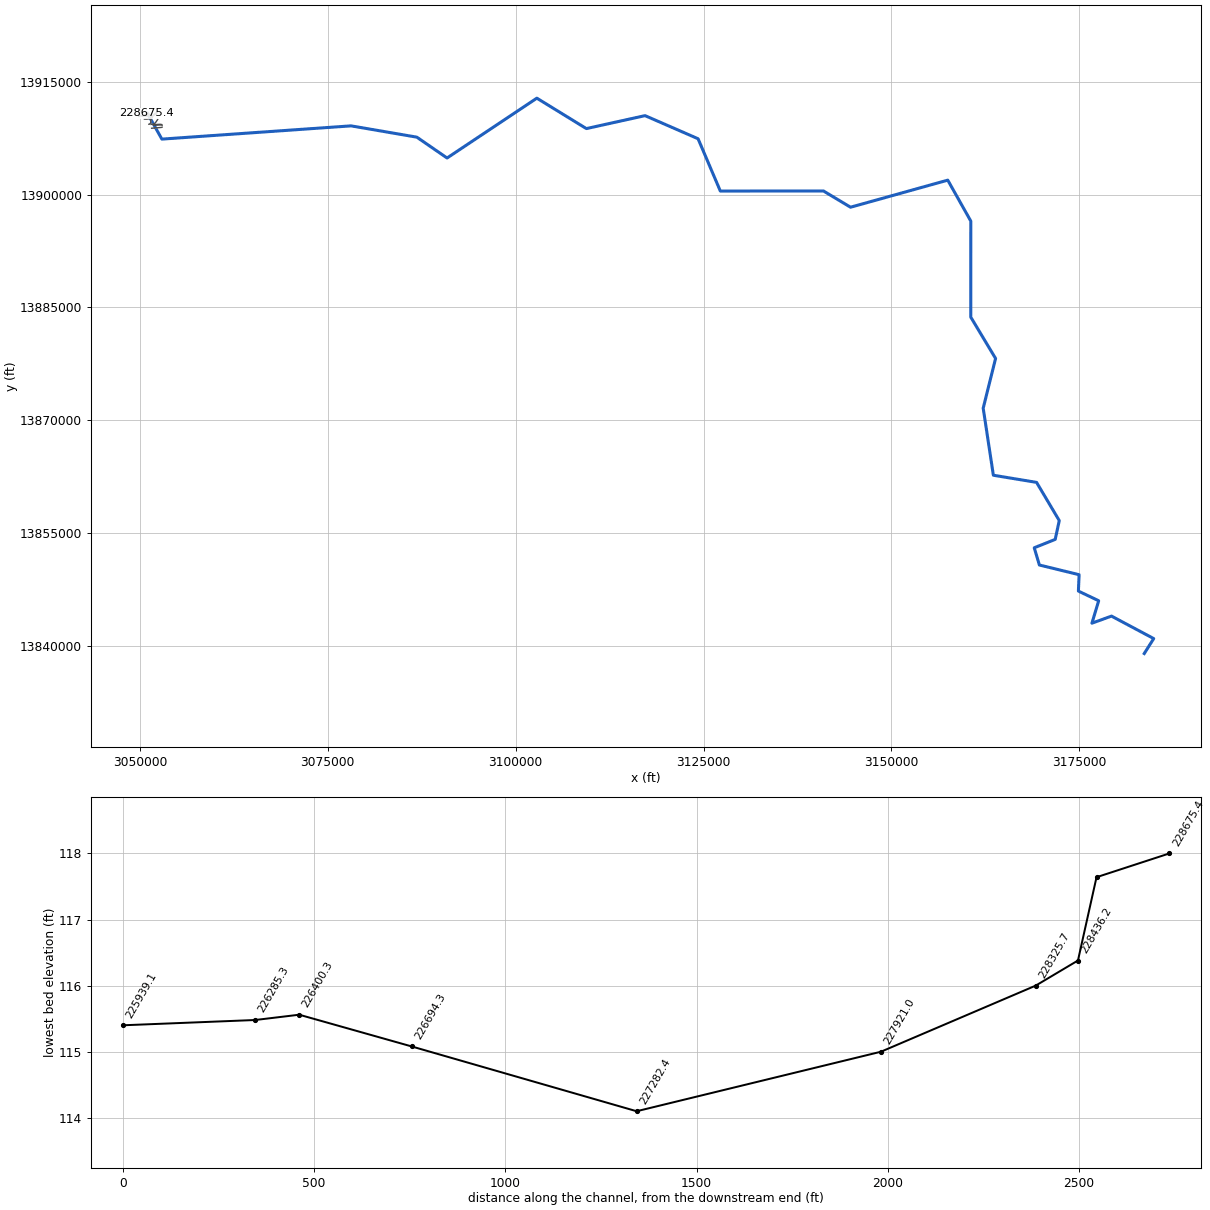
HEC-RAS study P100-00-00.prj: P100-00-00

--- P100-00-00.p01 (plan) ---

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Plan Title=Effective Multi-Profile 2020
Short Identifier=Effective MP 2020
Geom File=g01
Flow File=f01
Encroach Param= 0 ,0,0, 2

--- P100-00-00.f02 (steady flow) ---

Flow Title=Effective Floodway 2018
Version=Version 3.0.1  May 2012
Number of Profiles= 2
Profile Names=1PCT_100yr,Floodway
River Rch & RM=P100-00-00,P100-00-00_0010 ,228675.4
     357     357
River Rch & RM=P100-00-00,P100-00-00_0010 ,228484.7
     366     366
River Rch & RM=P100-00-00,P100-00-00_0010 ,228436.2
     389     389
River Rch & RM=P100-00-00,P100-00-00_0010 ,227921
     427     427
River Rch & RM=P100-00-00,P100-00-00_0010 ,227282.4
     466     466
River Rch & RM=P100-00-00,P100-00-00_0010 ,226694.3
     487     487
River Rch & RM=P100-00-00,P100-00-00_0010 ,226400.3
     522     522
River Rch & RM=P100-00-00,P100-00-00_0010 ,225939.1
     558     558
River Rch & RM=P100-00-00,P100-00-00_0010 ,225480
     587     587
River Rch & RM=P100-00-00,P100-00-00_0010 ,225142.8
     615     615
River Rch & RM=P100-00-00,P100-00-00_0010 ,224949.2
     664     664
River Rch & RM=P100-00-00,P100-00-00_0010 ,224308.4
     696     696
River Rch & RM=P100-00-00,P100-00-00_0010 ,223997.9
     800     800
River Rch & RM=P100-00-00,P100-00-00_0010 ,223061.5
     941     941
River Rch & RM=P100-00-00,P100-00-00_0010 ,221964.2
    1049    1049
River Rch & RM=P100-00-00,P100-00-00_0010 ,221230.4
    1088    1088
River Rch & RM=P100-00-00,P100-00-00_0010 ,220984.2
    1147    1147
River Rch & RM=P100-00-00,P100-00-00_0010 ,220631.9
    1212    1212
River Rch & RM=P100-00-00,P100-00-00_0010 ,220257.4
    1260    1260
River Rch & RM=P100-00-00,P100-00-00_0010 ,219998.9
    1308    1308
River Rch & RM=P100-00-00,P100-00-00_0010 ,219744.4
    1962    1962
River Rch & RM=P100-00-00,P100-00-00_0010 ,215936.4
    2676    2676
River Rch & RM=P100-00-00,P100-00-00_0010 ,213673.1
    2942    2942
River Rch & RM=P100-00-00,P100-00-00_0010 ,211630.6
    3102    3102
River Rch & RM=P100-00-00,P100-00-00_0010 ,210022.7
    3461    3461
River Rch & RM=P100-00-00,P100-00-00_0010 ,209411
    4122    4122
River Rch & RM=P100-00-00,P100-00-00_0010 ,209281.4
    4359    4359
River Rch & RM=P100-00-00,P100-00-00_0010 ,208303.8
    4549    4549
River Rch & RM=P100-00-00,P100-00-00_0010 ,207557.1
    4735    4735
River Rch & RM=P100-00-00,P100-00-00_0010 ,206854.1
    4922    4922
River Rch & RM=P100-00-00,P100-00-00_0010 ,206174
    5150    5150
River Rch & RM=P100-00-00,P100-00-00_0010 ,204744.1
    5296    5296
River Rch & RM=P100-00-00,P100-00-00_0010 ,203825.7
    5447    5447
River Rch & RM=P100-00-00,P100-00-00_0010 ,202904.2
    5496    5496
River Rch & RM=P100-00-00,P100-00-00_0010 ,199501.1
    5548    5548
River Rch & RM=P100-00-00,P100-00-00_0010 ,197172.9
    5572    5572
River Rch & RM=P100-00-00,P100-00-00_0010 ,196097
    5625    5625
River Rch & RM=P100-00-00,P100-00-00_0010 ,193896.3
    5644    5644
River Rch & RM=P100-00-00,P100-00-00_0010 ,192935.6
    5906    5906
River Rch & RM=P100-00-00,P100-00-00_0010 ,186609.7
    5917    5917
River Rch & RM=P100-00-00,P100-00-00_0010 ,185578.7
    5943    5943
River Rch & RM=P100-00-00,P100-00-00_0010 ,183348.2
    7687    7687
River Rch & RM=P100-00-00,P100-00-00_0010 ,181739.5
    7835    7835
River Rch & RM=P100-00-00,P100-00-00_0010 ,179921.2
    7943    7943
River Rch & RM=P100-00-00,P100-00-00_0010 ,178661.5
    8044    8044
River Rch & RM=P100-00-00,P100-00-00_0010 ,177406.7
    8134    8134
River Rch & RM=P100-00-00,P100-00-00_0010 ,176342.1
    8211    8211
River Rch & RM=P100-00-00,P100-00-00_0010 ,175549.5
    8328    8328
River Rch & RM=P100-00-00,P100-00-00_0010 ,174086.8
    8421    8421
River Rch & RM=P100-00-00,P100-00-00_0010 ,173023.1
    9755    9755
River Rch & RM=P100-00-00,P100-00-00_0010 ,171583.6
   10062   10062
River Rch & RM=P100-00-00,P100-00-00_0010 ,169319.2
   18532   18532
River Rch & RM=P100-00-00,P100-00-00_0010 ,161801.4
   19098   19098
River Rch & RM=P100-00-00,P100-00-00_0010 ,157981.7
   18679   18679
River Rch & RM=P100-00-00,P100-00-00_0010 ,155378.8
   19513   19513
River Rch & RM=P100-00-00,P100-00-00_0010 ,151806.5
   20274   20274
River Rch & RM=P100-00-00,P100-00-00_0010 ,142362
   21485   21485
River Rch & RM=P100-00-00,P100-00-00_0010 ,132316.5
   22991   22991
River Rch & RM=P100-00-00,P100-00-00_0010 ,122757.9
   22991   22991
River Rch & RM=P100-00-00,P100-00-00_0010 ,111431.6
   23276   23276
River Rch & RM=P100-00-00,P100-00-00_0010 ,100298.8
   31669   31669
River Rch & RM=P100-00-00,P100-00-00_0010 ,85105.8
   32258   32258
River Rch & RM=P100-00-00,P100-00-00_0010 ,81700.8
   32565   32565
River Rch & RM=P100-00-00,P100-00-00_0010 ,71993.7
   33098   33098
River Rch & RM=P100-00-00,P100-00-00_0010 ,64048.7
   44000   44000
River Rch & RM=P100-00-00,P100-00-00_0010 ,52958.0
   44832   44832
River Rch & RM=P100-00-00,P100-00-00_0010 ,46018.3
   45118   45118
River Rch & RM=P100-00-00,P100-00-00_0010 ,43183.7
   45456   45456
River Rch & RM=P100-00-00,P100-00-00_0010 ,38132.0
   48012   48012
River Rch & RM=P100-00-00,P100-00-00_0010 ,19924.3
   48703   48703
Boundary for River Rch & Prof#=P100-00-00,P100-00-00_0010 , 1
Up Type= 0
Dn Type= 3
Dn Slope=.00005
Boundary for River Rch & Prof#=P100-00-00,P100-00-00_0010 , 2
Up Type= 0
Dn Type= 3
Dn Slope=.00005
DSS Import GetInterval= 0
DSS Import GetPeak= 0
DSS Import FillOption= 0

--- P100-00-00.f01 (steady flow) ---

Flow Title=Effective Multi-Profile 2018
Version=Version 3.0.1  May 2012
Number of Profiles= 4
Profile Names=10PCT_10yr, 2PCT_50yr, 1PCT_100yr, 0.2PCT_500yr
River Rch & RM=P100-00-00,P100-00-00_0010 ,228675.4
     210     308     357     500
River Rch & RM=P100-00-00,P100-00-00_0010 ,228484.7
     215     315     366     512
River Rch & RM=P100-00-00,P100-00-00_0010 ,228436.2
     228     334     389     544
River Rch & RM=P100-00-00,P100-00-00_0010 ,227921
     251     368     427     598
River Rch & RM=P100-00-00,P100-00-00_0010 ,227282.4
     273     401     466     652
River Rch & RM=P100-00-00,P100-00-00_0010 ,226694.3
     286     419     487     681
River Rch & RM=P100-00-00,P100-00-00_0010 ,226400.3
     306     449     522     730
River Rch & RM=P100-00-00,P100-00-00_0010 ,225939.1
     327     481     558     781
River Rch & RM=P100-00-00,P100-00-00_0010 ,225480
     344     505     587     821
River Rch & RM=P100-00-00,P100-00-00_0010 ,225142.8
     361     529     615     860
River Rch & RM=P100-00-00,P100-00-00_0010 ,224949.2
     390     572     664     929
River Rch & RM=P100-00-00,P100-00-00_0010 ,224308.4
     408     599     696     973
River Rch & RM=P100-00-00,P100-00-00_0010 ,223997.9
     469     688     800    1119
River Rch & RM=P100-00-00,P100-00-00_0010 ,223061.5
     552     810     941    1316
River Rch & RM=P100-00-00,P100-00-00_0010 ,221964.2
     615     903    1049    1468
River Rch & RM=P100-00-00,P100-00-00_0010 ,221230.4
     638     937    1088    1523
River Rch & RM=P100-00-00,P100-00-00_0010 ,220984.2
     673     987    1147    1604
River Rch & RM=P100-00-00,P100-00-00_0010 ,220631.9
     711    1044    1212    1696
River Rch & RM=P100-00-00,P100-00-00_0010 ,220257.4
     739    1084    1260    1762
River Rch & RM=P100-00-00,P100-00-00_0010 ,219998.9
     767    1126    1308    1830
River Rch & RM=P100-00-00,P100-00-00_0010 ,219744.4
    1170    1694    1962    2714
River Rch & RM=P100-00-00,P100-00-00_0010 ,215936.4
    1845    2354    2676    3747
River Rch & RM=P100-00-00,P100-00-00_0010 ,213673.1
    2003    2598    2942    3774
River Rch & RM=P100-00-00,P100-00-00_0010 ,211630.6
    2097    2745    3102    3789
River Rch & RM=P100-00-00,P100-00-00_0010 ,210022.7
    2299    3046    3461    4290
River Rch & RM=P100-00-00,P100-00-00_0010 ,209411
    2663    3597    4122    5233
River Rch & RM=P100-00-00,P100-00-00_0010 ,209281.4
    2813    3826    4359    5557
River Rch & RM=P100-00-00,P100-00-00_0010 ,208303.8
    2933    4011    4549    5817
River Rch & RM=P100-00-00,P100-00-00_0010 ,207557.1
    3051    4193    4735    6074
River Rch & RM=P100-00-00,P100-00-00_0010 ,206854.1
    3169    4377    4922    6333
River Rch & RM=P100-00-00,P100-00-00_0010 ,206174
    3324    4586    5150    6638
River Rch & RM=P100-00-00,P100-00-00_0010 ,204744.1
    3425    4720    5296    6834
River Rch & RM=P100-00-00,P100-00-00_0010 ,203825.7
    3529    4859    5447    7037
River Rch & RM=P100-00-00,P100-00-00_0010 ,202904.2
    3529    4891    5496    7173
River Rch & RM=P100-00-00,P100-00-00_0010 ,199501.1
    3529    4925    5548    7318
River Rch & RM=P100-00-00,P100-00-00_0010 ,197172.9
    3529    4941    5572    7386
River Rch & RM=P100-00-00,P100-00-00_0010 ,196097
    3529    4975    5625    7535
River Rch & RM=P100-00-00,P100-00-00_0010 ,193896.3
    3529    4987    5644    7590
River Rch & RM=P100-00-00,P100-00-00_0010 ,192935.6
    4617    5616    5906    7929
River Rch & RM=P100-00-00,P100-00-00_0010 ,186609.7
    4663    5633    5917    7929
River Rch & RM=P100-00-00,P100-00-00_0010 ,185578.7
    4770    5671    5943    7929
River Rch & RM=P100-00-00,P100-00-00_0010 ,183348.2
    5693    7142    7687    9040
River Rch & RM=P100-00-00,P100-00-00_0010 ,181739.5
    5786    7268    7835    9240
River Rch & RM=P100-00-00,P100-00-00_0010 ,179921.2
    5853    7360    7943    9388
River Rch & RM=P100-00-00,P100-00-00_0010 ,178661.5
    5916    7446    8044    9525
River Rch & RM=P100-00-00,P100-00-00_0010 ,177406.7
    5972    7523    8134    9648
River Rch & RM=P100-00-00,P100-00-00_0010 ,176342.1
    6020    7588    8211    9753
River Rch & RM=P100-00-00,P100-00-00_0010 ,175549.5
    6092    7688    8328    9914
River Rch & RM=P100-00-00,P100-00-00_0010 ,174086.8
    6150    7767    8421   10042
River Rch & RM=P100-00-00,P100-00-00_0010 ,173023.1
    6917    9040    9755   12208
River Rch & RM=P100-00-00,P100-00-00_0010 ,171583.6
    7071    9298   10062   12508
River Rch & RM=P100-00-00,P100-00-00_0010 ,169319.2
   11592   15973   18532   23457
River Rch & RM=P100-00-00,P100-00-00_0010 ,161801.4
   11871   16415   19098   24108
River Rch & RM=P100-00-00,P100-00-00_0010 ,157981.7
   12075   16168   18679   23048
River Rch & RM=P100-00-00,P100-00-00_0010 ,155378.8
   12446   16738   19513   24583
River Rch & RM=P100-00-00,P100-00-00_0010 ,151806.5
   12701   17269   20274   25284
River Rch & RM=P100-00-00,P100-00-00_0010 ,142362
   13265   18318   21485   26954
River Rch & RM=P100-00-00,P100-00-00_0010 ,132316.5
   14969   18952   22991   29052
River Rch & RM=P100-00-00,P100-00-00_0010 ,122757.9
   15118   18989   22991   29327
River Rch & RM=P100-00-00,P100-00-00_0010 ,111431.6
   15522   19544   23276   30552
River Rch & RM=P100-00-00,P100-00-00_0010 ,100298.8
   21042   27399   31669   45828
River Rch & RM=P100-00-00,P100-00-00_0010 ,85105.8
   21748   28541   32258   47107
River Rch & RM=P100-00-00,P100-00-00_0010 ,81700.8
   22123   29100   32565   47165
River Rch & RM=P100-00-00,P100-00-00_0010 ,71993.7
   22944   29725   33098   47684
River Rch & RM=P100-00-00,P100-00-00_0010 ,64048.7
   32159   40326   44000   60382
River Rch & RM=P100-00-00,P100-00-00_0010 ,52958
   32682   40973   44832   60382
River Rch & RM=P100-00-00,P100-00-00_0010 ,46018.3
   32810   41148   45118   60382
River Rch & RM=P100-00-00,P100-00-00_0010 ,43183.7
   32923   41326   45456   60382
River Rch & RM=P100-00-00,P100-00-00_0010 ,38132
   33762   42937   48012   61567
River Rch & RM=P100-00-00,P100-00-00_0010 ,19924.3
   33914   43247   48703   61832
Boundary for River Rch & Prof#=P100-00-00,P100-00-00_0010 , 1
Up Type= 0
Dn Type= 3
Dn Slope=.00005
Boundary for River Rch & Prof#=P100-00-00,P100-00-00_0010 , 2
Up Type= 0
Dn Type= 3
Dn Slope=.00005
Boundary for River Rch & Prof#=P100-00-00,P100-00-00_0010 , 3
Up Type= 0
Dn Type= 3
Dn Slope=.00005
Boundary for River Rch & Prof#=P100-00-00,P100-00-00_0010 , 4
Up Type= 0
Dn Type= 3
Dn Slope=.000052
DSS Import GetInterval= 0
DSS Import GetPeak= 0
DSS Import FillOption= 0

--- P100-00-00.g01 (geometry) ---

Geom Title=P100-00-00 2020
Program Version=5.07

River Reach=P100-00-00      ,P100-00-00_0010
Reach XY= 30
       3051008.1     13910827.73      3052923.75       13907399.
        3078096.       13909162.      3086848.75       13907658.
      3090870.17     13904886.79        3102817.       13912846.
      3109404.25       13908798.      3117211.49     13910522.97
      3124267.86     13907447.58       3127228.5       13900488.
       3140950.5       13900499.      3144555.25       13898337.
       3157489.5       13901939.      3160556.25       13896488.
      3160546.75       13883722.      3163850.76     13878215.23
        3162204.       13871597.      3163555.25       13862678.
        3169304.       13861726.      3172324.25       13856643.
        3171784.       13854142.      3168993.18     13853026.67
      3169677.75       13850734.       3174964.5       13849443.
      3174869.66     13847263.57      3177570.25       13845976.
        3176667.       13842989.      3179274.25       13843935.
      3184890.25       13840943.      3183632.25       13838954.

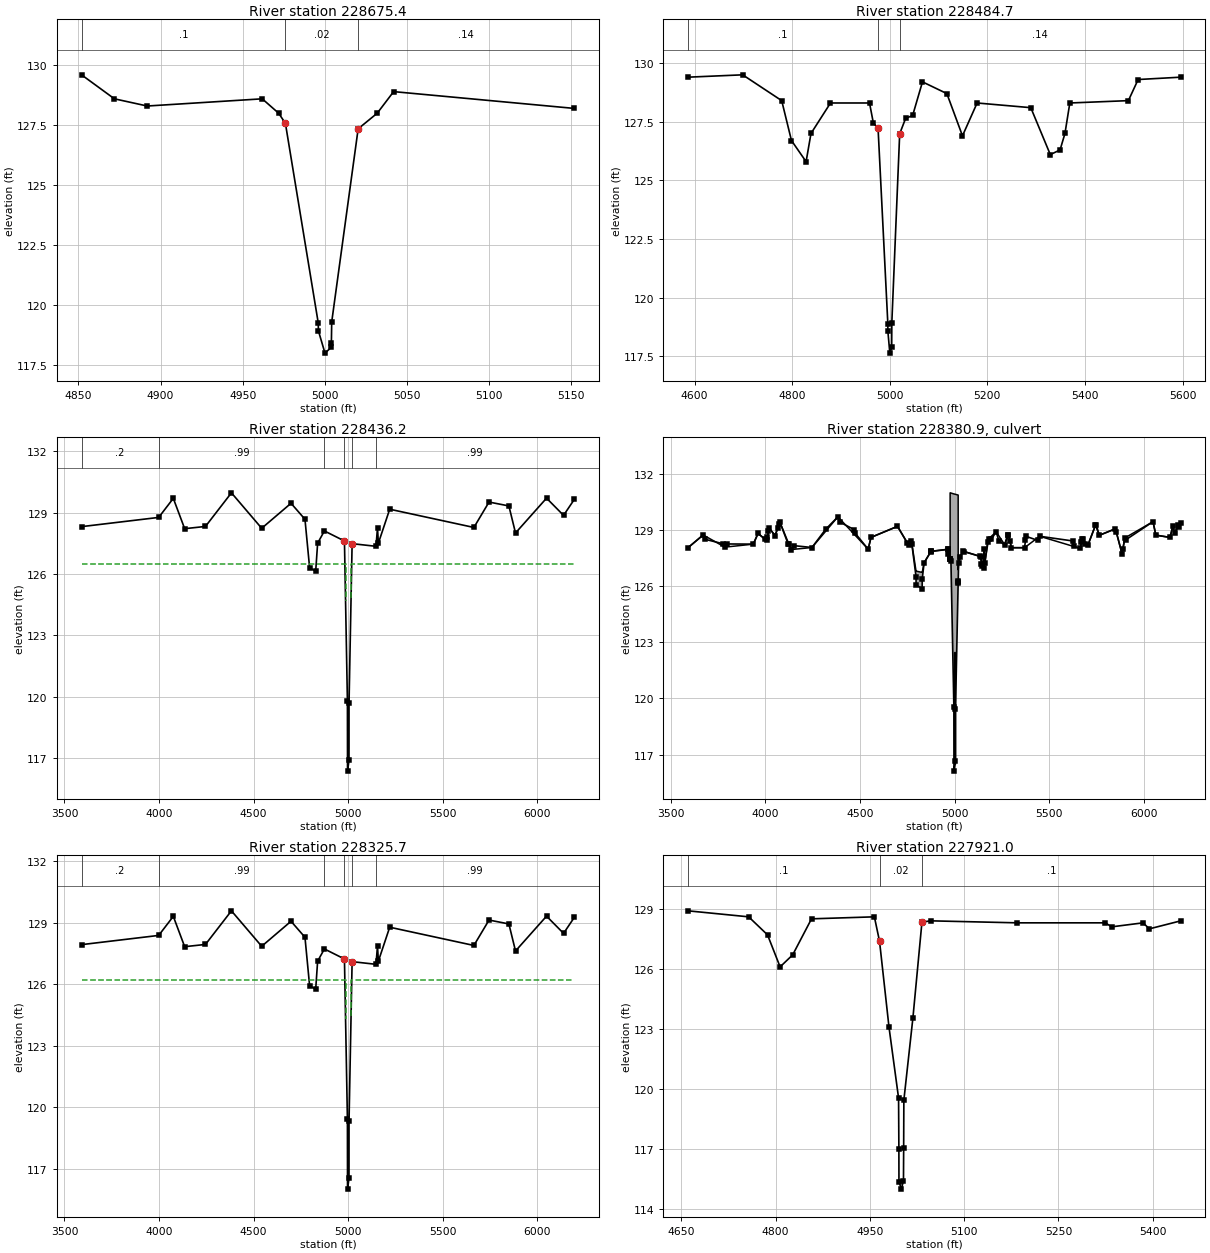
Type RM Length L Ch R = 1 ,228675.4,191.4,190.7,189.9
BEGIN DESCRIPTION:
Cross Section 228675.4-Interpolated
END DESCRIPTION:
XS GIS Cut Line= 2
      3051155.57      13910841.3      3050856.84     13910813.73
#Sta/Elev= 16
  4851.9   129.6  4871.9   128.6  4891.9   128.3  4961.9   128.6  4971.9     128
    4976  127.58    4996  119.26  4996.1  118.93  5000.1     118  5003.9  118.24
    5004  118.43  5004.2   119.3  5020.3  127.35  5031.9     128  5041.9   128.9
  5151.9   128.2
#Mann= 3 , 1 , 0
  4851.9      .1       0    4976     .02       0  5020.3     .14       0
Bank Sta=4976,5020.3
XS Rating Curve= 0 ,0
Exp/Cntr=0.3,0.1

Type RM Length L Ch R = 1 ,228484.7,57.2,48.55,45.1
BEGIN DESCRIPTION:
Cross Section 228484.7
END DESCRIPTION:
XS GIS Cut Line= 6
      3051422.03     13910677.44      3051317.53     13910637.17
      3051049.03     13910639.37      3050877.37     13910628.37
      3050430.62     13910604.16      3050420.66     13910603.48
#Sta/Elev= 30
  4586.5   129.4  4698.5   129.5  4778.5   128.4  4798.5   126.7  4828.5   125.8
  4838.5     127  4878.5   128.3  4958.5   128.3  4966.3  127.45    4976  127.22
    4996   118.9  4996.1  118.57  5000.1  117.64  5003.9  117.88  5004.2  118.94
  5020.3  126.99  5032.4  127.64  5046.9  127.77    5067   129.2    5117   128.7
    5149   126.9    5179   128.3    5289   128.1    5329   126.1    5349   126.3
    5359     127    5369   128.3    5489   128.4    5509   129.3  5596.4   129.4
#Mann= 3 , 1 , 0
  4586.5      .1       0    4976     .02       0  5020.3     .14       0
#XS Ineff= 2 , 0
       0  4878.5   128.3    5067       0   129.2
Permanent Ineff=
       F       F
Bank Sta=4976,5020.3
XS Rating Curve= 0 ,0
Exp/Cntr=0.5,0.3

Type RM Length L Ch R = 1 ,228436.2,110.5,110.5,110.5
BEGIN DESCRIPTION:
Upstream Section of Bridge/Culvert/Weir
END DESCRIPTION:
XS GIS Cut Line= 6
      3052241.52     13910977.58      3051673.08     13910529.08
      3051368.05     13910468.34      3051104.13     13910576.43
      3050936.24     13910602.35      3049825.32     13910527.71
#Sta/Elev= 30
  3590.5  128.31  3998.2  128.76  4075.5  129.69  4135.5  128.21  4245.5  128.32
  4382.7  129.96  4542.7  128.23  4697.7  129.45  4771.4  128.67  4795.9  126.31
  4828.1  126.13  4838.3   127.5    4874   128.1  4980.1  127.61  4995.8  119.78
  4996.4  116.38  5004.2  116.91  5004.3   119.7  5020.6  127.48    5147  127.35
  5154.8  128.26  5159.3   127.5  5219.3  129.16  5664.3  128.27  5744.3  129.51
  5849.3  129.32  5884.3     128  6048.3   129.7  6138.3  128.86  6195.1  129.64
#Mann= 6 , 1 , 0
  3590.5      .2       0  3998.2     .99       0    4874      .1       0
  4980.1     .02       0  5020.6      .1       0    5147     .99       0
#XS Ineff= 2 , 0
       0    4986   126.5    5015       0   126.5
Permanent Ineff=
       F       F
Bank Sta=4980.1,5020.6
XS Rating Curve= 0 ,0
Exp/Cntr=0.5,0.3

Type RM Length L Ch R = 2 ,228380.9,,,
BEGIN DESCRIPTION:
MILLRIDGE ROAD
Structure ID: P00-97
END DESCRIPTION:
Bridge Culvert--1,0,-1,-1, 0
Deck Dist Width WeirC Skew NumUp NumDn MinLoCord MaxHiCord MaxSubmerge Is_Ogee
10,90.5,3,0, 60, 60, , , 0.95, 0, 1,1,,
  3590.5  3670.5  3785.5  3935.5  3960.5  4005.5  4020.5  4050.5  4075.5  4135.5
  4245.5  4382.7  4542.7  4557.7  4697.7    4757  4771.4  4795.7  4795.9  4828.1
  4828.5  4838.3  4874.9  4966.2 4975.89    4976  4980.1  4995.8  4996.4  5004.2
  5004.3  5018.5 5018.61  5020.6  5042.4  5137.2  5152.8  5154.8  5159.3  5179.3
  5219.3  5264.3  5284.3  5299.3  5369.3  5449.3  5664.3  5674.3  5704.3  5744.3
  5764.3  5849.3  5884.3  5899.3  6048.3  6063.3  6138.3  6153.3  6163.3  6195.1
  128.05  128.73  128.08  128.24  128.81  128.44  129.08   128.7  129.43  127.95
  128.06   129.7  127.97   128.6  129.19  128.19  128.42   126.8   126.8  126.73
  126.73  127.25  127.86  127.97  127.48  130.98  130.97  130.92  130.92   130.9
   130.9  130.86  126.86  127.23  127.87  127.58  126.99     128  127.24  128.52
   128.9  128.21  128.71  128.05  128.05  128.66  128.01  128.53  128.19  129.25
  128.71  129.06  127.74  128.57  129.44  128.72   128.6  129.21  128.84  129.38
  128.05  128.73  128.08  128.24  128.81  128.44  129.08   128.7  129.43  127.95
  128.06   129.7  127.97   128.6  129.19  128.18  128.41  126.51  126.05  125.87
  126.38  127.24  127.85  127.96  127.47  127.47  127.35  119.52  116.12  116.65
  119.44  126.22  126.27  127.22  127.86  127.58  126.99     128  127.24  128.52
   128.9  128.21  128.71  128.05  128.05  128.66  128.01  128.53  128.19  129.25
  128.71  129.06  127.74  128.57  129.44  128.72   128.6  129.21  128.84  129.38
  3590.5  3670.5  3785.5  3935.5  3960.5  4005.5  4020.5  4050.5  4075.5  4135.5
  4245.5  4382.7  4542.7  4557.7  4697.7    4757  4771.4  4795.7  4795.9  4828.1
  4828.5  4838.3  4874.9  4966.2 4975.89    4976  4980.1  4995.8  4996.4  5004.2
  5004.3  5018.5 5018.61  5020.6  5042.4  5137.2  5152.8  5154.8  5159.3  5179.3
  5219.3  5264.3  5284.3  5299.3  5369.3  5449.3  5664.3  5674.3  5704.3  5744.3
  5764.3  5849.3  5884.3  5899.3  6048.3  6063.3  6138.3  6153.3  6163.3  6195.1
  128.05  128.73  128.08  128.24  128.81  128.44  129.08   128.7  129.43  127.95
  128.06   129.7  127.97   128.6  129.19  128.19  128.42   126.8   126.8  126.73
  126.73  127.25  127.86  127.97  127.48  130.98  130.97  130.92  130.92   130.9
   130.9  130.86  126.86  127.23  127.87  127.58  126.99     128  127.24  128.52
   128.9  128.21  128.71  128.05  128.05  128.66  128.01  128.53  128.19  129.25
  128.71  129.06  127.74  128.57  129.44  128.72   128.6  129.21  128.84  129.38
  127.95  128.63  127.98  128.14  128.71  128.34  128.98   128.6  129.33  127.85
  127.96   129.6  127.87   128.5  129.09  128.08  128.31  126.41  125.95  125.77
  126.28  127.14  127.75  127.86  127.37  127.37  127.25  119.42  116.02  116.55
  119.34  126.12  126.17  127.12  127.76  127.48  126.89   127.9  127.14  128.42
   128.8  128.11  128.61  127.95  127.95  128.56  127.91  128.43  128.09  129.15
  128.61  128.96  127.64  128.47  129.34  128.62   128.5  129.11  128.74  129.28
BR Coef= 1 , 0 , 0 ,1.25, 0 ,,,0.8,-1,2,0,
WSPro=,,,, 1 ,,,, 0 ,,,, 0 ,,,,-1 ,-1 ,-1 , 0 , 0 , 0 , 0 , 0
Culvert=2,6,8,90.5,0.015,0.5,1,8,1,116.5,5000.2,116.4,5000.2,Culvert #1  , 0 ,10
  5000.2  5000.2
BC Culvert Barrel=1,,0
Culvert Bottom n=0.015
BR U #Sta/Elev= 107
  3590.5  128.05  3670.5  128.73  3680.5   128.5  3775.5  128.26  3785.5  128.08
  3795.5  128.25  3935.5  128.24  3960.5  128.81  3998.2   128.5  4005.5  128.44
  4010.5   128.6  4015.5  128.93  4020.5  129.08  4050.5   128.7  4065.5  129.09
  4070.5  129.34  4075.5  129.43  4120.5  128.23  4125.5  128.23  4135.5  127.95
  4150.5  128.16  4245.5  128.06  4317.7  129.03  4382.7   129.7  4392.7  129.42
  4467.7  129.02  4472.7  128.84  4542.7  127.97  4557.7   128.6  4697.7  129.19
  4749.1  128.31    4757  128.18  4771.4  128.41  4773.7  128.23  4795.7  126.51
  4795.9  126.05  4828.1  125.87  4828.5  126.38  4838.3  127.24    4874  127.84
  4874.9  127.85  4876.8  127.85  4962.3  127.96  4966.2  127.96  4967.3  127.71
 4975.89  127.47    4976  127.47 4976.11  127.46  4980.1  127.35  4995.8  119.52
  4996.4  116.12  5004.2  116.65  5004.3  119.44 5018.39  126.17  5018.5  126.22
 5018.61  126.27  5020.6  127.22  5027.7  127.57  5042.4  127.86  5050.1  127.84
  5133.1  127.59  5137.2  127.58  5140.3   127.2    5147  127.09  5152.8  126.99
  5154.8     128  5159.3  127.24  5174.3  128.38  5179.3  128.52  5194.3  128.51
  5219.3   128.9  5234.3   128.4  5264.3  128.21  5279.3  128.74  5284.3  128.71
  5294.3  128.39  5299.3  128.05  5369.3  128.05  5374.3  128.44  5379.3  128.65
  5439.3  128.44  5449.3  128.66  5624.3  128.41  5629.3  128.12  5664.3  128.01
  5669.3  128.36  5674.3  128.53  5679.3  128.49  5689.3  128.23  5704.3  128.19
  5744.3  129.25  5749.3  129.24  5764.3  128.71  5849.3  129.06  5854.3  128.89
  5884.3  127.74  5889.3  127.96  5899.3  128.57  5904.3  128.47  6048.3  129.44
  6063.3  128.72  6138.3   128.6  6153.3  129.21  6163.3  128.84  6178.3  129.26
  6183.3  129.13  6195.1  129.38
BR U #Mann= 6
  3590.5      .2  3998.2     .99    4874      .1  4980.1     .02  5020.6      .1
    5147     .99
BR U Banks=4980.1,5020.6
BR D #Sta/Elev= 107
  3590.5  127.95  3670.5  128.63  3680.5   128.4  3775.5  128.16  3785.5  127.98
  3795.5  128.15  3935.5  128.14  3960.5  128.71  3998.2   128.4  4005.5  128.34
  4010.5   128.5  4015.5  128.83  4020.5  128.98  4050.5   128.6  4065.5  128.99
  4070.5  129.24  4075.5  129.33  4120.5  128.13  4125.5  128.13  4135.5  127.85
  4150.5  128.06  4245.5  127.96  4317.7  128.93  4382.7   129.6  4392.7  129.32
  4467.7  128.92  4472.7  128.74  4542.7  127.87  4557.7   128.5  4697.7  129.09
  4749.1  128.21    4757  128.08  4771.4  128.31  4773.7  128.13  4795.7  126.41
  4795.9  125.95  4828.1  125.77  4828.5  126.28  4838.3  127.14    4874  127.74
  4874.9  127.75  4876.8  127.75  4962.3  127.86  4966.2  127.86  4967.3  127.61
 4975.89  127.37    4976  127.37 4976.11  127.36  4980.1  127.25  4995.8  119.42
  4996.4  116.02  5004.2  116.55  5004.3  119.34 5018.39  126.07  5018.5  126.12
 5018.61  126.17  5020.6  127.12  5027.7  127.47  5042.4  127.76  5050.1  127.74
  5133.1  127.49  5137.2  127.48  5140.3   127.1    5147  126.99  5152.8  126.89
  5154.8   127.9  5159.3  127.14  5174.3  128.28  5179.3  128.42  5194.3  128.41
  5219.3   128.8  5234.3   128.3  5264.3  128.11  5279.3  128.64  5284.3  128.61
  5294.3  128.29  5299.3  127.95  5369.3  127.95  5374.3  128.34  5379.3  128.55
  5439.3  128.34  5449.3  128.56  5624.3  128.31  5629.3  128.02  5664.3  127.91
  5669.3  128.26  5674.3  128.43  5679.3  128.39  5689.3  128.13  5704.3  128.09
  5744.3  129.15  5749.3  129.14  5764.3  128.61  5849.3  128.96  5854.3  128.79
  5884.3  127.64  5889.3  127.86  5899.3  128.47  5904.3  128.37  6048.3  129.34
  6063.3  128.62  6138.3   128.5  6153.3  129.11  6163.3  128.74  6178.3  129.16
  6183.3  129.03  6195.1  129.28
BR D #Mann= 6
  3590.5      .2  3998.2     .99    4874      .1  4980.1     .02  5020.6      .1
    5147     .99
BR D Banks=4980.1,5020.6
BC Design=,, 0 ,, 0 ,,,,,,
BC HTab HWMax=129.96
BC Use User HTab Curves=0
BC User HTab FreeFlow(D)= 0

Type RM Length L Ch R = 1 ,228325.7,404.65,404.65,404.65
BEGIN DESCRIPTION:
Downstream Section of Bridge/Culvert/Weir
END DESCRIPTION:
XS GIS Cut Line= 6
      3052251.15      13910867.5      3051682.72       13910419.
      3051377.69     13910358.26      3051113.77     13910466.35
      3050945.88     13910492.27      3049834.96     13910417.63
#Sta/Elev= 30
  3590.5  127.93  3998.2  128.38  4075.5  129.31  4135.5  127.83  4245.5  127.94
  4382.7  129.58  4542.7  127.85  4697.7  129.07  4771.4  128.29  4795.9  125.93
  4828.1  125.75  4838.3  127.12    4874  127.72  4980.1  127.23  4995.8   119.4
  4996.4     116  5004.2  116.53  5004.3  119.32  5020.6   127.1    5147  126.97
  5154.8  127.88  5159.3  127.12  5219.3  128.78  5664.3  127.89  5744.3  129.13
  5849.3  128.94  5884.3  127.62  6048.3  129.32  6138.3  128.48  6195.1  129.26
#Mann= 6 , 1 , 0
  3590.5      .2       0  3998.2     .99       0    4874      .1       0
  4980.1     .02       0  5020.6      .1       0    5147     .99       0
#XS Ineff= 2 , 0
       0    4986   126.2    5015       0   126.2
Permanent Ineff=
       F       F
Bank Sta=4980.1,5020.6
XS Rating Curve= 0 ,0
Exp/Cntr=0.5,0.3

Type RM Length L Ch R = 1 ,227921.0,536.9,638.6,685
BEGIN DESCRIPTION:
Cross Section 227921.0-Interpolated
END DESCRIPTION:
XS GIS Cut Line= 4
      3051353.03     13910167.76      3051281.84     13910102.51
       3050857.3     13910052.56      3050597.51     13910061.92
#Sta/Elev= 25
  4660.7   128.9  4757.2   128.6  4787.2   127.7  4807.2   126.1  4827.2   126.7
  4857.2   128.5  4957.2   128.6  4965.4  127.38  4980.5  123.08  4995.7  119.55
  4996.2  116.98  4996.3  115.38  5000.2     115  5003.5  115.43  5003.8  117.03
  5004.1  119.44  5018.5  123.55  5032.9  128.34  5047.2   128.4  5184.7   128.3
  5324.7   128.3  5334.7   128.1  5384.7   128.3  5394.7     128  5444.7   128.4
#Mann= 3 , 1 , 0
  4660.7      .1       0  4965.4     .02       0  5032.9      .1       0
#XS Ineff= 2 , 0
       0  4857.2   128.5               0
Permanent Ineff=
       F       F
Bank Sta=4965.4,5032.9
XS Rating Curve= 0 ,0
Exp/Cntr=0.3,0.1

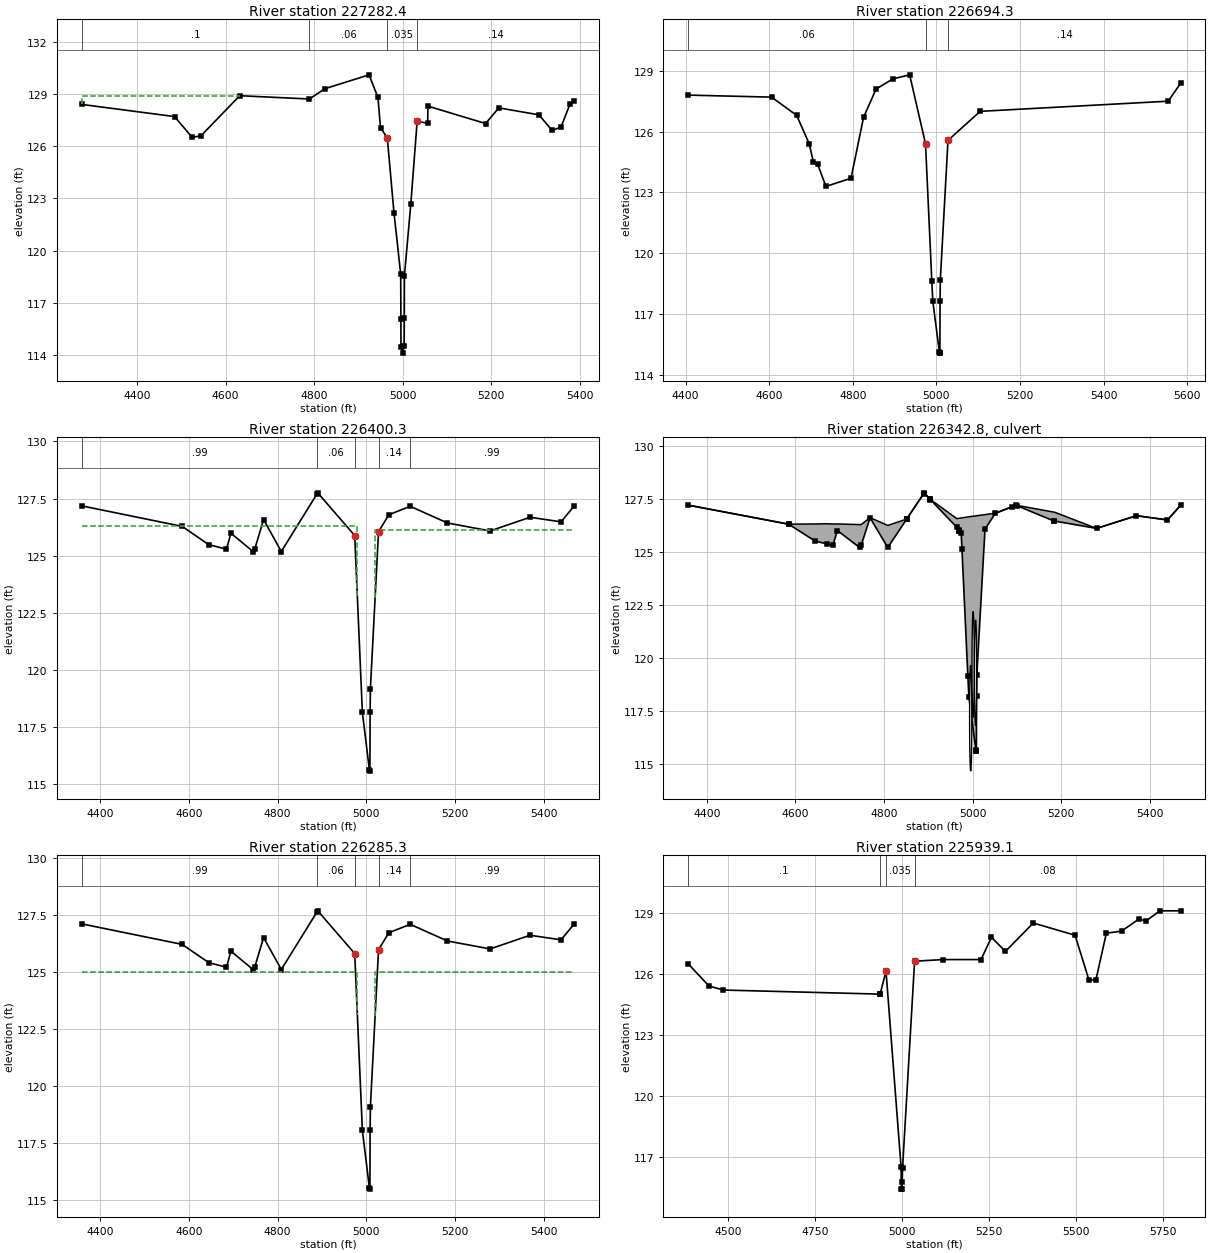
Type RM Length L Ch R = 1 ,227282.4,651.7,588.1,561.1
BEGIN DESCRIPTION:
Cross Section 227282.4
END DESCRIPTION:
XS GIS Cut Line= 6
       3051657.4     13910284.09      3051447.89     13909994.65
       3051462.8     13909802.96      3051442.48     13909570.75
      3051275.34     13909384.25      3051196.16     13909372.87
#Sta/Elev= 30
  4274.8   128.4  4484.8   127.7  4524.8   126.5  4544.8   126.6  4632.1   128.9
  4789.7  128.71  4824.3   129.3  4924.3   130.1  4944.3   128.8  4950.1  127.06
  4965.4  126.48  4980.5  122.18  4995.7  118.65  4996.2  116.08  4996.3  114.48
  5000.2   114.1  5003.5  114.53  5003.8  116.13  5004.1  118.54  5018.5  122.65
  5032.9  127.44  5056.5  127.31  5057.4   128.3  5187.4   127.3  5217.4   128.2
  5307.9   127.8  5337.9   126.9  5357.9   127.1  5377.9   128.4  5387.9   128.6
#Mann= 4 , 1 , 0
  4274.8      .1       0  4789.7     .06       0  4965.4    .035       0
  5032.9     .14       0
#XS Ineff= 2 , 0
       0  4632.1   128.9  5057.4       0   128.3
Permanent Ineff=
       F       F
Bank Sta=4965.4,5032.9
XS Rating Curve= 0 ,0
Exp/Cntr=0.3,0.1

Type RM Length L Ch R = 1 ,226694.3,449.1,294,231.4
BEGIN DESCRIPTION:
Cross Section 226694.3-Interpolated
END DESCRIPTION:
XS GIS Cut Line= 4
       3052369.5       13910016.      3052091.22     13909612.23
      3051956.78     13909452.58      3051485.84     13909359.72
#Sta/Elev= 24
  4405.7   127.8  4605.7   127.7  4665.7   126.8  4695.7   125.4  4705.7   124.5
  4715.7   124.4  4735.7   123.3  4795.7   123.7  4825.7   126.7  4855.7   128.1
    4896   128.6    4936   128.8    4974   125.4  4989.1  118.62  4991.3  117.66
  5007.2  115.13  5007.8   115.1  5008.4  115.08  5008.8  117.67  5009.4  118.69
  5027.8  125.57  5104.8     127  5554.8   127.5  5584.8   128.4
#Mann= 3 , 1 , 0
  4405.7     .06       0    4974     .04       0  5027.8     .14       0
#XS Ineff= 2 , 0
       0  4842.9   127.5               0
Permanent Ineff=
       F       F
Bank Sta=4974,5027.8
XS Rating Curve= 0 ,0
Exp/Cntr=0.5,0.3

Type RM Length L Ch R = 1 ,226400.3,115,115,115
BEGIN DESCRIPTION:
Upstream Section of Bridge/Culvert/Weir
END DESCRIPTION:
XS GIS Cut Line= 6
       3052891.9      13909339.5      3052775.04     13909364.26
      3052704.45     13909369.84      3052542.83     13909366.12
      3052188.01     13909347.54       3051786.6     13909297.74
#Sta/Elev= 25
  4357.7  127.18  4584.7  126.28  4644.7  125.48  4684.7  125.28  4694.7  125.98
  4744.7  125.18  4748.4  125.28  4768.4  126.58  4808.4  125.18  4889.2  127.71
  4890.6  127.75    4974  125.88  4991.3  118.14  5007.2  115.61  5008.3  115.56
  5008.8  118.15  5009.4  119.17  5027.8  126.05  5051.1  126.79  5099.2  127.16
  5183.1  126.43  5279.5  126.08  5369.5  126.68  5439.5  126.48  5469.5  127.18
#Mann= 5 , 1 , 0
  4357.7     .99       0  4889.2     .06       0    4974    .035       0
  5027.8     .14       0  5099.2     .99       0
#XS Ineff= 2 , 0
       0    4980   126.3    5020       0   126.1
Permanent Ineff=
       F       F
Bank Sta=4974,5027.8
XS Rating Curve= 0 ,0
Exp/Cntr=0.5,0.3

Type RM Length L Ch R = 2 ,226342.8,,,
BEGIN DESCRIPTION:
LOU EDD ROAD
Structure ID: P00-96
END DESCRIPTION:
Bridge Culvert--1,0,-1,-1, 0
Deck Dist Width WeirC Skew NumUp NumDn MinLoCord MaxHiCord MaxSubmerge Is_Ogee
10,95,2.6,0, 43, 43, , , 0.95, 0, 1,1,,
  4357.7  4584.6  4584.7  4644.7    4671  4684.7  4694.7  4744.7  4748.4  4768.4
  4808.4 4850.89    4851 4851.11  4889.2  4890.6 4904.29  4904.4 4904.51  4964.3
 4969.89    4970 4970.11    4974  4975.7  4989.1  4991.3  5007.2  5007.8  5008.3
  5008.8  5009.4  5027.8  5051.1  5088.9  5097.8  5099.2  5183.1  5184.1  5279.5
  5369.5  5439.5  5469.5
   127.2   126.3   126.3  126.31  126.32  126.31  126.31  126.28  126.28  126.61
  126.24  126.54  126.54  126.55  127.74  127.78  127.48  127.48  127.47  126.56
  126.58  126.58  126.58  126.59   126.6  126.64  126.65  126.69  126.69   126.7
   126.7   126.7  126.75  126.82  127.13   127.2  127.19  126.87  126.87   126.1
   126.7   126.5   127.2
   127.2   126.3   126.3   125.5  125.37   125.3     126   125.2   125.3   126.6
   125.2  126.53  126.53  126.54  127.73  127.77  127.47  127.47  127.46  126.15
  126.01     126     126   125.9  125.14  119.12  118.16  115.63   115.6  115.58
  118.17  119.19  126.07  126.81  127.12  127.19  127.18  126.45  126.45   126.1
   126.7   126.5   127.2
  4357.7  4584.6  4584.7  4644.7    4671  4684.7  4694.7  4744.7  4748.4  4768.4
  4808.4 4850.89    4851 4851.11  4889.2  4890.6 4904.29  4904.4 4904.51  4964.3
 4969.89    4970 4970.11    4974  4975.7  4989.1  4991.3  5007.2  5007.8  5008.3
  5008.8  5009.4  5027.8  5051.1  5088.9  5097.8  5099.2  5183.1  5184.1  5279.5
  5369.5  5439.5  5469.5
   127.2   126.3   126.3  126.31  126.32  126.31  126.31  126.28  126.28  126.61
  126.24  126.54  126.54  126.55  127.74  127.78  127.48  127.48  127.47  126.56
  126.58  126.58  126.58  126.59   126.6  126.64  126.65  126.69  126.69   126.7
   126.7   126.7  126.75  126.82  127.13   127.2  127.19  126.87  126.87   126.1
   126.7   126.5   127.2
   127.1   126.2   126.2   125.4  125.27   125.2   125.9   125.1   125.2   126.5
   125.1  126.43  126.43  126.44  127.63  127.67  127.37  127.37  127.36  126.05
  125.91   125.9   125.9   125.8  125.04  119.02  118.06  115.53   115.5  115.48
  118.07  119.09  125.97  126.71  127.02  127.09  127.08  126.35  126.35     126
   126.6   126.4   127.1
BR Coef= 1 , 0 , 0 ,1.25, 0 ,,,0.8,-1,2,0,
WSPro=,,,, 1 ,,,, 0 ,,,, 0 ,,,,-1 ,-1 ,-1 , 0 , 0 , 0 , 0 , 0
Culvert=1,5,,95,0.015,0.7,1,1,3,114.64,4995.5,114.54,4995.5,Culvert #1  , 0 ,10
  4995.5  4995.5
BC Culvert Barrel=1,,0
Culvert Bottom n=0.015
Culvert=1,5,,95,0.015,0.7,1,1,3,117.18,5001,117.08,5001,Culvert #2  , 0 ,10
    5001    5001
BC Culvert Barrel=1,,0
Culvert Bottom n=0.015
Culvert=1,5,,95,0.015,0.7,1,1,3,116.78,5006.5,116.68,5006.5,Culvert #3  , 0 ,10
  5006.5  5006.5
BC Culvert Barrel=1,,0
Culvert Bottom n=0.015
BR U #Sta/Elev= 43
  4357.7   127.2  4584.6   126.3  4584.7   126.3  4644.7   125.5    4671  125.37
  4684.7   125.3  4694.7     126  4744.7   125.2  4748.4   125.3  4768.4   126.6
  4808.4   125.2 4850.89  126.53    4851  126.53 4851.11  126.54  4889.2  127.73
  4890.6  127.77 4904.29  127.47  4904.4  127.47 4904.51  127.46  4964.3  126.15
 4969.89  126.01    4970     126 4970.11     126    4974   125.9  4975.7  125.14
  4989.1  119.12  4991.3  118.16  5007.2  115.63  5007.8   115.6  5008.3  115.58
  5008.8  118.17  5009.4  119.19  5027.8  126.07  5051.1  126.81  5088.9  127.12
  5097.8  127.19  5099.2  127.18  5183.1  126.45  5184.1  126.45  5279.5   126.1
  5369.5   126.7  5439.5   126.5  5469.5   127.2
BR U #Mann= 5
  4357.7     .99  4889.2     .06    4974    .015  5027.8     .14  5099.2     .99
BR U Banks=4974,5027.8
BR D #Sta/Elev= 43
  4357.7   127.1  4584.6   126.2  4584.7   126.2  4644.7   125.4    4671  125.27
  4684.7   125.2  4694.7   125.9  4744.7   125.1  4748.4   125.2  4768.4   126.5
  4808.4   125.1 4850.89  126.43    4851  126.43 4851.11  126.44  4889.2  127.63
  4890.6  127.67 4904.29  127.37  4904.4  127.37 4904.51  127.36  4964.3  126.05
 4969.89  125.91    4970   125.9 4970.11   125.9    4974   125.8  4975.7  125.04
  4989.1  119.02  4991.3  118.06  5007.2  115.53  5007.8   115.5  5008.3  115.48
  5008.8  118.07  5009.4  119.09  5027.8  125.97  5051.1  126.71  5088.9  127.02
  5097.8  127.09  5099.2  127.08  5183.1  126.35  5184.1  126.35  5279.5     126
  5369.5   126.6  5439.5   126.4  5469.5   127.1
BR D #Mann= 5
  4357.7     .99  4889.2     .06    4974    .015  5027.8     .14  5099.2     .99
BR D Banks=4974,5027.8
BC Design=,, 0 ,, 0 ,,,,,,
BC HTab HWMax=127.75
BC Use User HTab Curves=0
BC User HTab FreeFlow(D)= 0

Type RM Length L Ch R = 1 ,226285.3,346.2,346.2,346.2
BEGIN DESCRIPTION:
Downstream Section of Bridge/Culvert/Weir
END DESCRIPTION:
XS GIS Cut Line= 6
      3052963.19     13909249.26      3052846.32     13909274.02
      3052775.73      13909279.6      3052614.11     13909275.88
      3052259.29      13909257.3      3051857.89      13909207.5
#Sta/Elev= 25
  4357.7   127.1  4584.7   126.2  4644.7   125.4  4684.7   125.2  4694.7   125.9
  4744.7   125.1  4748.4   125.2  4768.4   126.5  4808.4   125.1  4889.2  127.63
  4890.6  127.67    4974   125.8  4991.3  118.06  5007.2  115.53  5008.3  115.48
  5008.8  118.07  5009.4  119.09  5027.8  125.97  5051.1  126.71  5099.2  127.08
  5183.1  126.35  5279.5     126  5369.5   126.6  5439.5   126.4  5469.5   127.1
#Mann= 5 , 1 , 0
  4357.7     .99       0  4889.2     .06       0    4974    .035       0
  5027.8     .14       0  5099.2     .99       0
#XS Ineff= 2 , 0
       0    4980     125    5020       0     125
Permanent Ineff=
       F       F
Bank Sta=4974,5027.8
XS Rating Curve= 0 ,0
Exp/Cntr=0.5,0.3

Type RM Length L Ch R = 1 ,225939.1,454,459.1,462.7
BEGIN DESCRIPTION:
Cross Section 225939.1-Interpolated
END DESCRIPTION:
XS GIS Cut Line= 4
      3052961.49     13908994.26      3052868.93     13908951.86
      3051729.07     13908858.08      3051559.49     13908845.15
#Sta/Elev= 26
  4385.8   126.5  4445.8   125.4  4487.6   125.2  4937.6     125  4937.8  125.01
  4954.6  126.13  4997.9  116.49  4998.8   115.4  4999.6  115.41  5001.2  115.75
  5002.1  116.43  5036.7  126.62  5117.6   126.7  5227.6   126.7  5257.6   127.8
  5297.6   127.1  5377.6   128.5  5497.6   127.9  5537.6   125.7  5557.6   125.7
  5587.6     128  5631.4   128.1  5681.4   128.7  5701.4   128.6  5741.4   129.1
  5801.4   129.1
#Mann= 4 , 1 , 0
  4385.8      .1       0  4937.8     .08       0  4954.6    .035       0
  5036.7     .08       0
#XS Ineff= 2 , 0
       0  4954.6  126.13  5497.6       0   127.9
Permanent Ineff=
       F       F
Bank Sta=4954.6,5036.7
XS Rating Curve= 0 ,0
Exp/Cntr=0.3,0.1