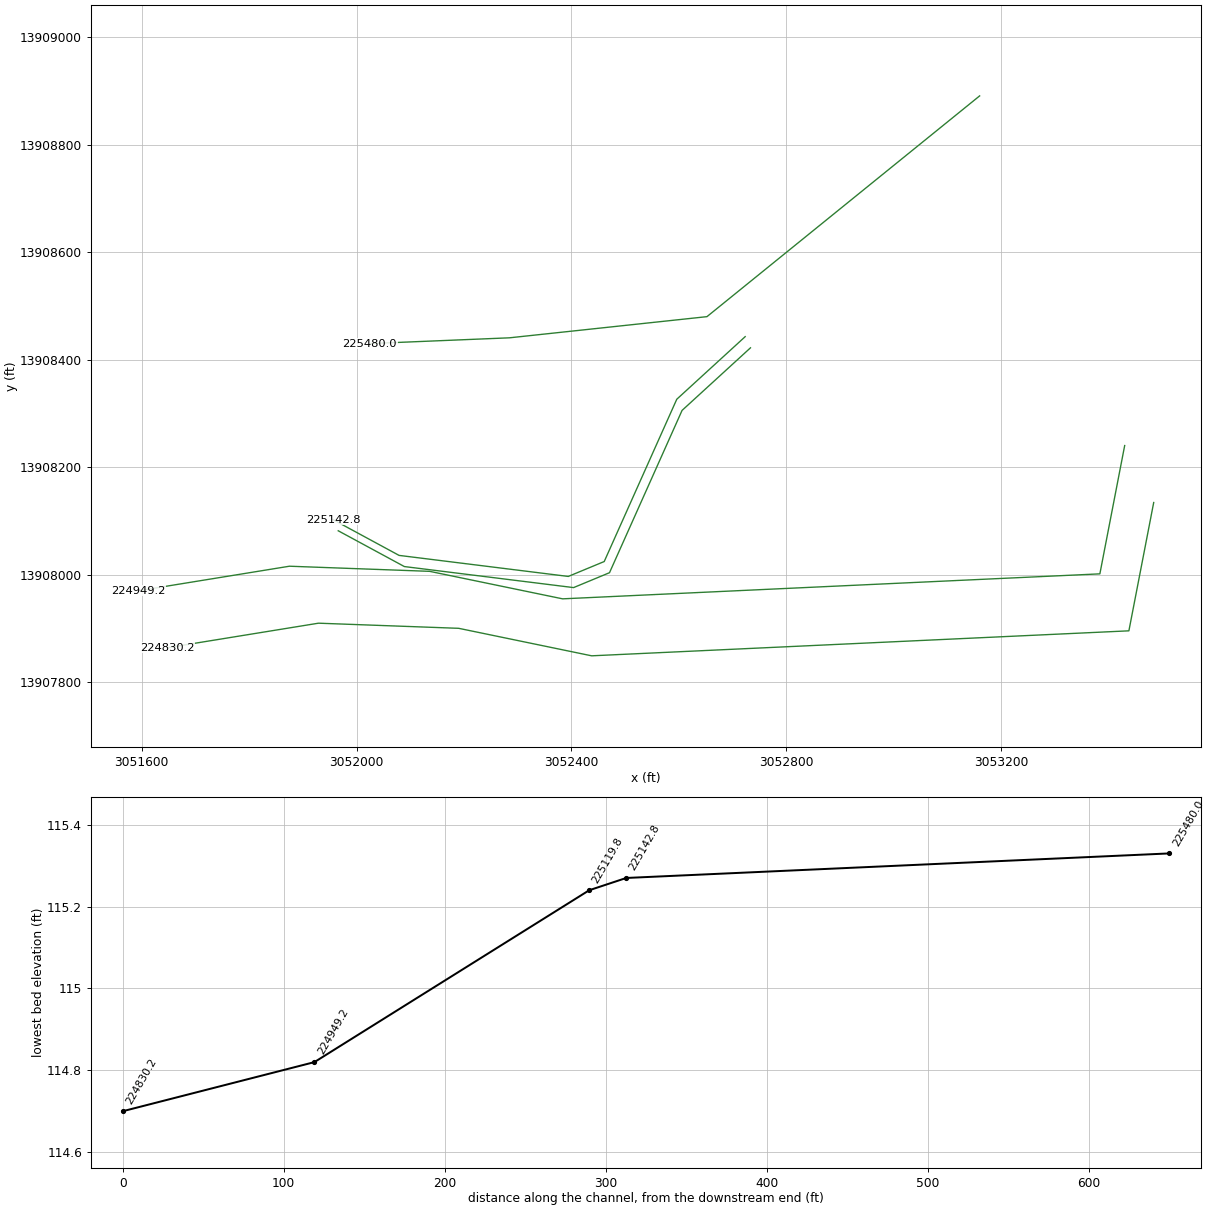
HEC-RAS study P100-00-00.prj: P100-00-00

--- P100-00-00.g01 (geometry) --- (continued)

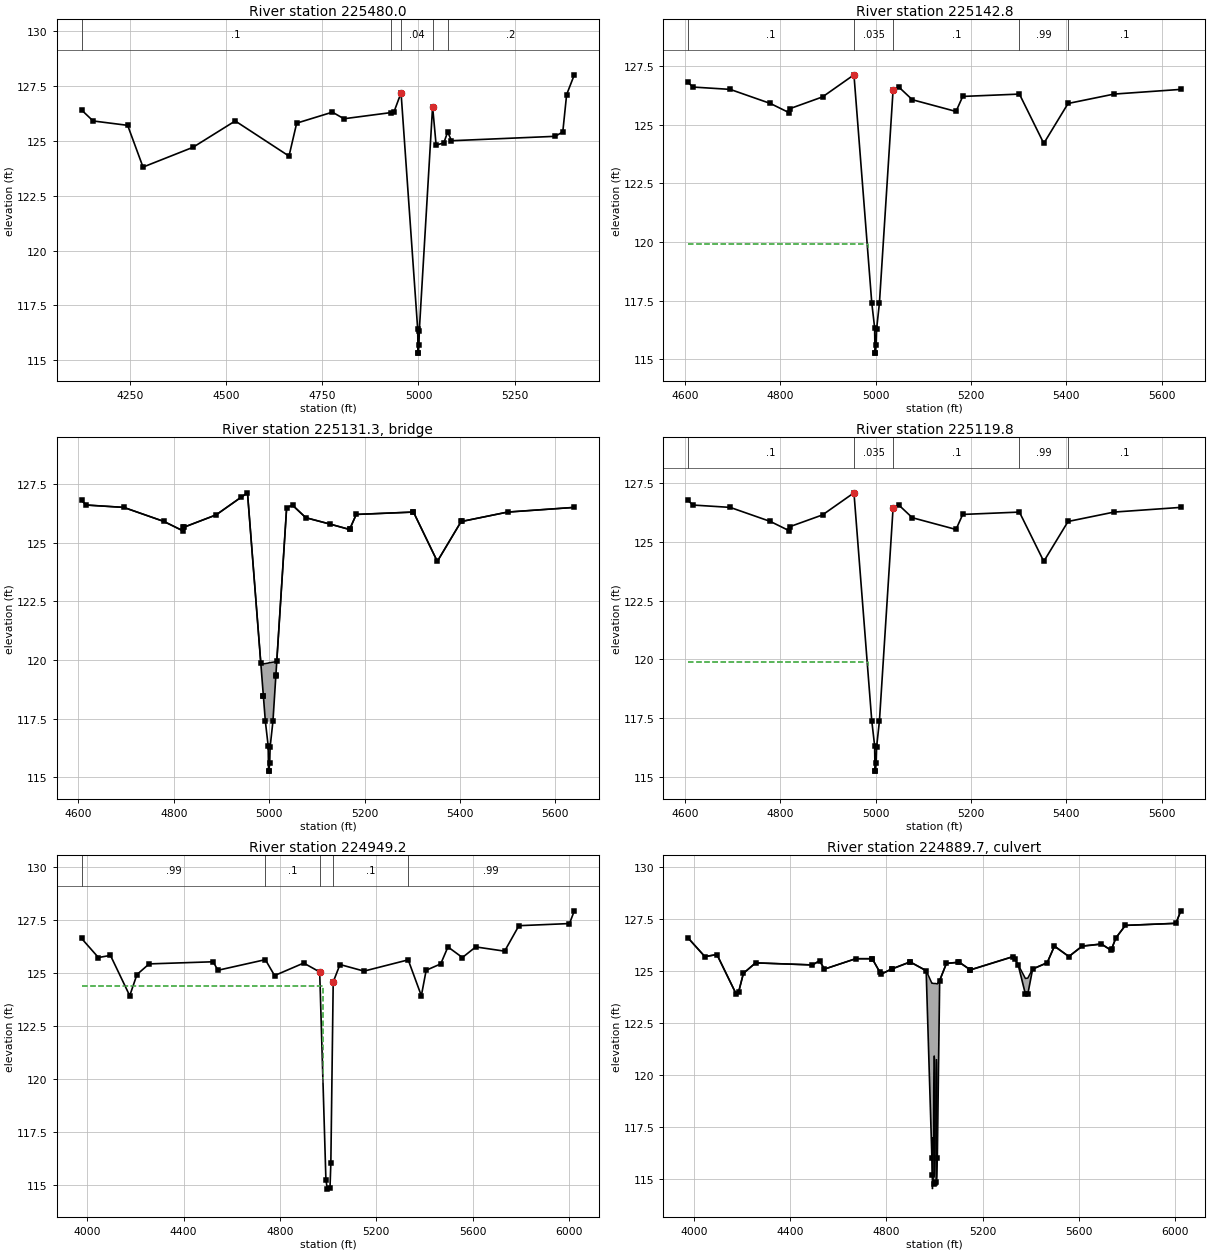
Type RM Length L Ch R = 1 ,225480.0,342.5,337.2,313.3
BEGIN DESCRIPTION:
Cross Section 225480.0-Interpolated
END DESCRIPTION:
XS GIS Cut Line= 4
      3053159.63     13908891.11       3052652.1     13908480.23
      3052284.48     13908440.84      3052024.72     13908430.08
#Sta/Elev= 27
  4122.9   126.4  4152.9   125.9  4242.9   125.7  4282.9   123.8  4412.9   124.7
  4522.9   125.9  4662.9   124.3  4682.9   125.8  4775.9   126.3  4805.9     126
    4928  126.28  4935.9   126.3  4954.6  127.18  4997.9  116.42  4998.8  115.33
  4999.6  115.34  5001.2  115.68  5002.1  116.36  5036.7  126.55  5045.9   124.8
  5065.9   124.9  5075.9   125.4  5085.9     125  5355.6   125.2  5375.6   125.4
  5385.6   127.1  5405.6     128
#Mann= 5 , 1 , 0
  4122.9      .1       0    4928     .08       0  4954.6     .04       0
  5036.7     .08       0  5075.9      .2       0
#XS Ineff= 2 , 0
       0  4775.9   126.3  5036.7       0  126.55
Permanent Ineff=
       F       F
Bank Sta=4954.6,5036.7
XS Rating Curve= 0 ,0
Exp/Cntr=0.5,0.3

Type RM Length L Ch R = 1 ,225142.8,23,23,23
BEGIN DESCRIPTION:
Upstream Section of Bridge/Culvert/Weir
END DESCRIPTION:
XS GIS Cut Line= 6
      3052723.27     13908442.99      3052595.94      13908326.5
      3052460.91     13908024.45      3052394.01     13907996.71
      3052079.09     13908035.87      3051956.01     13908102.49
#Sta/Elev= 25
  4606.6   126.8  4616.6   126.6    4695   126.5  4779.4   125.9  4819.4   125.5
  4820.3  125.68  4888.7  126.18  4954.6  127.12    4992   117.4  4997.9  116.36
  4998.8  115.27  4999.6  115.28  5001.2  115.62  5002.1   116.3    5008   117.4
  5036.7  126.49  5049.2  126.59    5077  126.06  5168.6  125.56  5182.7   126.2
  5301.6   126.3  5352.7   124.2  5403.6   125.9    5500   126.3    5640   126.5
#Mann= 5 , 1 , 0
  4606.6      .1       0  4954.6    .035       0  5036.7      .1       0
  5301.6     .99       0  5403.6      .1       0
#XS Ineff= 2 , 0
       0    4983   119.9    5017       0     120
Permanent Ineff=
       F       F
Bank Sta=4954.6,5036.7
XS Rating Curve= 0 ,0
Exp/Cntr=0.5,0.3

Type RM Length L Ch R = 3 ,225131.3,,,
BEGIN DESCRIPTION:
30" PIPELINE
Structure ID: PL1_P00-95
END DESCRIPTION:
Bridge Culvert--1,0,-1,-1, 0
Deck Dist Width WeirC Skew NumUp NumDn MinLoCord MaxHiCord MaxSubmerge Is_Ogee
10,3,2.6,0, 37, 37, , , 0.95, 0, 1,1,,
  4606.6  4616.6    4695  4779.4  4819.4  4820.3  4820.5  4888.7  4941.1  4954.6
  4982.5 4987.81  4987.9    4992  4997.9  4998.8  4999.6  5001.2  5002.1    5008
 5014.09  5014.2  5016.1  5036.7  5049.2    5077  5127.5  5168.6  5168.7  5182.7
  5301.6  5302.7  5352.7  5402.7  5403.6    5500    5640
   126.8   126.6   126.5   125.9   125.5  125.68  125.65  126.18  126.93  127.12
  119.88  119.84  119.84  119.85  119.87  119.88  119.88  119.89  119.89  119.91
  119.93  119.93  119.98  126.49  126.59  126.06  125.79  125.56  125.56   126.2
   126.3   126.3   124.2   125.9   125.9   126.3   126.5
   126.8   126.6   126.5   125.9   125.5  125.68  125.65  126.18  126.93  127.12
  119.87  118.49  118.47   117.4  117.37  117.38  117.38  117.39  117.39  117.41
  119.33  119.36  119.97  126.49  126.59  126.06  125.79  125.56  125.56   126.2
   126.3   126.3   124.2   125.9   125.9   126.3   126.5
  4606.6  4616.6    4695  4779.4  4819.4  4820.3  4820.5  4888.7  4941.1  4954.6
  4982.5 4987.81  4987.9    4992  4997.9  4998.8  4999.6  5001.2  5002.1    5008
 5014.09  5014.2  5016.1  5036.7  5049.2    5077  5127.5  5168.6  5168.7  5182.7
  5301.6  5302.7  5352.7  5402.7  5403.6    5500    5640
   126.8   126.6   126.5   125.9   125.5  125.68  125.65  126.18  126.93  127.12
  119.88  119.84  119.84  119.85  119.87  119.88  119.88  119.89  119.89  119.91
  119.93  119.93  119.98  126.49  126.59  126.06  125.79  125.56  125.56   126.2
   126.3   126.3   124.2   125.9   125.9   126.3   126.5
   126.8   126.6   126.5   125.9   125.5  125.68  125.65  126.18  126.93  127.12
  119.87  118.49  118.47   117.4  117.37  117.38  117.38  117.39  117.39  117.41
  119.33  119.36  119.97  126.49  126.59  126.06  125.79  125.56  125.56   126.2
   126.3   126.3   124.2   125.9   125.9   126.3   126.5
BR Coef= 1 , 1 , 0 ,1.25, 0 ,,,0.8,0,2,0,
WSPro=,,,, 1 ,,,, 0 ,,,, 0 ,,,,-1 ,-1 ,-1 , 0 , 0 , 0 , 0 , 0
BR U #Sta/Elev= 37
  4606.6   126.8  4616.6   126.6    4695   126.5  4779.4   125.9  4819.4   125.5
  4820.3  125.68  4820.5  125.65  4888.7  126.18  4941.1  126.93  4954.6  127.12
  4982.5  119.87 4987.81  118.49  4987.9  118.47    4992   117.4  4997.9  116.36
  4998.8  115.27  4999.6  115.28  5001.2  115.62  5002.1   116.3    5008   117.4
 5014.09  119.33  5014.2  119.36  5016.1  119.97  5036.7  126.49  5049.2  126.59
    5077  126.06  5127.5  125.79  5168.6  125.56  5168.7  125.56  5182.7   126.2
  5301.6   126.3  5302.7   126.3  5352.7   124.2  5402.7   125.9  5403.6   125.9
    5500   126.3    5640   126.5
BR U #Mann= 5
  4606.6      .1  4954.6     .04  5036.7      .1  5301.6     .99  5403.6      .1
BR U Banks=4954.6,5036.7
BR D #Sta/Elev= 37
  4606.6   126.8  4616.6   126.6    4695   126.5  4779.4   125.9  4819.4   125.5
  4820.3  125.68  4820.5  125.65  4888.7  126.18  4941.1  126.93  4954.6  127.12
  4982.5  119.87 4987.81  118.49  4987.9  118.47    4992   117.4  4997.9  116.36
  4998.8  115.27  4999.6  115.28  5001.2  115.62  5002.1   116.3    5008   117.4
 5014.09  119.33  5014.2  119.36  5016.1  119.97  5036.7  126.49  5049.2  126.59
    5077  126.06  5127.5  125.79  5168.6  125.56  5168.7  125.56  5182.7   126.2
  5301.6   126.3  5302.7   126.3  5352.7   124.2  5402.7   125.9  5403.6   125.9
    5500   126.3    5640   126.5
BR D #Mann= 5
  4606.6      .1  4954.6     .04  5036.7      .1  5301.6     .99  5403.6      .1
BR D Banks=4954.6,5036.7
BC Design=,, 0 ,, 0 ,,,,,,
BC HTab HWMax=127.12
BC Use User HTab Curves=0
BC User HTab FreeFlow(D)= 0

Type RM Length L Ch R = 1 ,225119.8,170.6,170.6,170.6
BEGIN DESCRIPTION:
Downstream Section of Bridge/Culvert/Weir
END DESCRIPTION:
XS GIS Cut Line= 6
      3052733.11      13908422.2      3052605.78     13908305.72
      3052470.75     13908003.67      3052403.85     13907975.93
      3052088.93     13908015.09      3051965.85      13908081.7
#Sta/Elev= 25
  4606.6  126.77  4616.6  126.57    4695  126.47  4779.4  125.87  4819.4  125.47
  4820.3  125.65  4888.7  126.15  4954.6  127.09    4992  117.37  4997.9  116.33
  4998.8  115.24  4999.6  115.25  5001.2  115.59  5002.1  116.27    5008  117.37
  5036.7  126.46  5049.2  126.56    5077  126.03  5168.6  125.53  5182.7  126.17
  5301.6  126.27  5352.7  124.17  5403.6  125.87    5500  126.27    5640  126.47
#Mann= 5 , 1 , 0
  4606.6      .1       0  4954.6    .035       0  5036.7      .1       0
  5301.6     .99       0  5403.6      .1       0
#XS Ineff= 2 , 0
       0    4983   119.9    5017       0     120
Permanent Ineff=
       F       F
Bank Sta=4954.6,5036.7
XS Rating Curve= 0 ,0
Exp/Cntr=0.5,0.3

Type RM Length L Ch R = 1 ,224949.2,119,119,119
BEGIN DESCRIPTION:
Upstream Section of Bridge/Culvert/Weir
END DESCRIPTION:
XS GIS Cut Line= 6
      3053429.61     13908240.32      3053383.43     13908001.52
      3052383.48     13907955.01      3052135.98     13908006.19
      3051875.05     13908015.73      3051594.01     13907970.06
#Sta/Elev= 30
  3976.4  126.63  4046.4  125.73  4096.4  125.83  4176.4  123.93  4206.4  124.93
    4257  125.43  4522.6  125.53  4542.6  125.13  4739.4  125.63  4777.7  124.88
  4898.6  125.47    4965  125.05  4990.8  115.26  4996.8  114.82  5007.8  114.89
  5011.3  116.05  5021.1  124.58  5049.2   125.4    5149  125.09  5332.4  125.62
    5387  123.93    5407  125.13  5467.4  125.43  5497.4  126.23  5557.4  125.73
  5612.7  126.23  5732.7  126.03    5792  127.23    6002  127.33    6022  127.93
#Mann= 5 , 1 , 0
  3976.4     .99       0  4739.4      .1       0    4965    .035       0
  5021.1      .1       0  5332.4     .99       0
#XS Ineff= 2 , 0
       0    4979   124.4    5021       0   124.4
Permanent Ineff=
       F       F
Bank Sta=4965,5021.1
XS Rating Curve= 0 ,0
Exp/Cntr=0.5,0.3

Type RM Length L Ch R = 2 ,224889.7,,,
BEGIN DESCRIPTION:
GREEN CREEK DRIVE
Structure ID: P00-94
END DESCRIPTION:
Bridge Culvert--1,0,-1,-1, 0
Deck Dist Width WeirC Skew NumUp NumDn MinLoCord MaxHiCord MaxSubmerge Is_Ogee
10,99,3,0, 49, 49, , , 0.95, 0, 1,1,,
  3976.4  4046.4  4096.4  4176.4  4186.4  4206.4    4257  4492.6  4522.6  4542.6
  4672.6  4739.4  4741.1  4772.2  4777.7  4821.5  4822.2  4896.1  4898.6    4965
  4988.8  4990.8  4996.8  5003.3  5007.8  5011.3  5021.1  5049.2  5096.8  5101.7
  5148.5    5149    5327  5332.4    5347    5377    5387    5407  5467.4  5497.4
  5557.4  5612.7  5692.7  5732.7  5735.1  5752.7    5792    6002    6022
   126.6   125.7   125.8   123.9     124   124.9   125.4   125.3   125.5   125.1
   125.6   125.6   125.6  124.97  124.86  125.11  125.11  125.44  125.45  125.03
  124.42  124.42  124.41  124.41   124.4  124.39  124.56  125.38  125.43  125.44
  125.07  125.07  125.71   125.6  125.31  124.65  124.67  125.11  125.41  126.21
  125.71  126.21  126.31  126.01  126.08   126.6   127.2   127.3   127.9
   126.6   125.7   125.8   123.9     124   124.9   125.4   125.3   125.5   125.1
   125.6   125.6   125.6  124.96  124.85   125.1   125.1  125.43  125.44  125.02
  116.04  115.23  114.79  114.83  114.86  116.02  124.55  125.37  125.42  125.43
  125.06  125.06   125.7  125.59   125.3   123.9   123.9   125.1   125.4   126.2
   125.7   126.2   126.3     126  126.07   126.6   127.2   127.3   127.9
  3976.4  4046.4  4096.4  4176.4  4186.4  4206.4    4257  4492.6  4522.6  4542.6
  4672.6  4739.4  4741.1  4772.2  4777.7  4821.5  4822.2  4896.1  4898.6    4965
  4988.8  4990.8  4996.8  5003.3  5007.8  5011.3  5021.1  5049.2  5096.8  5101.7
  5148.5    5149    5327  5332.4    5347    5377    5387    5407  5467.4  5497.4
  5557.4  5612.7  5692.7  5732.7  5735.1  5752.7    5792    6002    6022
   126.6   125.7   125.8   123.9     124   124.9   125.4   125.3   125.5   125.1
   125.6   125.6   125.6  124.97  124.86  125.11  125.11  125.44  125.45  125.03
  124.42  124.42  124.41  124.41   124.4  124.39  124.56  125.38  125.43  125.44
  125.07  125.07  125.71   125.6  125.31  124.65  124.67  125.11  125.41  126.21
  125.71  126.21  126.31  126.01  126.08   126.6   127.2   127.3   127.9
  126.52  125.62  125.72  123.82  123.92  124.82  125.32  125.22  125.42  125.02
  125.52  125.52  125.52  124.88  124.77  125.02  125.02  125.35  125.36  124.94
  115.96  115.15  114.71  114.75  114.78  115.94  124.47  125.29  125.34  125.35
  124.98  124.98  125.62  125.51  125.22  123.82  123.82  125.02  125.32  126.12
  125.62  126.12  126.22  125.92  125.99  126.52  127.12  127.22  127.82
BR Coef= 1 , 0 , 0 ,1.25, 0 ,,,0.8,-1,2,0,
WSPro=,,,, 1 ,,,, 0 ,,,, 0 ,,,,-1 ,-1 ,-1 , 0 , 0 , 0 , 0 , 0
Culvert=1,2.5,,99,0.015,0.5,1,1,3,114.53,4991.2,114.5,4991.2,Culvert #1  , 0 ,10
  4991.2  4991.2
BC Culvert Barrel=1,,0
Culvert Bottom n=0.015
Culvert=1,5.8,,99,0.024,0.9,1,1,3,115.14,4998.7,115.11,4998.7,Culvert #2  , 0 ,10
  4998.7  4998.7
BC Culvert Barrel=1,,0
Culvert Bottom n=0.024
Culvert=1,5.8,,99,0.024,0.9,1,1,3,114.97,5007.7,114.94,5007.7,Culvert #3  , 0 ,10
  5007.7  5007.7
BC Culvert Barrel=1,,0
Culvert Bottom n=0.024
BR U #Sta/Elev= 49
  3976.4   126.6  4046.4   125.7  4096.4   125.8  4176.4   123.9  4186.4     124
  4206.4   124.9    4257   125.4  4492.6   125.3  4522.6   125.5  4542.6   125.1
  4672.6   125.6  4739.4   125.6  4741.1   125.6  4772.2  124.96  4777.7  124.85
  4821.5   125.1  4822.2   125.1  4896.1  125.43  4898.6  125.44    4965  125.02
  4988.8  116.04  4990.8  115.23  4996.8  114.79  5003.3  114.83  5007.8  114.86
  5011.3  116.02  5021.1  124.55  5049.2  125.37  5096.8  125.42  5101.7  125.43
  5148.5  125.06    5149  125.06    5327   125.7  5332.4  125.59    5347   125.3
    5377   123.9    5387   123.9    5407   125.1  5467.4   125.4  5497.4   126.2
  5557.4   125.7  5612.7   126.2  5692.7   126.3  5732.7     126  5735.1  126.07
  5752.7   126.6    5792   127.2    6002   127.3    6022   127.9
BR U #Mann= 5
  3976.4     .99  4739.4      .1    4965    .035  5021.1      .1  5332.4     .99
BR U Banks=4965,5021.1
BR D #Sta/Elev= 49
  3976.4  126.52  4046.4  125.62  4096.4  125.72  4176.4  123.82  4186.4  123.92
  4206.4  124.82    4257  125.32  4492.6  125.22  4522.6  125.42  4542.6  125.02
  4672.6  125.52  4739.4  125.52  4741.1  125.52  4772.2  124.88  4777.7  124.77
  4821.5  125.02  4822.2  125.02  4896.1  125.35  4898.6  125.36    4965  124.94
  4988.8  115.96  4990.8  115.15  4996.8  114.71  5003.3  114.75  5007.8  114.78
  5011.3  115.94  5021.1  124.47  5049.2  125.29  5096.8  125.34  5101.7  125.35
  5148.5  124.98    5149  124.98    5327  125.62  5332.4  125.51    5347  125.22
    5377  123.82    5387  123.82    5407  125.02  5467.4  125.32  5497.4  126.12
  5557.4  125.62  5612.7  126.12  5692.7  126.22  5732.7  125.92  5735.1  125.99
  5752.7  126.52    5792  127.12    6002  127.22    6022  127.82
BR D #Mann= 5
  3976.4     .99  4739.4      .1    4965    .035  5021.1      .1  5332.4     .99
BR D Banks=4965,5021.1
BC Design=,, 0 ,, 0 ,,,,,,
BC HTab HWMax=127.93
BC Use User HTab Curves=0
BC User HTab FreeFlow(D)= 0

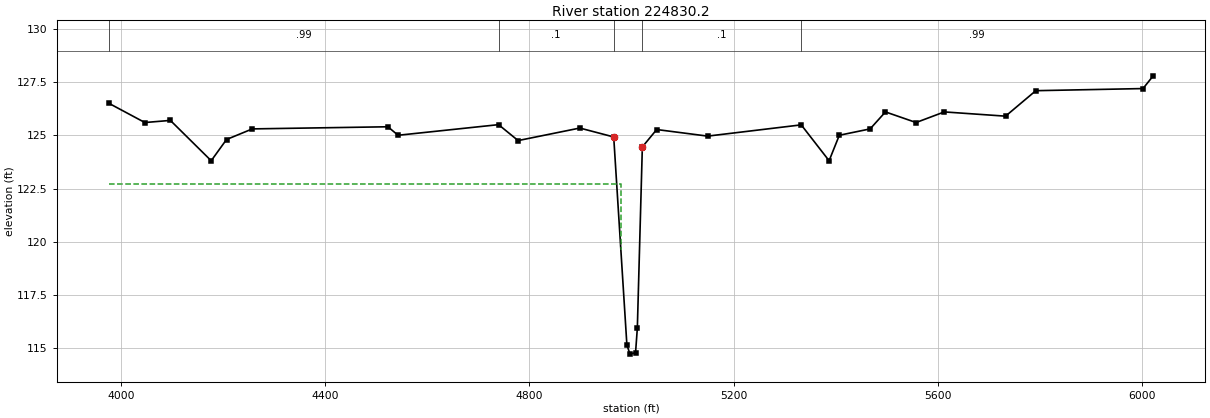
Type RM Length L Ch R = 1 ,224830.2,521.8,521.8,521.8
BEGIN DESCRIPTION:
Downstream Section of Bridge/Culvert/Weir
END DESCRIPTION:
XS GIS Cut Line= 6
      3053483.63     13908134.29      3053437.45     13907895.48
       3052437.5     13907848.97        3052190.     13907900.15
      3051929.07     13907909.69      3051648.03     13907864.03
#Sta/Elev= 30
  3976.4  126.51  4046.4  125.61  4096.4  125.71  4176.4  123.81  4206.4  124.81
    4257  125.31  4522.6  125.41  4542.6  125.01  4739.4  125.51  4777.7  124.76
  4898.6  125.35    4965  124.93  4990.8  115.14  4996.8   114.7  5007.8  114.77
  5011.3  115.93  5021.1  124.46  5049.2  125.28    5149  124.97  5332.4   125.5
    5387  123.81    5407  125.01  5467.4  125.31  5497.4  126.11  5557.4  125.61
  5612.7  126.11  5732.7  125.91    5792  127.11    6002  127.21    6022  127.81
#Mann= 5 , 1 , 0
  3976.4     .99       0  4739.4      .1       0    4965    .035       0
  5021.1      .1       0  5332.4     .99       0
#XS Ineff= 2 , 0
       0    4979   122.7    5021       0   122.7
Permanent Ineff=
       F       F
Bank Sta=4965,5021.1
XS Rating Curve= 0 ,0
Exp/Cntr=0.5,0.3