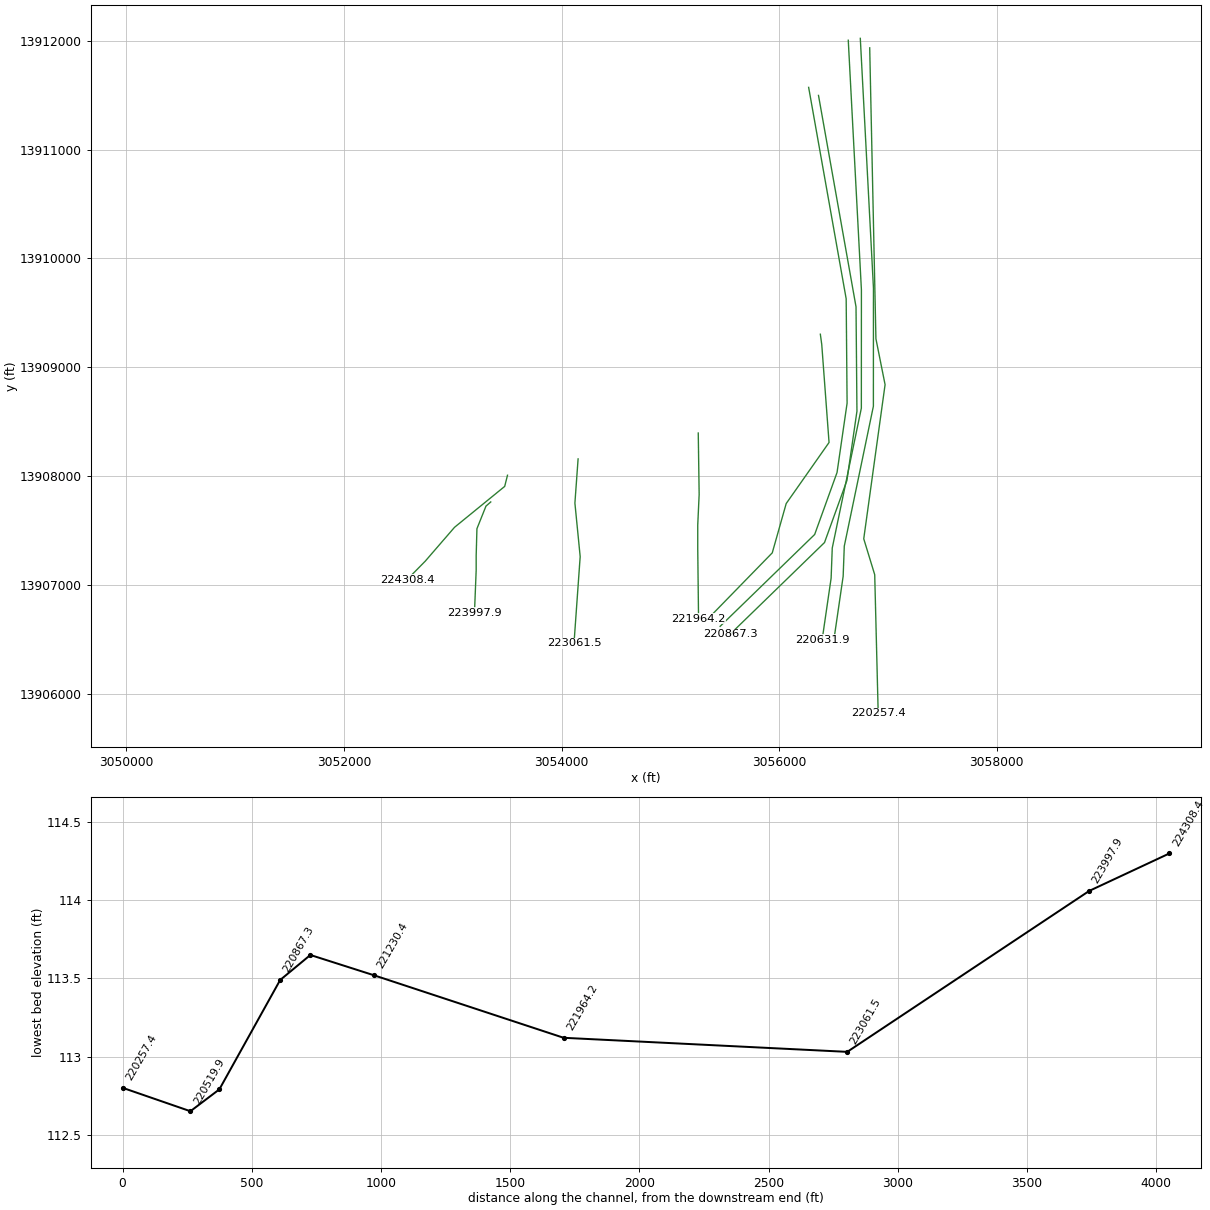
HEC-RAS study P100-00-00.prj: P100-00-00

--- P100-00-00.g01 (geometry) --- (continued)

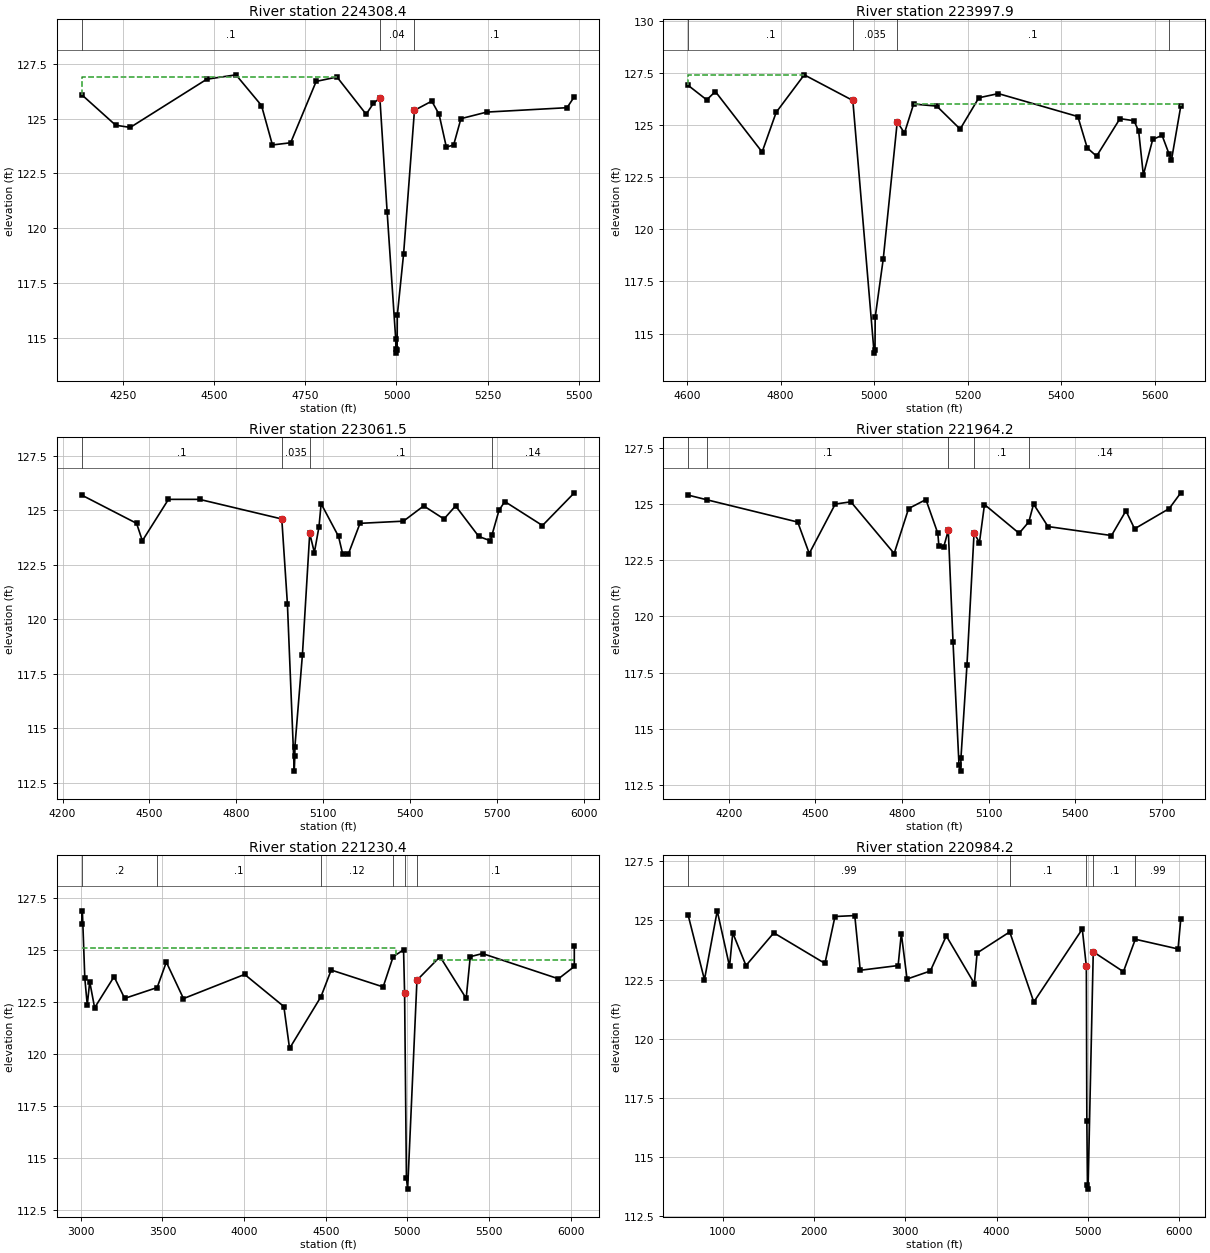
Type RM Length L Ch R = 1 ,224308.4,205.9,310.5,373.3
BEGIN DESCRIPTION:
Cross Section 224308.4-Interpolated
END DESCRIPTION:
XS GIS Cut Line= 5
      3053502.39     13908006.91      3053476.62     13907904.34
      3053015.52     13907528.36      3052746.63     13907217.46
      3052578.31     13907046.47
#Sta/Elev= 29
  4136.1   126.1  4229.7   124.7  4269.7   124.6  4479.7   126.8  4559.7     127
  4629.7   125.6  4659.7   123.8  4709.7   123.9  4779.7   126.7  4836.8   126.9
  4916.8   125.2  4936.8   125.7  4954.4  125.94  4974.3  120.76  4997.9  114.93
  4998.4  114.49  4999.9   114.3  5001.8  114.46  5002.2  116.02  5019.5  118.83
  5049.3  125.38  5096.8   125.8  5116.8   125.2  5136.8   123.7  5156.8   123.8
  5176.8     125  5247.8   125.3  5467.8   125.5  5487.8     126
#Mann= 3 , 1 , 0
  4136.1      .1       0  4954.4     .04       0  5049.3      .1       0
#XS Ineff= 2 , 0
       0  4836.8   126.9  5096.8       0   125.8
Permanent Ineff=
       F       F
Bank Sta=4954.4,5049.3
XS Rating Curve= 0 ,0
Exp/Cntr=0.3,0.1

Type RM Length L Ch R = 1 ,223997.9,927.4,936.4,949.1
BEGIN DESCRIPTION:
Cross Section 223997.9
END DESCRIPTION:
XS GIS Cut Line= 6
      3053348.55     13907761.58      3053304.54     13907723.21
      3053221.42      13907515.4      3053214.49     13907266.02
      3053214.49      13907134.4      3053198.93     13906744.71
#Sta/Elev= 30
  4602.1   126.9  4642.1   126.2  4660.5   126.6  4760.5   123.7  4790.5   125.6
  4850.5   127.4  4954.4  126.17  4999.9  114.06  5001.8  114.22  5002.2  115.78
  5019.5  118.59  5049.3  125.14  5064.8  124.61  5084.3     126  5133.8   125.9
  5183.8   124.8  5223.8   126.3  5265.4   126.5  5435.4   125.4  5455.4   123.9
  5475.4   123.5  5525.4   125.3  5555.4   125.2  5565.4   124.7  5575.4   122.6
  5595.4   124.3  5615.4   124.5  5630.6  123.59  5635.4   123.3  5655.4   125.9
#Mann= 4 , 1 , 0
  4602.1      .1       0  4954.4    .035       0  5049.3      .1       0
  5630.6     .14       0
#XS Ineff= 2 , 0
       0  4850.5   127.4  5084.3       0     126
Permanent Ineff=
       F       F
Bank Sta=4954.4,5049.3
XS Rating Curve= 0 ,0
Exp/Cntr=0.3,0.1

Type RM Length L Ch R = 1 ,223061.5,1104.5,1097.3,1086.1
BEGIN DESCRIPTION:
Cross Section 223061.5
END DESCRIPTION:
XS GIS Cut Line= 4
      3054151.28      13908157.1      3054121.95     13907750.92
      3054170.44     13907259.09      3054113.52     13906461.07
#Sta/Elev= 30
  4265.4   125.7  4455.4   124.4  4475.4   123.6  4565.4   125.5  4672.7   125.5
  4956.8   124.6  4976.2  120.71  4999.8  113.03  5001.9  113.72  5002.1  114.15
  5028.1  118.38  5053.3  123.94  5069.3  123.06  5085.2  124.24  5092.7   125.3
  5152.7   123.8  5166.9     123  5186.9     123  5226.9   124.4  5376.9   124.5
  5446.9   125.2  5516.9   124.6  5556.9   125.2  5636.9   123.8  5676.9   123.6
  5682.3  123.85  5706.9     125  5726.9   125.4  5856.9   124.3  5966.9   125.8
#Mann= 4 , 1 , 0
  4265.4      .1       0  4956.8    .035       0  5053.3      .1       0
  5682.3     .14       0
#XS Ineff= 2 , 0
       0  4565.4   125.5  5092.7       0   125.3
Permanent Ineff=
       F       F
Bank Sta=4956.8,5053.3
XS Rating Curve= 0 ,0
Exp/Cntr=0.3,0.1

Type RM Length L Ch R = 1 ,221964.2,773.6,733.8,702.4
BEGIN DESCRIPTION:
Cross Section 221964.2
END DESCRIPTION:
XS GIS Cut Line= 5
      3055255.75     13908394.94      3055264.02     13907830.95
      3055251.07     13907550.03      3055251.07     13907328.36
      3055258.46     13906688.34
#Sta/Elev= 30
  4058.4   125.4  4123.8  125.19  4438.4   124.2  4478.4   122.8  4568.4     125
  4622.5   125.1  4772.5   122.8  4822.5   124.8  4882.5   125.2  4923.7   123.7
  4927.5  123.13  4943.7  123.07    4960  123.83  4976.4  118.87  4997.1   113.4
    5003  113.12  5003.9  113.71  5024.6  117.82  5049.3  123.71    5068  123.29
  5085.4  124.98  5205.4   123.7  5239.1  124.21  5255.4     125  5305.4     124
  5525.4   123.6  5575.4   124.7  5605.4   123.9  5725.4   124.8  5765.4   125.5
#Mann= 5 , 1 , 0
  4058.4      .2       0  4123.8      .1       0    4960    .035       0
  5049.3      .1       0  5239.1     .14       0
#XS Ineff= 2 , 0
       0  4882.5   125.2  5085.4       0  124.98
Permanent Ineff=
       F       F
Bank Sta=4960,5049.3
XS Rating Curve= 0 ,0
Exp/Cntr=0.3,0.1

Type RM Length L Ch R = 1 ,221230.4,377.7,246.25,189.7
BEGIN DESCRIPTION:
Cross Section 221230.4-Interpolated
END DESCRIPTION:
XS GIS Cut Line= 6
      3056377.89     13909303.28      3056390.75     13909210.07
      3056457.93     13908307.91      3056064.05     13907746.63
      3055936.04     13907293.68      3055334.22     13906676.52
#Sta/Elev= 30
  3004.6  126.25  3009.6  126.87  3024.6  123.63  3039.6  122.35  3054.6  123.47
  3084.6  122.22  3203.7  123.71  3268.7  122.67  3467.6  123.19  3523.7  124.41
  3628.7  122.66  4003.3  123.82  4243.3  122.28  4278.3  120.27  4470.6  122.75
  4533.3  124.03  4851.4  123.22  4912.7  124.67  4976.4     125  4982.7  122.92
    4994  114.03  5001.4  113.52  5058.4  123.54  5199.8  124.67  5359.8  122.67
  5384.8  124.67  5459.8  124.82  5924.8  123.61  6021.9   124.2    6022   125.2
#Mann= 6 , 1 , 0
  3004.6      .2       0  3467.6      .1       0  4470.6     .12       0
  4912.7      .1       0  4982.7     .04       0  5058.4      .1       0
#XS Ineff= 2 , 0
       0  4931.5   125.1  5159.9       0   124.5
Permanent Ineff=
       F       F
Bank Sta=4982.7,5058.4
XS Rating Curve= 0 ,0
Exp/Cntr=0.5,0.3

Type RM Length L Ch R = 1 ,220984.2,116.9,116.9,116.9
BEGIN DESCRIPTION:
Upstream Section of Bridge/Culvert/Weir
END DESCRIPTION:
XS GIS Cut Line= 6
      3056270.39     13911572.06      3056615.32     13909628.91
      3056623.79      13908669.4      3056531.45      13908032.2
      3056325.76     13907462.39      3055456.75     13906618.06
#Sta/Elev= 30
   618.5  125.24   798.5  122.49   938.5   125.4  1073.5  123.05  1108.5  124.47
  1253.5  123.09  1558.5  124.47  2118.5  123.18  2228.5  125.16  2445.4   125.2
  2505.4  122.89  2920.4  123.09  2955.4  124.44  3018.3  122.52  3273.3  122.86
  3448.3  124.34  3755.8  122.33  3785.8  123.62  4143.2  124.51  4406.8  121.55
  4938.3  124.63  4982.7  123.05  4988.2  116.54  4994.8  113.82  5001.4  113.65
  5058.4  123.67  5388.8  122.83  5519.2   124.2  5987.3  123.79  6017.3  125.05
#Mann= 5 , 1 , 0
   618.5     .99       0  4143.2      .1       0  4982.7    .035       0
  5058.4      .1       0  5519.2     .99       0
#XS Ineff= 2 , 0
       0    4967   123.6    5059       0   123.3
Permanent Ineff=
       F       F
Bank Sta=4982.7,5058.4
XS Rating Curve= 0 ,0
Exp/Cntr=0.5,0.3

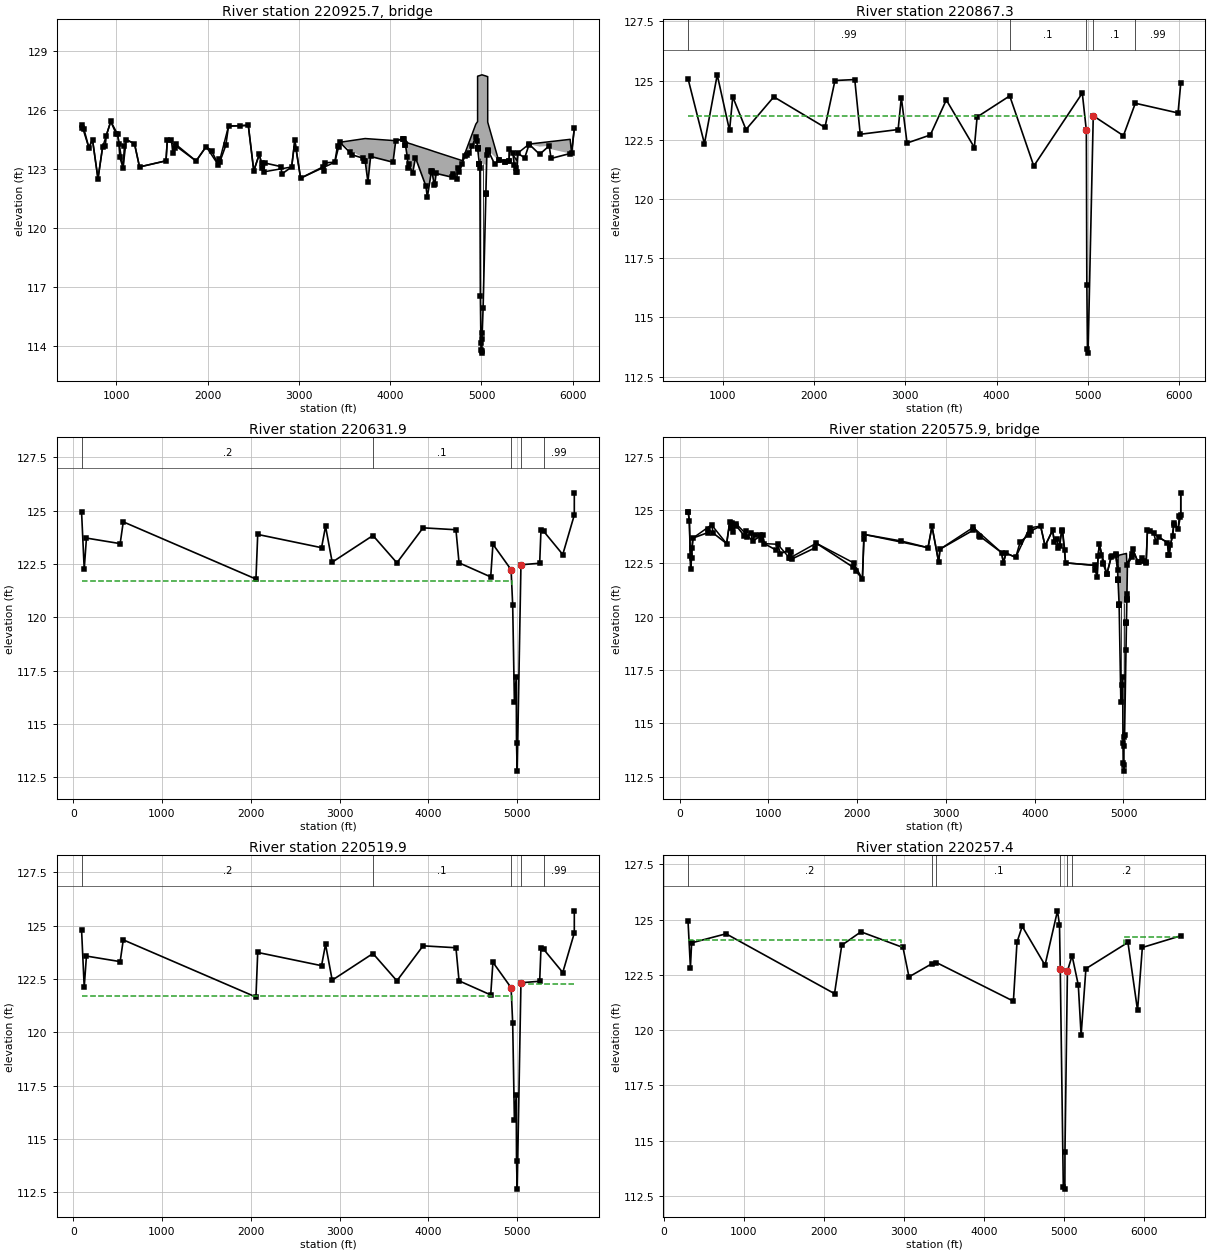
Type RM Length L Ch R = 3 ,220925.7,,,
BEGIN DESCRIPTION:
F.M. 1960 W.
Structure ID: P00-93
END DESCRIPTION:
Bridge Culvert--1,0,-1,-1, 0
Deck Dist Width WeirC Skew NumUp NumDn MinLoCord MaxHiCord MaxSubmerge Is_Ogee
10,96.9,2.6,0, 60, 60, , , 0.95, 0, 1,1,,
   618.5   698.5   738.5   798.5   848.5   938.5  1013.5  1073.5  1108.5  1198.5
  1253.5  1543.5  1558.5  1873.5  1983.5  2118.5  2228.5  2445.4  2505.4  2565.4
  2615.4  2920.4  2955.4  3018.3  3393.3  3448.3  3725.8  3755.8  3785.8  4030.8
  4060.8  4150.8  4196.8  4246.8  4276.8  4406.8  4451.8  4483.3  4503.3  4729.8
  4789.1  4938.3 4957.59  4957.7  5005.9 5048.29  5048.4  5058.4  5068.4 5068.51
  5071.1  5187.2    5303    5306  5388.8  5398.8  5522.3  5971.7  5987.3  6017.3
  125.25  124.08  124.48   122.5  124.09  125.41  124.76  123.06  124.48  124.28
   123.1  123.41  124.48   123.4  124.13  123.19  125.17  125.21   122.9  123.74
  122.85   123.1  124.45  122.53  123.34  124.35  124.54  124.53  124.52  124.44
  124.43  124.54  124.31  124.24  124.19     124  123.93  123.88  123.85  123.51
  123.42  125.27   125.4   127.7  127.77  127.71  127.71  127.69  127.68  125.38
  125.33  123.44  123.43     124  123.41   123.8  124.26   124.5   123.8  125.06
  125.25  124.08  124.48   122.5  124.09  125.41  124.76  123.06  124.48  124.28
   123.1  123.41  124.48   123.4  124.13  123.19  125.17  125.21   122.9  123.74
  122.85   123.1  124.45  122.53  123.34  124.35  123.41  122.34  123.63  123.34
  124.43  124.53  123.05  122.81  123.57  121.56  122.88   122.2  122.77  122.51
  123.27  124.64  124.05  124.04  123.27  123.21  121.76  123.68  123.89  123.89
  123.95  123.43  123.42  123.99  122.84  123.79  124.25  123.78   123.8  125.06
   618.5   698.5   738.5   798.5   848.5   938.5  1013.5  1073.5  1108.5  1198.5
  1253.5  1543.5  1558.5  1873.5  1983.5  2118.5  2228.5  2445.4  2505.4  2565.4
  2615.4  2920.4  2955.4  3018.3  3393.3  3448.3  3725.8  3755.8  3785.8  4030.8
  4060.8  4150.8  4196.8  4246.8  4276.8  4406.8  4451.8  4483.3  4503.3  4729.8
  4789.1  4938.3 4957.59  4957.7  5005.9 5048.29  5048.4  5058.4  5068.4 5068.51
  5071.1  5187.2    5303    5306  5388.8  5398.8  5522.3  5971.7  5987.3  6017.3
  125.25  124.08  124.48   122.5  124.09  125.41  124.76  123.06  124.48  124.28
   123.1  123.41  124.48   123.4  124.13  123.19  125.17  125.21   122.9  123.74
  122.85   123.1  124.45  122.53  123.34  124.35  124.54  124.53  124.52  124.44
  124.43  124.54  124.31  124.24  124.19     124  123.93  123.88  123.85  123.51
  123.42  125.27   125.4   127.7  127.77  127.71  127.71  127.69  127.68  125.38
  125.33  123.44  123.43     124  123.41   123.8  124.26   124.5   123.8  125.06
  125.11  123.94  124.34  122.36  123.95  125.27  124.62  122.92  124.34  124.14
  122.96  123.27  124.34  123.26  123.99  123.05  125.03  125.07  122.76   123.6
  122.71  122.96  124.31  122.39   123.2  124.21  123.27   122.2  123.49   123.2
  124.29  124.39  122.91  122.67  123.43  121.42  122.74  122.06  122.63  122.37
  123.13   124.5  123.91   123.9  123.13  123.07  121.62  123.54  123.75  123.75
  123.81  123.29  123.28  123.85   122.7  123.65  124.11  123.64  123.66  124.92
Pier Skew, UpSta & Num, DnSta & Num=  ,4988.2, 2 ,4988.2, 2 , 0 , 0 , 0 ,,
     1.4     1.4
  115.26  124.24
     1.4     1.4
  115.12   124.1
Pier Skew, UpSta & Num, DnSta & Num=  ,5018.2, 2 ,5018.2, 2 , 0 , 0 , 0 ,,
     1.4     1.4
  114.88  124.26
     1.4     1.4
  114.74  124.12
BR Coef= 1 , 1 , 0 ,1.25, 0 ,,,0.8,-1,2,0,
WSPro=,,,, 1 ,,,, 0 ,,,, 0 ,,,,-1 ,-1 ,-1 , 0 , 0 , 0 , 0 , 0
BR U #Sta/Elev= 143
   618.5  125.25   628.5  125.05   643.5  125.03   698.5  124.08   738.5  124.48
   798.5   122.5   848.5  124.09   878.5  124.17   888.5  124.68   938.5  125.41
   998.5  124.77  1013.5  124.76  1028.5  124.24  1038.5  123.58  1073.5  123.06
  1088.5  124.16  1108.5  124.48  1198.5  124.28  1253.5   123.1  1543.5  123.41
  1558.5  124.48  1603.5  124.47  1618.5   123.8  1643.5  124.06  1648.5  124.25
  1873.5   123.4  1983.5  124.13  2043.5  123.92  2118.5  123.19  2123.5   123.5
  2133.5  123.36  2198.5  124.19  2228.5  125.17  2355.4  125.19  2445.4  125.21
  2505.4   122.9  2565.4  123.74  2590.4  123.28  2595.4  123.06  2615.4  122.85
  2625.4   123.3  2800.4  123.12  2815.4  122.75  2920.4   123.1  2955.4  124.45
  2968.3     124  3018.3  122.53  3263.3   123.1  3273.3  122.87  3288.3  123.31
  3393.3  123.34  3423.3  124.18  3438.3  124.11  3448.3  124.35  3556.4  123.85
  3585.8  123.71  3705.8  123.54  3710.8  123.39  3725.8  123.41  3755.8  122.34
  3785.8  123.63  4030.8  123.34  4060.8  124.43  4138.7  124.52  4143.2  124.52
  4150.8  124.53  4160.8  124.19  4166.8  124.23  4186.8  123.62  4196.8  123.05
  4201.8  123.23  4246.8  122.81  4276.8  123.57  4391.8  122.12  4406.8  121.56
  4451.8  122.88  4456.8  122.87  4458.3  122.83  4483.3   122.2  4488.3  122.21
  4503.3  122.77  4678.3  122.58  4683.3  122.73  4689.8  122.63  4729.8  122.51
  4739.8  123.07  4757.8  122.83  4789.1  123.27  4816.9  123.66  4842.4  123.73
  4868.5  123.81  4899.4  124.18  4938.3  124.64  4948.8  124.39  4957.5  124.05
 4957.59  124.05  4957.7  124.04 4957.81  124.04  4957.9  124.03 4977.81  123.25
  4977.9  123.25    4978  123.24  4982.7  123.06  4988.2  116.55    4994  114.17
  4994.8  113.83  5001.4  113.66  5004.6  113.78  5005.9  114.39  5008.3   114.7
  5018.2  115.97  5048.2  121.72 5048.29  121.74  5048.4  121.76  5058.4  123.68
 5068.29  123.89  5068.4  123.89 5068.51  123.89  5068.7   123.9  5071.1  123.95
  5146.3  123.23  5187.2  123.43  5188.9  123.44  5253.7  123.34  5256.3  123.34
  5302.9  123.42    5303  123.42    5306  123.99  5343.8  123.81  5358.8   123.2
  5378.8  123.04  5383.8  122.85  5388.8  122.84  5398.8  123.79  5473.8  123.56
  5519.2  124.21  5522.3  124.25  5637.3  123.74  5742.3  124.17  5762.3  123.53
  5971.7  123.78  5987.3   123.8  6017.3  125.06
BR U #Mann= 5
   618.5     .99  4143.2      .1  4982.7    .035  5058.4      .1  5519.2     .99
BR U Banks=4982.7,5058.4
BR D #Sta/Elev= 143
   618.5  125.11   628.5  124.91   643.5  124.89   698.5  123.94   738.5  124.34
   798.5  122.36   848.5  123.95   878.5  124.03   888.5  124.54   938.5  125.27
   998.5  124.63  1013.5  124.62  1028.5   124.1  1038.5  123.44  1073.5  122.92
  1088.5  124.02  1108.5  124.34  1198.5  124.14  1253.5  122.96  1543.5  123.27
  1558.5  124.34  1603.5  124.33  1618.5  123.66  1643.5  123.92  1648.5  124.11
  1873.5  123.26  1983.5  123.99  2043.5  123.78  2118.5  123.05  2123.5  123.36
  2133.5  123.22  2198.5  124.05  2228.5  125.03  2355.4  125.05  2445.4  125.07
  2505.4  122.76  2565.4   123.6  2590.4  123.14  2595.4  122.92  2615.4  122.71
  2625.4  123.16  2800.4  122.98  2815.4  122.61  2920.4  122.96  2955.4  124.31
  2968.3  123.86  3018.3  122.39  3263.3  122.96  3273.3  122.73  3288.3  123.17
  3393.3   123.2  3423.3  124.04  3438.3  123.97  3448.3  124.21  3556.4  123.71
  3585.8  123.57  3705.8   123.4  3710.8  123.25  3725.8  123.27  3755.8   122.2
  3785.8  123.49  4030.8   123.2  4060.8  124.29  4138.7  124.38  4143.2  124.38
  4150.8  124.39  4160.8  124.05  4166.8  124.09  4186.8  123.48  4196.8  122.91
  4201.8  123.09  4246.8  122.67  4276.8  123.43  4391.8  121.98  4406.8  121.42
  4451.8  122.74  4456.8  122.73  4458.3  122.69  4483.3  122.06  4488.3  122.07
  4503.3  122.63  4678.3  122.44  4683.3  122.59  4689.8  122.49  4729.8  122.37
  4739.8  122.93  4757.8  122.69  4789.1  123.13  4816.9  123.52  4842.4  123.59
  4868.5  123.67  4899.4  124.04  4938.3   124.5  4948.8  124.25  4957.5  123.91
 4957.59  123.91  4957.7   123.9 4957.81   123.9  4957.9  123.89 4977.81  123.11
  4977.9  123.11    4978   123.1  4982.7  122.92  4988.2  116.41    4994  114.03
  4994.8  113.69  5001.4  113.52  5004.6  113.64  5005.9  114.25  5008.3  114.56
  5018.2  115.83  5048.2  121.58 5048.29   121.6  5048.4  121.62  5058.4  123.54
 5068.29  123.75  5068.4  123.75 5068.51  123.75  5068.7  123.76  5071.1  123.81
  5146.3  123.09  5187.2  123.29  5188.9   123.3  5253.7   123.2  5256.3   123.2
  5302.9  123.28    5303  123.28    5306  123.85  5343.8  123.67  5358.8  123.06
  5378.8   122.9  5383.8  122.71  5388.8   122.7  5398.8  123.65  5473.8  123.42
  5519.2  124.07  5522.3  124.11  5637.3   123.6  5742.3  124.03  5762.3  123.39
  5971.7  123.64  5987.3  123.66  6017.3  124.92
BR D #Mann= 5
   618.5     .99  4143.2      .1  4982.7    .035  5058.4      .1  5519.2     .99
BR D Banks=4982.7,5058.4
BC Design=,, 0 ,, 0 ,,,,,,
BC HTab HWMax=125.4
BC Use User HTab Curves=0
BC User HTab FreeFlow(D)= 0

Type RM Length L Ch R = 1 ,220867.3,235.35,235.35,235.35
BEGIN DESCRIPTION:
Downstream Section of Bridge/Culvert/Weir
END DESCRIPTION:
XS GIS Cut Line= 6
      3056360.96     13911498.14      3056705.88     13909554.99
      3056714.35     13908595.48      3056622.01     13907958.28
      3056416.32     13907388.47      3055547.31     13906544.14
#Sta/Elev= 30
   618.5  125.08   798.5  122.33   938.5  125.24  1073.5  122.89  1108.5  124.31
  1253.5  122.93  1558.5  124.31  2118.5  123.02  2228.5     125  2445.4  125.04
  2505.4  122.73  2920.4  122.93  2955.4  124.28  3018.3  122.36  3273.3   122.7
  3448.3  124.18  3755.8  122.17  3785.8  123.46  4143.2  124.35  4406.8  121.39
  4938.3  124.47  4982.7  122.89  4988.2  116.38  4994.8  113.66  5001.4  113.49
  5058.4  123.51  5388.8  122.67  5519.2  124.04  5987.3  123.63  6017.3  124.89
#Mann= 5 , 1 , 0
   618.5     .99       0  4143.2      .1       0  4982.7    .035       0
  5058.4      .1       0  5519.2     .99       0
#XS Ineff= 2 , 0
       0    4967   123.5    5059       0   123.2
Permanent Ineff=
       F       F
Bank Sta=4982.7,5058.4
XS Rating Curve= 0 ,0
Exp/Cntr=0.5,0.3

Type RM Length L Ch R = 1 ,220631.9,112,112,112
BEGIN DESCRIPTION:
Upstream Section of Bridge/Culvert/Weir
END DESCRIPTION:
XS GIS Cut Line= 6
      3056634.56      13912005.3      3056755.43     13909710.47
      3056754.86     13908623.71      3056487.44      13907338.4
      3056476.98     13907060.91      3056394.11     13906492.31
#Sta/Elev= 30
    93.4  124.95   123.4  122.25   148.4  123.71   528.4  123.45   563.4  124.47
  2058.4  121.79  2078.4  123.88  2797.6  123.26  2842.6  124.26  2917.6  122.58
  3376.9  123.83  3646.5  122.55  3941.5  124.19  4311.9   124.1  4346.9  122.55
  4703.7  121.89  4728.7  123.42  4933.3  122.23  4951.3  120.57  4970.5  116.05
  4991.3  117.18  4994.4  114.13  5002.1  112.79  5044.4  122.46  5255.4  122.53
    5270  124.08    5300  124.03  5515.6  122.94  5645.6  124.79  5645.7  125.83
#Mann= 5 , 1 , 0
    93.4      .2       0  3376.9      .1       0  4933.3    .035       0
  5044.4      .1       0    5300     .99       0
#XS Ineff= 2 , 0
       0    4941  121.69    5044       0  122.25
Permanent Ineff=
       F       F
Bank Sta=4933.3,5044.4
XS Rating Curve= 0 ,0
Exp/Cntr=0.5,0.3

Type RM Length L Ch R = 3 ,220575.9,,,
BEGIN DESCRIPTION:
PERRY ROAD
Structure ID: P00-92
END DESCRIPTION:
Bridge Culvert--1,0,-1,-1, 0
Deck Dist Width WeirC Skew NumUp NumDn MinLoCord MaxHiCord MaxSubmerge Is_Ogee
10,92,2.6,0, 60, 60, , , 0.95, 0, 1,1,,
    93.4   108.4   123.4   148.4   358.4   528.4   563.4   603.4   633.4   823.4
   933.4   953.4  1103.4  1238.4  1538.4  1958.4  2058.4  2078.4  2797.6  2842.6
  2917.6  2932.6  3307.6  3626.5  3646.5  3676.5  3786.5  3941.5  4066.5  4116.5
  4201.5  4221.5  4266.9  4311.9  4346.9  4678.7  4703.7  4713.7  4728.7  4812.6
  4865.8  4910.4  4933.3 4938.49  4938.6 4951.01 5033.29  5033.4 5037.91  5044.4
  5105.2  5163.9  5255.4    5270  5495.6  5515.6  5570.6  5615.6  5645.6  5645.7
  124.92  124.46  122.22  123.68   124.3  123.42  124.44  123.97  124.36  123.54
  123.83  123.42  123.39  122.74  123.44  122.52  121.76  123.85  123.23  124.23
  122.55  123.16  124.18     123  122.52  122.97  122.78  124.16  124.24  123.31
  124.05  123.49  123.23  124.07  122.52   122.4  121.86  122.85  123.39     122
  122.87  122.96   122.3   122.3   122.8  122.88  122.96  122.96  122.45  122.47
  123.16  122.55  122.51  124.05  123.47  122.91  124.39  124.11  124.76   125.8
  124.92  124.46  122.22  123.68   124.3  123.42  124.44  123.97  124.36  123.54
  123.83  123.42  123.39  122.74  123.44  122.52  121.76  123.85  123.23  124.23
  122.55  123.16  124.18     123  122.52  122.97  122.78  124.16  124.24  123.31
  124.05  123.49  123.23  124.07  122.52   122.4  121.86  122.85  123.39  121.98
  122.86  122.95   122.2  121.72  121.71  120.57  120.66  119.73  120.84  122.43
  123.15  122.54   122.5  124.05  123.47  122.91  124.39  124.11  124.76   125.8
    93.4   108.4   123.4   148.4   358.4   528.4   563.4   603.4   633.4   823.4
   933.4   953.4  1103.4  1238.4  1538.4  1958.4  2058.4  2078.4  2797.6  2842.6
  2917.6  2932.6  3307.6  3626.5  3646.5  3676.5  3786.5  3941.5  4066.5  4116.5
  4201.5  4221.5  4266.9  4311.9  4346.9  4678.7  4703.7  4713.7  4728.7  4812.6
  4865.8  4910.4  4933.3 4938.49  4938.6 4951.01 5033.29  5033.4 5037.91  5044.4
  5105.2  5163.9  5255.4    5270  5495.6  5515.6  5570.6  5615.6  5645.6  5645.7
  124.92  124.46  122.22  123.68   124.3  123.42  124.44  123.97  124.36  123.54
  123.83  123.42  123.39  122.74  123.44  122.52  121.76  123.85  123.23  124.23
  122.55  123.16  124.18     123  122.52  122.97  122.78  124.16  124.24  123.31
  124.05  123.49  123.23  124.07  122.52   122.4  121.86  122.85  123.39     122
  122.87  122.96   122.3   122.3   122.8  122.88  122.96  122.96  122.45  122.47
  123.16  122.55  122.51  124.05  123.47  122.91  124.39  124.11  124.76   125.8
   124.8  124.34   122.1  123.56  124.18   123.3  124.32  123.85  124.24  123.42
  123.71   123.3  123.27  122.62  123.32   122.4  121.64  123.73  123.11  124.11
  122.43  123.04  124.06  122.88   122.4  122.85  122.66  124.04  124.12  123.19
  123.93  123.37  123.11  123.95   122.4  122.28  121.74  122.73  123.27  121.86
  122.74  122.83  122.08   121.6  121.59  120.45  120.54  119.61  120.72  122.31
  123.03  122.42  122.38  123.93  123.35  122.79  124.27  123.99  124.64  125.68
Pier Skew, UpSta & Num, DnSta & Num=  ,4970.5, 2 ,4970.5, 2 , 0 , 0 , 0 ,,
     1.4     1.4
  115.06  121.69
     1.4     1.4
  114.94  121.57
Pier Skew, UpSta & Num, DnSta & Num=  ,5005.5, 2 ,5005.5, 2 , 0 , 0 , 0 ,,
     1.4     1.4
  112.24  121.73
     1.4     1.4
  112.12  121.61
BR Coef= 1 , 1 , 0 ,1.25, 0 ,,,0.8,0,2,0,
WSPro=,,,, 1 ,,,, 0 ,,,, 0 ,,,,-1 ,-1 ,-1 , 0 , 0 , 0 , 0 , 0
BR U #Sta/Elev= 141
    93.4  124.92    98.4  124.88   108.4  124.46   118.4  122.86   123.4  122.22
   133.4  122.75   138.4  123.23   148.4  123.68   313.4  123.93   318.4  124.09
   358.4   124.3   378.4  123.91   528.4  123.42   563.4  124.44   578.4  124.15
   588.4  124.37   603.4  123.97   633.4  124.36   638.4  124.25   728.4  123.78
   743.4  123.99   758.4  123.71   798.4  123.94   823.4  123.54   843.4  123.81
   908.4  123.83   918.4  123.57   933.4  123.83   953.4  123.42  1088.4  123.11
  1103.4  123.39  1133.4  122.95  1223.4   123.1  1233.4  122.75  1238.4  122.74
  1253.4  123.03  1268.4  122.71  1528.4  123.23  1538.4  123.44  1948.4  122.33
  1958.4  122.52  1983.4  122.15  2058.4  121.76  2073.4  123.62  2078.4  123.85
  2497.6  123.54  2797.6  123.23  2842.6  124.23  2917.6  122.55  2932.6  123.16
  3302.6  124.04  3307.6  124.18  3376.9   123.8  3386.5  123.75  3626.5     123
  3646.5  122.52  3676.5  122.97  3786.5  122.78  3836.5   123.5  3931.5  123.83
  3941.5  124.16  3956.5  124.02  4066.5  124.24  4116.5  123.31  4201.5  124.05
  4221.5  123.49  4251.9  123.62  4266.9  123.23  4281.9   123.3  4301.9  124.02
  4311.9  124.07  4336.9  123.14  4346.9  122.52  4678.7   122.4  4683.7  122.17
  4703.7  121.86  4713.7  122.85  4728.7  123.39  4752.4  122.88  4770.6  122.51
    4772  122.48  4809.5  122.02  4812.6  121.98  4860.4  122.77  4865.8  122.86
  4910.4  122.95  4911.8   122.9  4933.3   122.2  4938.1  121.76 4938.49  121.72
  4938.6  121.71 4938.71   121.7 4951.01  120.57  4951.1  120.56  4951.2  120.55
  4951.3  120.54  4970.5  116.02  4984.4  116.78  4991.3  117.15  4994.4   114.1
  4997.1  113.14  5002.1  112.76  5004.6  113.03  5005.5  113.96  5008.6  114.38
  5012.2  114.44  5028.1  118.43  5033.2  119.68 5033.29   119.7  5033.4  119.73
 5037.69  120.78  5037.8  120.81 5037.91  120.84  5038.8  121.06  5044.4  122.43
  5090.9  122.77  5097.8  122.95  5105.2  123.15  5163.9  122.54    5170  122.57
  5210.7  122.74  5234.5  122.61  5255.4   122.5  5256.2  122.58    5270  124.05
    5300     124    5340  123.94    5365  123.51  5395.6  123.72  5495.6  123.47
  5505.6   122.9  5515.6  122.91  5525.6  123.37  5555.6  123.77  5565.6  124.28
  5570.6  124.39  5615.6  124.11  5630.6  124.71  5640.6  124.65  5645.6  124.76
  5645.7   125.8
BR U #Mann= 5
    93.4      .2  3376.9      .1  4933.3    .035  5044.4      .1    5300     .99
BR U Banks=4933.3,5044.4
BR D #Sta/Elev= 141
    93.4   124.8    98.4  124.76   108.4  124.34   118.4  122.74   123.4   122.1
   133.4  122.63   138.4  123.11   148.4  123.56   313.4  123.81   318.4  123.97
   358.4  124.18   378.4  123.79   528.4   123.3   563.4  124.32   578.4  124.03
   588.4  124.25   603.4  123.85   633.4  124.24   638.4  124.13   728.4  123.66
   743.4  123.87   758.4  123.59   798.4  123.82   823.4  123.42   843.4  123.69
   908.4  123.71   918.4  123.45   933.4  123.71   953.4   123.3  1088.4  122.99
  1103.4  123.27  1133.4  122.83  1223.4  122.98  1233.4  122.63  1238.4  122.62
  1253.4  122.91  1268.4  122.59  1528.4  123.11  1538.4  123.32  1948.4  122.21
  1958.4   122.4  1983.4  122.03  2058.4  121.64  2073.4   123.5  2078.4  123.73
  2497.6  123.42  2797.6  123.11  2842.6  124.11  2917.6  122.43  2932.6  123.04
  3302.6  123.92  3307.6  124.06  3376.9  123.68  3386.5  123.63  3626.5  122.88
  3646.5   122.4  3676.5  122.85  3786.5  122.66  3836.5  123.38  3931.5  123.71
  3941.5  124.04  3956.5   123.9  4066.5  124.12  4116.5  123.19  4201.5  123.93
  4221.5  123.37  4251.9   123.5  4266.9  123.11  4281.9  123.18  4301.9   123.9
  4311.9  123.95  4336.9  123.02  4346.9   122.4  4678.7  122.28  4683.7  122.05
  4703.7  121.74  4713.7  122.73  4728.7  123.27  4752.4  122.76  4770.6  122.39
    4772  122.36  4809.5   121.9  4812.6  121.86  4860.4  122.65  4865.8  122.74
  4910.4  122.83  4911.8  122.78  4933.3  122.08  4938.1  121.64 4938.49   121.6
  4938.6  121.59 4938.71  121.58 4951.01  120.45  4951.1  120.44  4951.2  120.43
  4951.3  120.42  4970.5   115.9  4984.4  116.66  4991.3  117.03  4994.4  113.98
  4997.1  113.02  5002.1  112.64  5004.6  112.91  5005.5  113.84  5008.6  114.26
  5012.2  114.32  5028.1  118.31  5033.2  119.56 5033.29  119.58  5033.4  119.61
 5037.69  120.66  5037.8  120.69 5037.91  120.72  5038.8  120.94  5044.4  122.31
  5090.9  122.65  5097.8  122.83  5105.2  123.03  5163.9  122.42    5170  122.45
  5210.7  122.62  5234.5  122.49  5255.4  122.38  5256.2  122.46    5270  123.93
    5300  123.88    5340  123.82    5365  123.39  5395.6   123.6  5495.6  123.35
  5505.6  122.78  5515.6  122.79  5525.6  123.25  5555.6  123.65  5565.6  124.16
  5570.6  124.27  5615.6  123.99  5630.6  124.59  5640.6  124.53  5645.6  124.64
  5645.7  125.68
BR D #Mann= 5
    93.4      .2  3376.9      .1  4933.3    .035  5044.4      .1    5300     .99
BR D Banks=4933.3,5044.4
BC Design=,, 0 ,, 0 ,,,,,,
BC HTab HWMax=125.83
BC Use User HTab Curves=0
BC User HTab FreeFlow(D)= 0

Type RM Length L Ch R = 1 ,220519.9,262.5,262.5,262.5
BEGIN DESCRIPTION:
Downstream Section of Bridge/Culvert/Weir
END DESCRIPTION:
XS GIS Cut Line= 6
      3056745.19     13912022.77      3056866.05     13909727.93
      3056865.48     13908641.17      3056598.06     13907355.86
       3056587.6     13907078.37      3056504.74     13906509.78
#Sta/Elev= 30
    93.4  124.81   123.4  122.11   148.4  123.57   528.4  123.31   563.4  124.33
  2058.4  121.65  2078.4  123.74  2797.6  123.12  2842.6  124.12  2917.6  122.44
  3376.9  123.69  3646.5  122.41  3941.5  124.05  4311.9  123.96  4346.9  122.41
  4703.7  121.75  4728.7  123.28  4933.3  122.09  4951.3  120.43  4970.5  115.91
  4991.3  117.04  4994.4  113.99  5002.1  112.65  5044.4  122.32  5255.4  122.39
    5270  123.94    5300  123.89  5515.6   122.8  5645.6  124.65  5645.7  125.69
#Mann= 5 , 1 , 0
    93.4      .2       0  3376.9      .1       0  4933.3    .035       0
  5044.4      .1       0    5300     .99       0
#XS Ineff= 2 , 0
       0    4941  121.69    5044       0  122.25
Permanent Ineff=
       F       F
Bank Sta=4933.3,5044.4
XS Rating Curve= 0 ,0
Exp/Cntr=0.5,0.3

Type RM Length L Ch R = 1 ,220257.4,274.2,258.5,206
BEGIN DESCRIPTION:
Cross Section 220257.4-Interpolated
END DESCRIPTION:
XS GIS Cut Line= 6
      3056831.66     13911935.37       3056888.8     13909261.05
      3056972.95     13908839.67      3056776.84      13907422.7
      3056877.68     13907092.67      3056909.68     13905818.09
#Sta/Elev= 30
   302.6  124.94   332.6  122.83   347.6  123.95   777.6  124.36  2132.6  121.65
  2222.6  123.84  2462.6  124.45  2987.8  123.74  3062.8  122.41  3351.1  123.01
  3404.6  123.06    4367  121.31    4412  123.98    4477   124.7    4762  122.94
  4917.7   125.4  4942.7  124.77  4952.3  122.77  4990.4  112.91    5010   112.8
  5011.2  114.49  5041.8  122.67    5100  123.37  5177.7  122.04  5212.8  119.77
  5272.8  122.78  5797.8  123.97  5917.8  120.89  5977.8  123.74  6457.8  124.27
#Mann= 6 , 1 , 0
   302.6      .2       0  3351.1     .12       0  3404.6      .1       0
  4952.3    .035       0  5041.8      .1       0    5100      .2       0
#XS Ineff= 2 , 0
       0  2965.1   124.1  5752.8       0   124.2
Permanent Ineff=
       F       F
Bank Sta=4952.3,5041.8
XS Rating Curve= 0 ,0
Exp/Cntr=0.3,0.1