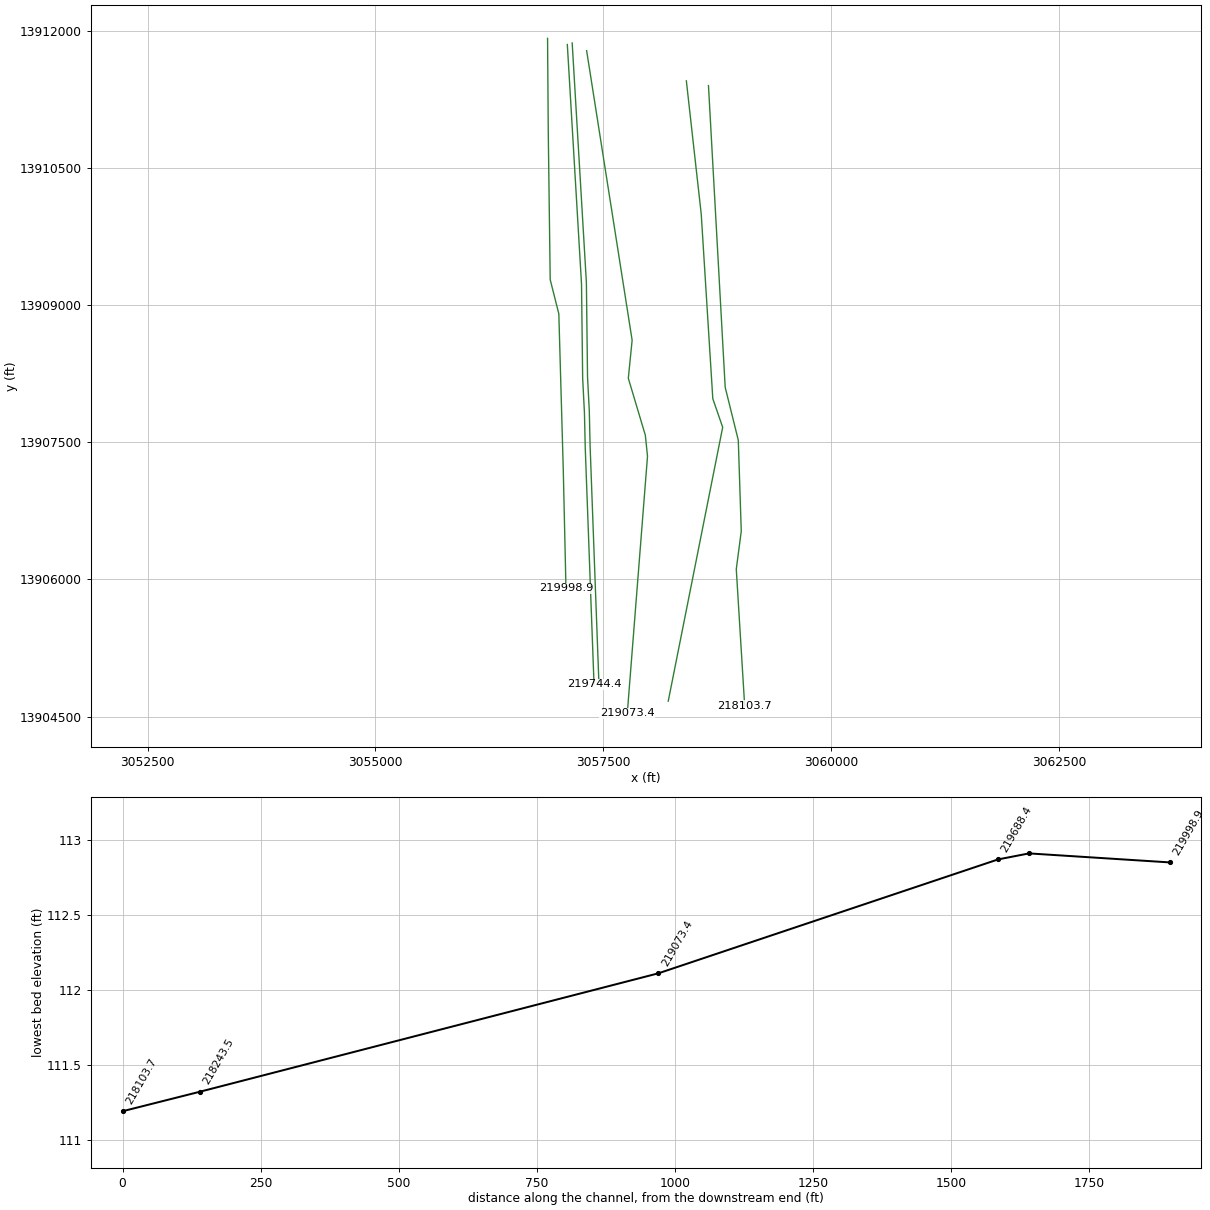
HEC-RAS study P100-00-00.prj: P100-00-00

--- P100-00-00.g01 (geometry) --- (continued)

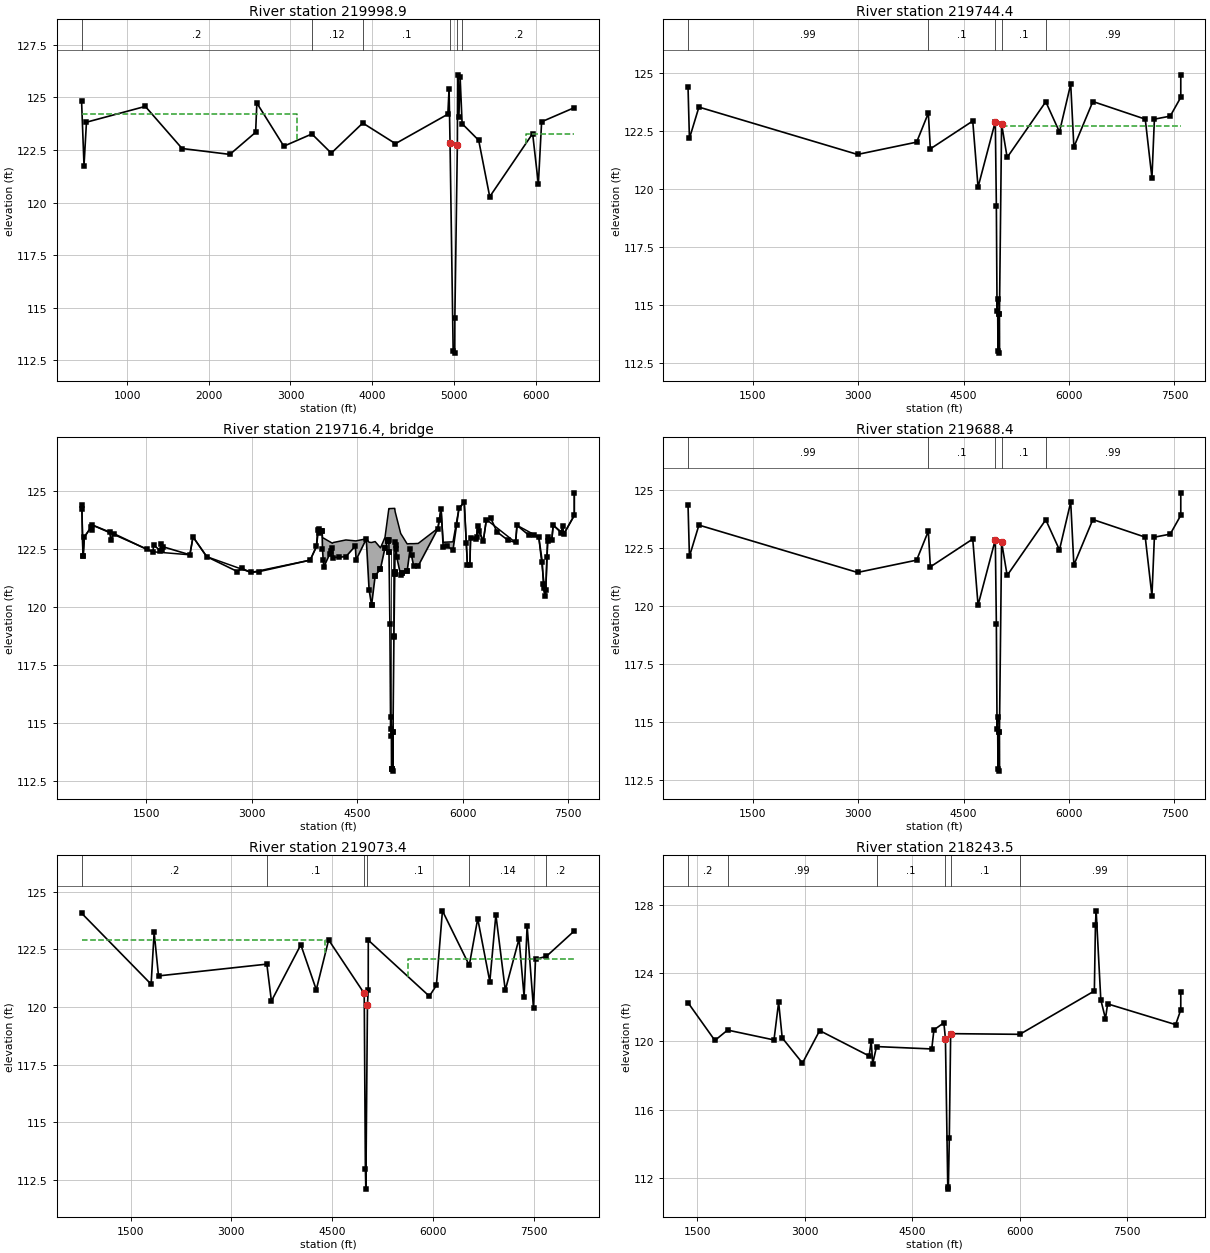
Type RM Length L Ch R = 1 ,219998.9,272.8,254.5,249.5
BEGIN DESCRIPTION:
Cross Section 219998.9-Interpolated
END DESCRIPTION:
XS GIS Cut Line= 6
      3056887.53     13911921.75      3056895.16     13910902.69
       3056916.4     13909281.41      3057011.07     13908906.86
      3057059.83     13907199.89       3057089.4     13905905.23
#Sta/Elev= 30
   443.4  124.85   473.4  121.76   503.4  123.82  1223.4  124.57  1673.4  122.57
  2258.4  122.29  2573.4  123.34  2588.4  124.73  2918.4  122.68  3261.9  123.26
  3499.3  122.35  3884.5  123.78  4284.3   122.8  4925.5   124.2  4940.5   125.4
  4952.3  122.82  4990.4  112.96    5010  112.85  5011.2  114.54  5041.8  122.72
  5045.5  126.07  5060.5  124.06  5075.5  125.98    5100  123.75  5302.9  122.96
  5437.9  120.28  5962.9  123.28  6032.9  120.88  6072.9  123.84  6472.9  124.51
#Mann= 6 , 1 , 0
   443.4      .2       0  3261.9     .12       0  3884.5      .1       0
  4952.3    .035       0  5041.8      .1       0    5100      .2       0
#XS Ineff= 2 , 0
       0  3084.1  124.23  5879.3       0  123.28
Permanent Ineff=
       F       F
Bank Sta=4952.3,5041.8
XS Rating Curve= 0 ,0
Exp/Cntr=0.5,0.3

Type RM Length L Ch R = 1 ,219744.4,56,56,56
BEGIN DESCRIPTION:
Upstream Section of Bridge/Culvert/Weir
END DESCRIPTION:
XS GIS Cut Line= 6
      3057104.21     13911854.14      3057259.96      13909234.3
      3057272.57     13908199.06      3057291.83     13907830.09
       3057300.8     13907442.29      3057397.18     13904854.51
#Sta/Elev= 30
   582.8  124.38   602.8  122.16   737.8  123.51  2992.8  121.47  3833.5     122
    4000  123.25  4028.5  121.71  4631.5  122.91  4706.9  120.06  4952.3  122.88
  4967.2  119.27  4977.2  114.73    4985  115.24  4990.4  113.02  5006.9   114.6
    5010  112.91  5011.2   114.6  5041.8  122.78  5120.7  121.34    5670  123.74
  5864.5  122.44  6024.5   124.5  6069.5  121.79  6339.5  123.75  7084.5  122.99
  7179.5  120.46  7214.5  122.99  7439.5  123.12  7589.5  123.93  7589.6   124.9
#Mann= 5 , 1 , 0
   582.8     .99       0    4000      .1       0  4952.3    .035       0
  5041.8      .1       0    5670     .99       0
#XS Ineff= 2 , 0
       0    4944   122.5    5047       0   122.7
Permanent Ineff=
       F       F
Bank Sta=4952.3,5041.8
XS Rating Curve= 0 ,0
Exp/Cntr=0.5,0.3

Type RM Length L Ch R = 3 ,219716.4,,,
BEGIN DESCRIPTION:
ROCKVILLE ROAD
Structure ID: P00-90
END DESCRIPTION:
Bridge Culvert--1,0,-1,-1, 0
Deck Dist Width WeirC Skew NumUp NumDn MinLoCord MaxHiCord MaxSubmerge Is_Ogee
10,36,2.6,0, 60, 60, , , 0.95, 0, 1,1,,
   582.8   587.8   602.8   622.8   737.8  1597.8  2122.8  2167.8  2362.8  2992.8
  3833.5  3923.5  3953.5  4003.5  4008.5  4028.5  4148.5  4163.5  4341.5  4476.5
  4486.5  4631.5  4671.5  4706.9  4757.3  4833.5  4897.4  4952.3 4954.41 5036.39
  5036.5  5041.8  5120.7  5212.6  5253.7    5305    5370  5649.9  5694.9  5724.9
  5864.5  5949.5  6024.5  6069.5  6104.5  6114.5  6194.5  6219.5  6294.5  6339.5
  6754.5  6774.5  7084.5  7179.5  7214.5  7269.5  7289.5  7439.5  7589.5  7589.6
  124.38  124.21  122.16     123  123.51  122.36  122.23     123  122.15  121.47
     122  122.59  123.34  123.27  122.97  122.94  122.73  122.76  122.87  122.83
  122.83  122.92  122.77  122.76   122.8  122.53  122.98  124.22  124.22  124.23
  124.22  124.09  123.15   122.7  122.71  122.71  122.72  123.37  124.22  122.77
  122.79  124.23   124.5  121.79  121.78  122.97   122.9  123.45  122.81  123.75
  122.76   123.5  122.99  120.46  122.99  122.88  123.51  123.12  123.93   124.9
  124.38  124.21  122.16     123  123.51  122.36  122.23     123  122.15  121.47
     122  122.59  123.34  123.26  122.49  121.71  122.51  122.11  122.15  122.61
  122.01  122.91  120.72  120.06  121.33  121.63  122.53  122.88  122.37  122.43
  121.51  122.78  121.34  121.52  122.46  121.75  121.75  123.36  124.21  122.58
  122.44  124.23   124.5  121.79  121.78  122.97   122.9  123.45  122.81  123.75
  122.76   123.5  122.99  120.46  122.99  122.88  123.51  123.12  123.93   124.9
   582.8   587.8   602.8   622.8   737.8  1597.8  2122.8  2167.8  2362.8  2992.8
  3833.5  3923.5  3953.5  4003.5  4008.5  4028.5  4148.5  4163.5  4341.5  4476.5
  4486.5  4631.5  4671.5  4706.9  4757.3  4833.5  4897.4  4952.3 4954.41 5036.39
  5036.5  5041.8  5120.7  5212.6  5253.7    5305    5370  5649.9  5694.9  5724.9
  5864.5  5949.5  6024.5  6069.5  6104.5  6114.5  6194.5  6219.5  6294.5  6339.5
  6754.5  6774.5  7084.5  7179.5  7214.5  7269.5  7289.5  7439.5  7589.5  7589.6
  124.38  124.21  122.16     123  123.51  122.36  122.23     123  122.15  121.47
     122  122.59  123.34  123.27  122.97  122.94  122.73  122.76  122.87  122.83
  122.83  122.92  122.77  122.76   122.8  122.53  122.98  124.22  124.22  124.23
  124.22  124.09  123.15   122.7  122.71  122.71  122.72  123.37  124.22  122.77
  122.79  124.23   124.5  121.79  121.78  122.97   122.9  123.45  122.81  123.75
  122.76   123.5  122.99  120.46  122.99  122.88  123.51  123.12  123.93   124.9
  124.35  124.18  122.13  122.97  123.48  122.33   122.2  122.97  122.12  121.44
  121.97  122.56  123.31  123.23  122.46  121.68  122.48  122.08  122.12  122.58
  121.98  122.88  120.69  120.03   121.3   121.6   122.5  122.85  122.34   122.4
  121.48  122.75  121.31  121.49  122.43  121.72  121.72  123.33  124.18  122.55
  122.41   124.2  124.47  121.76  121.75  122.94  122.87  123.42  122.78  123.72
  122.73  123.47  122.96  120.43  122.96  122.85  123.48  123.09   123.9  124.87
Pier Skew, UpSta & Num, DnSta & Num=  ,4977.2, 2 ,4977.2, 2 , 0 , 0 , 0 ,,
     1.4     1.4
  113.78  123.42
     1.4     1.4
  113.75  123.39
Pier Skew, UpSta & Num, DnSta & Num=  ,5006.9, 2 ,5006.9, 2 , 0 , 0 , 0 ,,
     1.4     1.4
  113.22  123.43
     1.4     1.4
  113.19   123.4
Abutment Skew #Up #Dn= , 2 , 2
  4954.3    4993
  122.42  113.02
  4954.3    4993
  122.39  112.99
Abutment Skew #Up #Dn= , 2 , 2
  5024.8 5036.59
  118.72  122.43
  5024.8 5036.59
  118.69   122.4
BR Coef= 1 , 1 , 0 ,1.25, 0 ,,,0.8,0,2,0,
WSPro=,,,, 1 ,,,, 0 ,,,, 0 ,,,,-1 ,-1 ,-1 , 0 , 0 , 0 , 0 , 0
BR U #Sta/Elev= 134
   582.8  124.38   587.8  124.21   602.8  122.16   607.8  122.17   622.8     123
   717.8  123.41   732.8  123.31   737.8  123.51   982.8  123.21   997.8  122.88
  1042.8  123.14  1507.8  122.47  1597.8  122.36  1607.8  122.65  1702.8  122.41
  1712.8   122.7  1732.8  122.43  1747.8  122.57  2122.8  122.23  2167.8     123
  2362.8  122.15  2797.8  121.51  2857.8  121.65  2992.8  121.47  3112.8  121.51
  3833.5     122  3923.5  122.59  3938.5  123.28  3953.5  123.34  3958.5  123.19
  3993.8  123.24    4000  123.25  4003.5  123.26  4008.5  122.49  4018.5  122.01
  4028.5  121.71  4110.8  122.26  4130.8  122.39  4148.5  122.51  4163.5  122.11
  4244.1  122.13  4341.5  122.15  4476.5  122.61  4486.5  122.01  4631.5  122.91
  4671.5  120.72  4706.5  120.07  4706.9  120.06  4757.3  121.33  4758.1  121.33
  4831.9  121.61  4833.5  121.63    4897  122.53  4897.4  122.53  4946.4  122.84
 4946.59  122.84  4946.7  122.84 4946.81  122.85  4952.3  122.88 4954.41  122.37
  4954.5  122.35  4967.2  119.27  4977.2  114.73    4985  115.24  4988.7  114.42
  4990.4  113.02    4993  113.02  4998.3  113.02  5006.9   114.6    5010  112.91
  5011.2   114.6  5024.7  118.69  5024.8  118.72    5036  121.39 5036.06  121.41
 5036.17  121.44 5036.28  121.46 5036.39  121.49  5036.5  121.51  5041.8  122.78
  5050.6  122.65  5054.9   122.5  5065.9  122.12  5120.7  121.34  5142.3  121.44
    5144  121.44  5210.5  121.52  5212.6  121.52  5253.7  122.46    5275   122.2
    5305  121.75    5370  121.75  5649.9  123.36    5670  123.74  5694.9  124.21
  5724.9  122.58  5784.5  122.59  5864.5  122.44  5915.8  123.52  5949.5  124.23
  6024.5   124.5  6054.5  122.73  6069.5  121.79  6104.5  121.78  6114.5  122.97
  6194.5   122.9  6199.5  122.99  6219.5  123.45  6229.5  123.26  6294.5  122.81
  6339.5  123.75  6399.5  123.82  6489.5  123.22  6644.5  122.86  6754.5  122.76
  6774.5   123.5  6944.5  123.07  7019.5  123.07  7084.5  122.99  7134.5  121.92
  7149.5  120.96  7154.5  120.81  7179.5  120.46  7184.5   120.7  7199.5  122.15
  7209.5  122.84  7214.5  122.99  7269.5  122.88  7289.5  123.51  7399.5  123.19
  7424.5  123.45  7439.5  123.12  7589.5  123.93  7589.6   124.9
BR U #Mann= 5
   582.8     .99    4000      .1  4952.3    .035  5041.8      .1    5670     .99
BR U Banks=4952.3,5041.8
BR D #Sta/Elev= 134
   582.8  124.35   587.8  124.18   602.8  122.13   607.8  122.14   622.8  122.97
   717.8  123.38   732.8  123.28   737.8  123.48   982.8  123.18   997.8  122.85
  1042.8  123.11  1507.8  122.44  1597.8  122.33  1607.8  122.62  1702.8  122.38
  1712.8  122.67  1732.8   122.4  1747.8  122.54  2122.8   122.2  2167.8  122.97
  2362.8  122.12  2797.8  121.48  2857.8  121.62  2992.8  121.44  3112.8  121.48
  3833.5  121.97  3923.5  122.56  3938.5  123.25  3953.5  123.31  3958.5  123.16
  3993.8  123.21    4000  123.22  4003.5  123.23  4008.5  122.46  4018.5  121.98
  4028.5  121.68  4110.8  122.23  4130.8  122.36  4148.5  122.48  4163.5  122.08
  4244.1   122.1  4341.5  122.12  4476.5  122.58  4486.5  121.98  4631.5  122.88
  4671.5  120.69  4706.5  120.04  4706.9  120.03  4757.3   121.3  4758.1   121.3
  4831.9  121.58  4833.5   121.6    4897   122.5  4897.4   122.5  4946.4  122.81
 4946.59  122.81  4946.7  122.81 4946.81  122.82  4952.3  122.85 4954.41  122.34
  4954.5  122.32  4967.2  119.24  4977.2   114.7    4985  115.21  4988.7  114.39
  4990.4  112.99    4993  112.99  4998.3  112.99  5006.9  114.57    5010  112.88
  5011.2  114.57  5024.7  118.66  5024.8  118.69    5036  121.36 5036.06  121.38
 5036.17  121.41 5036.28  121.43 5036.39  121.46  5036.5  121.48  5041.8  122.75
  5050.6  122.62  5054.9  122.47  5065.9  122.09  5120.7  121.31  5142.3  121.41
    5144  121.41  5210.5  121.49  5212.6  121.49  5253.7  122.43    5275  122.17
    5305  121.72    5370  121.72  5649.9  123.33    5670  123.71  5694.9  124.18
  5724.9  122.55  5784.5  122.56  5864.5  122.41  5915.8  123.49  5949.5   124.2
  6024.5  124.47  6054.5   122.7  6069.5  121.76  6104.5  121.75  6114.5  122.94
  6194.5  122.87  6199.5  122.96  6219.5  123.42  6229.5  123.23  6294.5  122.78
  6339.5  123.72  6399.5  123.79  6489.5  123.19  6644.5  122.83  6754.5  122.73
  6774.5  123.47  6944.5  123.04  7019.5  123.04  7084.5  122.96  7134.5  121.89
  7149.5  120.93  7154.5  120.78  7179.5  120.43  7184.5  120.67  7199.5  122.12
  7209.5  122.81  7214.5  122.96  7269.5  122.85  7289.5  123.48  7399.5  123.16
  7424.5  123.42  7439.5  123.09  7589.5   123.9  7589.6  124.87
BR D #Mann= 5
   582.8     .99    4000      .1  4952.3    .035  5041.8      .1    5670     .99
BR D Banks=4952.3,5041.8
BC Design=,, 0 ,, 0 ,,,,,,
BC HTab HWMax=124.9
BC Use User HTab Curves=0
BC User HTab FreeFlow(D)= 0

Type RM Length L Ch R = 1 ,219688.4,615,615,615
BEGIN DESCRIPTION:
Downstream Section of Bridge/Culvert/Weir
END DESCRIPTION:
XS GIS Cut Line= 6
      3057157.59     13911871.06      3057313.34     13909251.22
      3057325.95     13908215.98      3057345.21     13907847.01
      3057354.18     13907459.21      3057450.57     13904871.42
#Sta/Elev= 30
   582.8  124.34   602.8  122.12   737.8  123.47  2992.8  121.43  3833.5  121.96
    4000  123.21  4028.5  121.67  4631.5  122.87  4706.9  120.02  4952.3  122.84
  4967.2  119.23  4977.2  114.69    4985   115.2  4990.4  112.98  5006.9  114.56
    5010  112.87  5011.2  114.56  5041.8  122.74  5120.7   121.3    5670   123.7
  5864.5   122.4  6024.5  124.46  6069.5  121.75  6339.5  123.71  7084.5  122.95
  7179.5  120.42  7214.5  122.95  7439.5  123.08  7589.5  123.89  7589.6  124.86
#Mann= 5 , 1 , 0
   582.8     .99       0    4000      .1       0  4952.3    .035       0
  5041.8      .1       0    5670     .99       0
#XS Ineff= 2 , 0
       0    4944   122.4    5047       0   122.6
Permanent Ineff=
       F       F
Bank Sta=4952.3,5041.8
XS Rating Curve= 0 ,0
Exp/Cntr=0.5,0.3

Type RM Length L Ch R = 1 ,219073.4,950.9,829.9,813.7
BEGIN DESCRIPTION:
Cross Section 219073.4
END DESCRIPTION:
XS GIS Cut Line= 6
      3057316.07     13911786.98       3057815.1     13908618.33
      3057773.38     13908201.67      3057959.99     13907578.33
      3057983.81     13907348.05      3057762.02     13904534.36
#Sta/Elev= 30
   770.7  124.07  1805.7  120.99  1850.7  123.24  1915.7  121.35  3527.7  121.86
  3595.7  120.26  4033.4   122.7  4263.4  120.75  4447.1  122.91  4976.7  120.59
  4993.8  112.98  5000.8  112.11  5024.6  120.08  5036.2  120.75  5037.1   122.9
  5945.5  120.47  6050.5  120.94  6140.5  124.17  6539.8  121.81  6665.5  123.83
  6845.5   121.1  6935.5     124  7075.5  120.73  7280.5  122.96  7355.5  120.45
  7400.5  123.52  7495.5  119.94  7525.5  122.07  7688.4   122.2  8102.7   123.3
#Mann= 6 , 1 , 0
   770.7      .2       0  3527.7      .1       0  4976.7    .035       0
  5024.6      .1       0  6539.8     .14       0  7688.4      .2       0
#XS Ineff= 2 , 0
       0  4397.2   122.9  5630.5       0   122.1
Permanent Ineff=
       F       F
Bank Sta=4976.7,5024.6
XS Rating Curve= 0 ,0
Exp/Cntr=0.3,0.1

Type RM Length L Ch R = 1 ,218243.5,131.1,139.8,163.9
BEGIN DESCRIPTION:
Cross Section 218243.5-Interpolated
END DESCRIPTION:
XS GIS Cut Line= 5
      3058409.89     13911456.36      3058573.15     13909997.87
      3058700.11     13907978.08       3058808.4     13907665.24
      3058211.22     13904667.91
#Sta/Elev= 30
  1368.4  122.28  1743.4  120.06  1920.9  120.67  2568.4  120.09  2633.4  122.31
  2683.4  120.21    2966  118.73    3206  120.64    3896  119.15    3926  120.02
    3946  118.69    4000   119.7    4771  119.56    4801  120.68  4939.8   121.1
  4961.7  120.17    4995  111.32    5003  111.45  5015.9  114.32  5034.8  120.46
    6000  120.42  7040.8  122.97  7055.8  126.86  7065.8  127.68  7130.8  122.45
  7195.8  121.34  7225.8  122.21  8175.8  120.99  8247.1  121.86  8247.2   122.9
#Mann= 6 , 1 , 0
  1368.4      .2       0  1920.9     .99       0    4000      .1       0
  4961.7    .035       0  5034.8      .1       0    6000     .99       0
Bank Sta=4961.7,5034.8
XS Rating Curve= 0 ,0
Exp/Cntr=0.5,0.3

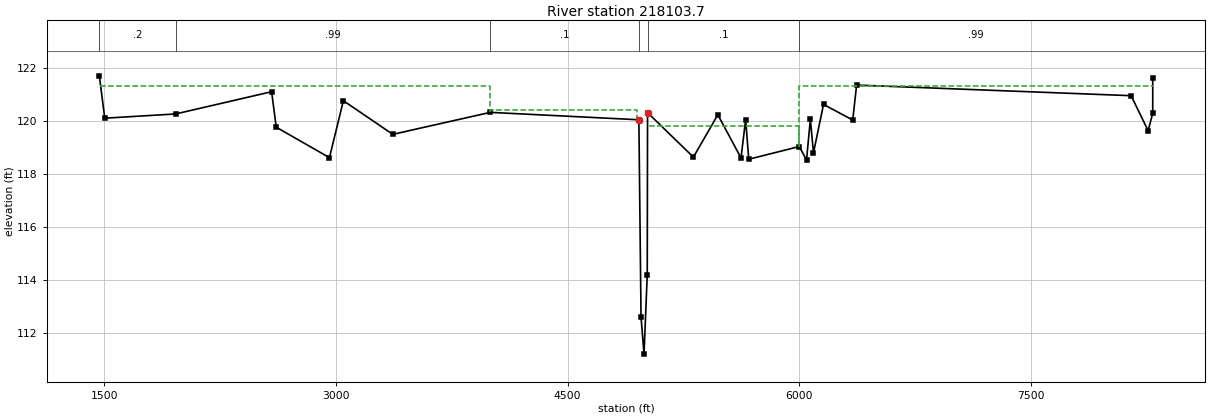
Type RM Length L Ch R = 1 ,218103.7,57,57,57
BEGIN DESCRIPTION:
Upstream Section of Bridge/Culvert/Weir
END DESCRIPTION:
XS GIS Cut Line= 6
      3058652.53     13911404.51      3058835.92     13908103.01
       3058979.6     13907524.41      3059012.27     13906527.42
      3058957.57     13906112.64      3059049.62     13904617.71
#Sta/Elev= 30
  1469.7   121.7  1504.7   120.1  1963.2  120.26  2584.7   121.1  2614.7  119.76
  2959.1  118.61  3049.1  120.76  3369.1  119.49    4000  120.32  4961.7  120.04
  4975.7  112.59    4995  111.19  5015.9  114.19  5017.9  120.31  5314.6  118.63
  5472.8  120.23  5622.8   118.6  5652.8  120.05  5672.8  118.55    6000  119.03
  6046.7  118.52  6071.7  120.06  6091.7  118.79  6156.7  120.62  6345.9  120.03
  6370.9  121.35  8147.5  120.95  8257.5  119.63  8287.5  120.28  8287.6  121.61
#Mann= 6 , 1 , 0
  1469.7      .2       0  1963.2     .99       0    4000      .1       0
  4961.7    .035       0  5017.9      .1       0    6000     .99       0
#XS Ineff= 4 ,-1
    1473    4000   121.3  4000.1    4952   120.4    5030    6000   119.8
  6000.1  8288.3   121.3
Permanent Ineff=
       F       F       F       F
Bank Sta=4961.7,5017.9
XS Rating Curve= 0 ,0
Exp/Cntr=0.5,0.3