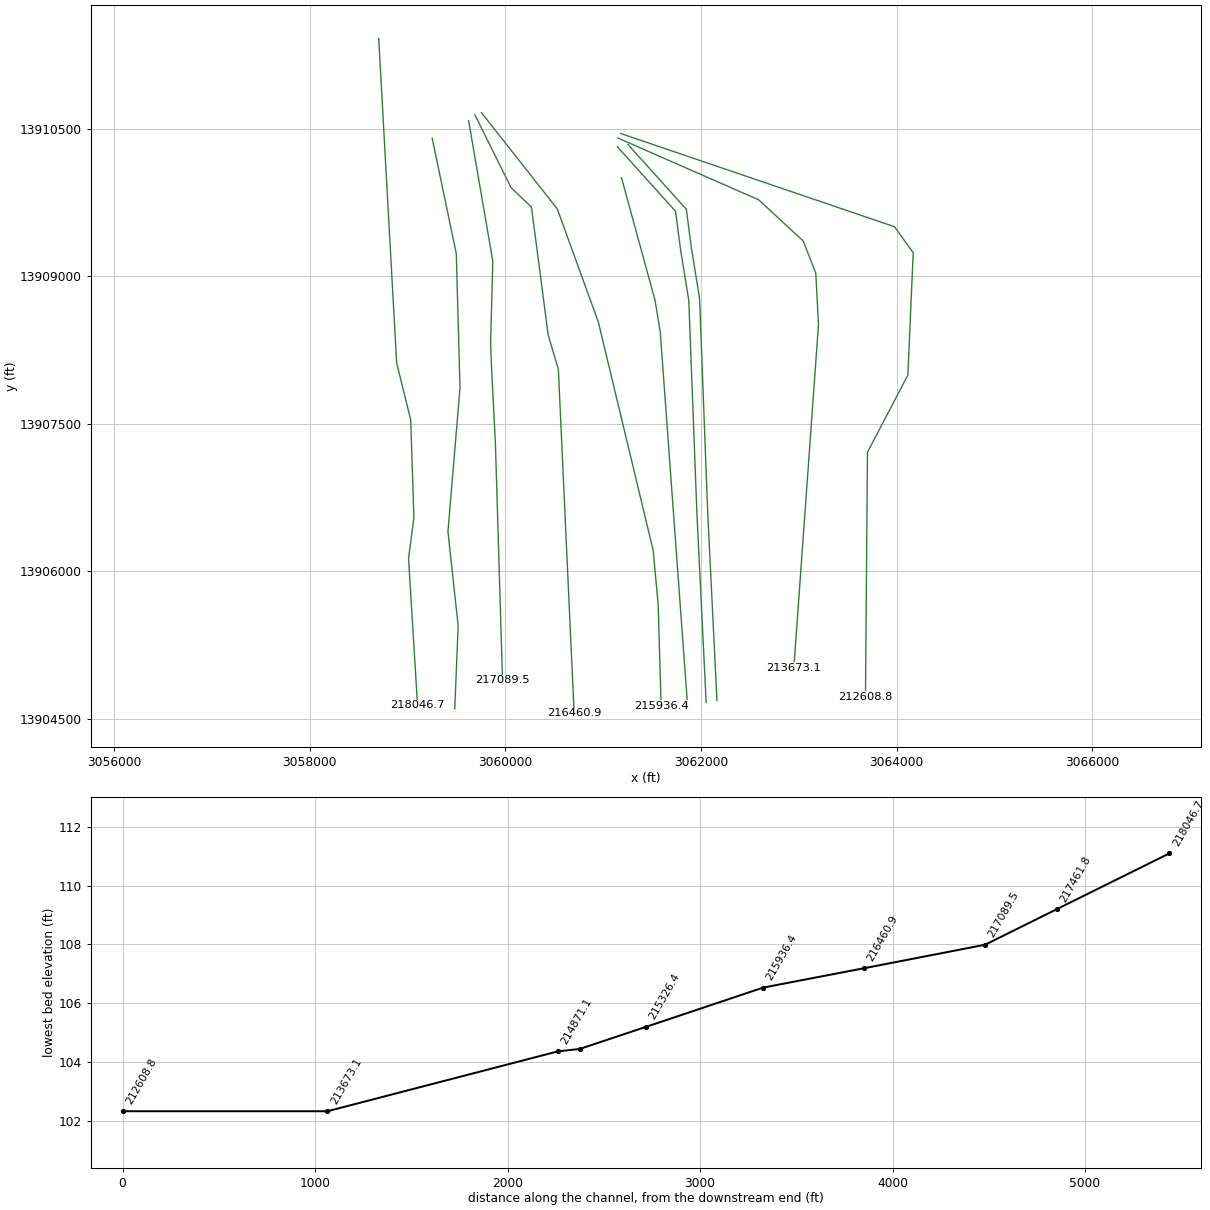
HEC-RAS study P100-00-00.prj: P100-00-00

--- P100-00-00.g01 (geometry) --- (continued)

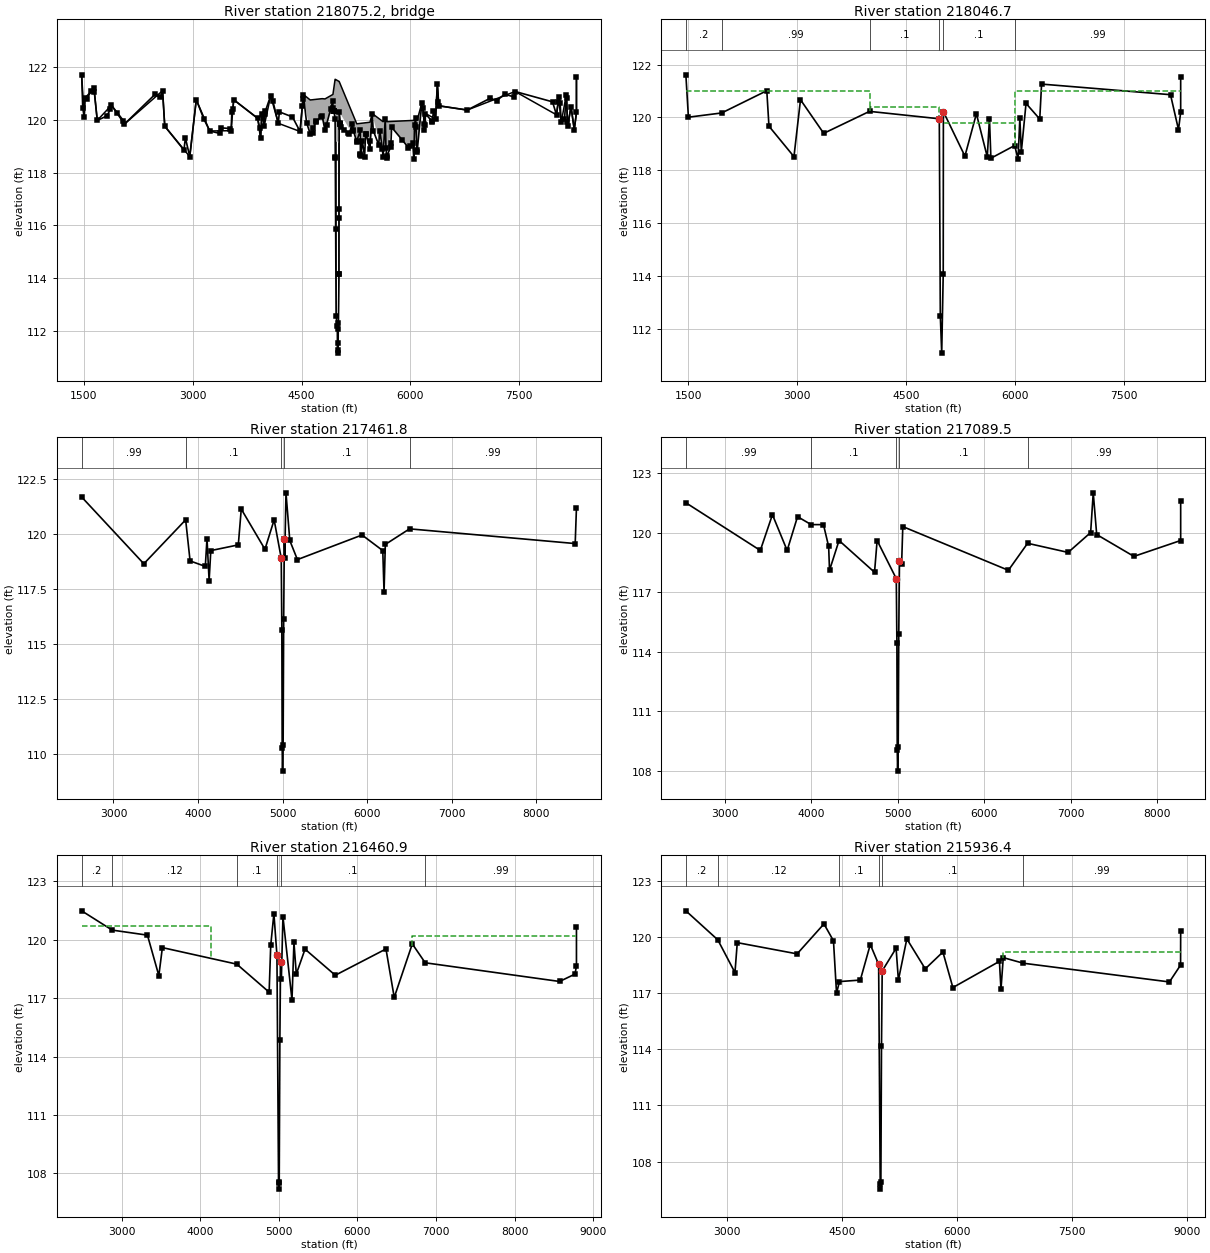
Type RM Length L Ch R = 3 ,218075.2,,,
BEGIN DESCRIPTION:
PALMERTON ROAD
Structure ID: P00-89
END DESCRIPTION:
Bridge Culvert--1,0,-1,-1, 0
Deck Dist Width WeirC Skew NumUp NumDn MinLoCord MaxHiCord MaxSubmerge Is_Ogee
10,37,2.6,0, 60, 60, , , 0.95, 0, 1,1,,
  1469.7  1504.7  1514.7  1639.7  1684.7  1879.7  2059.7  2584.7  2614.7  2959.1
  3049.1  3234.1  3529.1  3564.1  3894.1  3934.1  3954.1  3984.1  4074.1  4179.1
  4479.1  4524.1  4619.1  4783.2  4822.5  4931.9  4961.7 4964.41  4964.5 5016.59
  5016.7  5017.9  5260.3  5442.8  5472.8  5622.8  5652.8  5672.8  5740.8  6046.7
  6056.7  6071.7  6091.7  6156.7  6191.7  6206.7  6345.9  6370.9  6390.9  6782.5
  7442.5  8012.5  8042.5  8077.5  8147.5  8167.5  8212.5  8257.5  8287.5  8287.6
  121.69  120.09  120.81  121.19  119.97  120.54  119.83  121.09  119.75   118.6
  120.75  119.57  119.58  120.75  120.05   119.3  120.22  119.75   120.9  119.86
  119.55  120.95  120.74  120.79  120.78  120.95  121.52  121.52  121.52  121.44
  121.44  121.44  119.84   119.9  120.23  119.92  120.05  119.92  119.93  119.97
  119.97  120.06  119.97  120.62  119.99  120.23  120.02  121.34  120.52  120.36
  121.06  120.18  120.85  119.89  120.94  119.77  120.49  119.62  120.27   121.6
  121.69  120.09  120.81  121.19  119.97  120.54  119.83  121.09  119.75   118.6
  120.75  119.57  119.58  120.75  120.05   119.3  120.22  119.75   120.9  119.86
  119.55  120.94  119.46  120.14  119.59  120.72  120.03  118.59  119.22  119.14
  116.63   120.3  119.18  118.87  120.22  118.59  120.04  118.54  119.71  118.51
  119.79  120.05  118.78  120.61  119.61  120.22  120.02  121.34  120.52  120.36
  121.06  120.18  120.85  119.89  120.94  119.77  120.49  119.62  120.27   121.6
  1469.7  1504.7  1514.7  1639.7  1684.7  1879.7  2059.7  2584.7  2614.7  2959.1
  3049.1  3234.1  3529.1  3564.1  3894.1  3934.1  3954.1  3984.1  4074.1  4179.1
  4479.1  4524.1  4619.1  4783.2  4822.5  4931.9  4961.7 4964.41  4964.5 5016.59
  5016.7  5017.9  5260.3  5442.8  5472.8  5622.8  5652.8  5672.8  5740.8  6046.7
  6056.7  6071.7  6091.7  6156.7  6191.7  6206.7  6345.9  6370.9  6390.9  6782.5
  7442.5  8012.5  8042.5  8077.5  8147.5  8167.5  8212.5  8257.5  8287.5  8287.6
  121.69  120.09  120.81  121.19  119.97  120.54  119.83  121.09  119.75   118.6
  120.75  119.57  119.58  120.75  120.05   119.3  120.22  119.75   120.9  119.86
  119.55  120.95  120.74  120.79  120.78  120.95  121.52  121.52  121.52  121.44
  121.44  121.44  119.84   119.9  120.23  119.92  120.05  119.92  119.93  119.97
  119.97  120.06  119.97  120.62  119.99  120.23  120.02  121.34  120.52  120.36
  121.06  120.18  120.85  119.89  120.94  119.77  120.49  119.62  120.27   121.6
  121.64  120.04  120.76  121.14  119.92  120.49  119.78  121.04   119.7  118.55
   120.7  119.52  119.53   120.7     120  119.25  120.17   119.7  120.85  119.81
   119.5  120.89  119.41  120.09  119.54  120.67  119.98  118.54  119.17  119.09
  116.58  120.25  119.13  118.82  120.17  118.54  119.99  118.49  119.66  118.46
  119.74     120  118.73  120.56  119.56  120.17  119.97  121.29  120.47  120.31
  121.01  120.13   120.8  119.84  120.89  119.72  120.44  119.57  120.22  121.55
Pier Skew, UpSta & Num, DnSta & Num=  ,4975.7, 2 ,4975.7, 2 , 0 , 0 , 0 ,,
     1.4     1.4
  111.56   120.2
     1.4     1.4
  111.51  120.15
Pier Skew, UpSta & Num, DnSta & Num=  ,5005.3, 2 ,5005.3, 2 , 0 , 0 , 0 ,,
     1.4     1.4
  110.87  120.16
     1.4     1.4
  110.82  120.11
Abutment Skew #Up #Dn= , 2 , 2
  4964.3  4969.5
  119.22  115.88
  4964.3  4969.5
  119.17  115.83
BR Coef= 1 , 1 , 0 ,1.25, 0 ,,,0.8,0,2,0,
WSPro=,,,, 1 ,,,, 0 ,,,, 0 ,,,,-1 ,-1 ,-1 , 0 , 0 , 0 , 0 , 0
BR U #Sta/Elev= 163
  1469.7  121.69  1484.7  120.44  1504.7  120.09  1514.7  120.81  1549.7  120.79
  1594.7  121.08  1639.7  121.19  1644.7  121.03  1684.7  119.97  1819.7  120.14
  1864.7  120.39  1879.7  120.54  1963.2  120.25  2044.7  119.96  2059.7  119.83
  2479.7  120.95  2554.7  120.84  2584.7  121.09  2614.7  119.75  2879.1  118.85
  2899.1  119.31  2959.1   118.6  3049.1  120.75  3154.1  120.02  3234.1  119.57
  3369.1  119.48  3384.1  119.69  3519.1  119.66  3529.1  119.58  3539.1  120.28
  3554.1   120.4  3564.1  120.75  3894.1  120.05  3924.1  119.68  3934.1   119.3
  3954.1  120.22  3974.1  120.18  3984.1  119.75  3989.1  120.22    4000  120.31
  4074.1   120.9  4104.1   120.7  4179.1  119.86  4194.1  120.29  4374.1   120.1
  4479.1  119.55  4509.1   120.5  4518.5  120.78  4524.1  120.94  4569.1  119.88
  4619.1  119.46  4659.1  119.49  4664.1  119.67  4696.8  119.91  4703.6  119.93
  4773.4  120.11  4783.2  120.14  4822.5  119.59  4844.1  119.81  4902.3  120.41
  4931.9  120.72  4932.3  120.34  4938.9  120.43 4945.09  120.32  4945.2  120.32
 4945.31  120.32  4945.5  120.31  4961.7  120.03 4964.41  118.59  4964.5  118.54
  4969.5  115.88  4975.7  112.58  4992.3   112.2    4995  111.18  4999.6  111.58
    5003  111.31  5005.3  112.11  5007.7  112.31  5015.8  114.16  5015.9  114.18
 5016.59  116.29  5016.7  116.63  5017.9   120.3 5035.29  119.86  5035.4  119.85
 5035.51  119.85  5035.7  119.85  5041.1  119.71  5087.8  119.61  5138.6  119.51
  5155.6  119.47  5201.3  119.85  5212.2  119.59  5214.7  119.57  5258.9  119.17
  5260.3  119.18  5308.9  119.59  5309.6  118.69  5310.4  118.68  5314.6  118.62
  5337.8   119.2  5367.8  118.58  5382.8  119.47  5387.8  119.47  5442.8  118.87
  5447.8  119.18  5472.8  120.22  5487.8  119.58  5562.8  119.05  5577.8  119.58
  5612.8   118.9  5622.8  118.59  5652.8  120.04  5662.8  118.94  5672.8  118.54
  5677.8  118.64  5725.8  118.95  5730.8   119.1  5740.8  119.71  5886.7  119.23
  5971.7  118.94    6000  119.02  6031.7  119.12  6046.7  118.51  6056.7  119.79
  6071.7  120.05  6076.7  119.73  6086.7  118.84  6091.7  118.78  6156.7  120.61
  6176.7  120.42  6186.7  119.84  6191.7  119.61  6201.7   119.8  6206.7  120.22
    6300  119.93  6301.7  119.92  6316.7  120.32  6345.9  120.02  6370.9  121.34
  6385.9  120.68  6390.9  120.52  6782.5  120.36  7102.5  120.81  7187.5  120.71
  7297.5  120.96  7432.5  120.85  7442.5  121.06  7957.5  120.67  8012.5  120.18
  8037.5  120.67  8042.5  120.85  8062.5  120.63  8077.5  119.89  8122.5  120.01
  8147.5  120.94  8152.5  120.81  8162.5   119.9  8167.5  119.77  8212.5  120.49
  8257.5  119.62  8287.5  120.27  8287.6   121.6
BR U #Mann= 6
  1469.7      .2  1963.2     .99    4000      .1  4961.7    .035  5017.9      .1
    6000     .99
BR U Banks=4961.7,5017.9
BR D #Sta/Elev= 163
  1469.7  121.64  1484.7  120.39  1504.7  120.04  1514.7  120.76  1549.7  120.74
  1594.7  121.03  1639.7  121.14  1644.7  120.98  1684.7  119.92  1819.7  120.09
  1864.7  120.34  1879.7  120.49  1963.2   120.2  2044.7  119.91  2059.7  119.78
  2479.7   120.9  2554.7  120.79  2584.7  121.04  2614.7   119.7  2879.1   118.8
  2899.1  119.26  2959.1  118.55  3049.1   120.7  3154.1  119.97  3234.1  119.52
  3369.1  119.43  3384.1  119.64  3519.1  119.61  3529.1  119.53  3539.1  120.23
  3554.1  120.35  3564.1   120.7  3894.1     120  3924.1  119.63  3934.1  119.25
  3954.1  120.17  3974.1  120.13  3984.1   119.7  3989.1  120.17    4000  120.26
  4074.1  120.85  4104.1  120.65  4179.1  119.81  4194.1  120.24  4374.1  120.05
  4479.1   119.5  4509.1  120.45  4518.5  120.73  4524.1  120.89  4569.1  119.83
  4619.1  119.41  4659.1  119.44  4664.1  119.62  4696.8  119.86  4703.6  119.88
  4773.4  120.06  4783.2  120.09  4822.5  119.54  4844.1  119.76  4902.3  120.36
  4931.9  120.67  4932.3  120.29  4938.9  120.38 4945.09  120.27  4945.2  120.27
 4945.31  120.27  4945.5  120.26  4961.7  119.98 4964.41  118.54  4964.5  118.49
  4969.5  115.83  4975.7  112.53  4992.3  112.15    4995  111.13  4999.6  111.53
    5003  111.26  5005.3  112.06  5007.7  112.26  5015.8  114.11  5015.9  114.13
 5016.59  116.24  5016.7  116.58  5017.9  120.25 5035.29  119.81  5035.4   119.8
 5035.51   119.8  5035.7   119.8  5041.1  119.66  5087.8  119.56  5138.6  119.46
  5155.6  119.42  5201.3   119.8  5212.2  119.54  5214.7  119.52  5258.9  119.12
  5260.3  119.13  5308.9  119.54  5309.6  118.64  5310.4  118.63  5314.6  118.57
  5337.8  119.15  5367.8  118.53  5382.8  119.42  5387.8  119.42  5442.8  118.82
  5447.8  119.13  5472.8  120.17  5487.8  119.53  5562.8     119  5577.8  119.53
  5612.8  118.85  5622.8  118.54  5652.8  119.99  5662.8  118.89  5672.8  118.49
  5677.8  118.59  5725.8   118.9  5730.8  119.05  5740.8  119.66  5886.7  119.18
  5971.7  118.89    6000  118.97  6031.7  119.07  6046.7  118.46  6056.7  119.74
  6071.7     120  6076.7  119.68  6086.7  118.79  6091.7  118.73  6156.7  120.56
  6176.7  120.37  6186.7  119.79  6191.7  119.56  6201.7  119.75  6206.7  120.17
    6300  119.88  6301.7  119.87  6316.7  120.27  6345.9  119.97  6370.9  121.29
  6385.9  120.63  6390.9  120.47  6782.5  120.31  7102.5  120.76  7187.5  120.66
  7297.5  120.91  7432.5   120.8  7442.5  121.01  7957.5  120.62  8012.5  120.13
  8037.5  120.62  8042.5   120.8  8062.5  120.58  8077.5  119.84  8122.5  119.96
  8147.5  120.89  8152.5  120.76  8162.5  119.85  8167.5  119.72  8212.5  120.44
  8257.5  119.57  8287.5  120.22  8287.6  121.55
BR D #Mann= 6
  1469.7      .2  1963.2     .99    4000      .1  4961.7    .035  5017.9      .1
    6000     .99
BR D Banks=4961.7,5017.9
BC Design=,, 0 ,, 0 ,,,,,,
BC HTab HWMax=121.7
BC Use User HTab Curves=0
BC User HTab FreeFlow(D)= 0

Type RM Length L Ch R = 1 ,218046.7,584.9,584.9,584.9
BEGIN DESCRIPTION:
Downstream Section of Bridge/Culvert/Weir
END DESCRIPTION:
XS GIS Cut Line= 6
      3058707.28     13911420.37      3058890.68     13908118.87
      3059034.36     13907540.27      3059067.03     13906543.28
      3059012.33      13906128.5      3059104.37     13904633.56
#Sta/Elev= 30
  1469.7  121.61  1504.7  120.01  1963.2  120.17  2584.7  121.01  2614.7  119.67
  2959.1  118.52  3049.1  120.67  3369.1   119.4    4000  120.23  4961.7  119.95
  4975.7   112.5    4995   111.1  5015.9   114.1  5017.9  120.22  5314.6  118.54
  5472.8  120.14  5622.8  118.51  5652.8  119.96  5672.8  118.46    6000  118.94
  6046.7  118.43  6071.7  119.97  6091.7   118.7  6156.7  120.53  6345.9  119.94
  6370.9  121.26  8147.5  120.86  8257.5  119.54  8287.5  120.19  8287.6  121.52
#Mann= 6 , 1 , 0
  1469.7      .2       0  1963.2     .99       0    4000      .1       0
  4961.7    .035       0  5017.9      .1       0    6000     .99       0
#XS Ineff= 4 ,-1
    1473    4000     121  4000.1    4952   120.4    5030    6000   119.8
  6000.1  8288.3     121
Permanent Ineff=
       F       F       F       F
Bank Sta=4961.7,5017.9
XS Rating Curve= 0 ,0
Exp/Cntr=0.5,0.3

Type RM Length L Ch R = 1 ,217461.8,368.5,372.3,383.7
BEGIN DESCRIPTION:
Cross Section 217461.8 - Interpolated
END DESCRIPTION:
XS GIS Cut Line= 6
      3059253.77      13910405.2      3059500.38      13909229.1
      3059538.32      13907863.3      3059415.01     13906402.66
      3059519.35      13905444.7      3059484.71     13904600.27
#Sta/Elev= 30
  2623.7  121.68  3358.7  118.64    3853  120.64  3905.4  118.77  4085.4  118.52
  4105.4  119.79  4130.4  117.87  4150.4  119.24  4475.4   119.5  4510.4  121.13
  4790.4   119.3  4899.1  120.64    4983  118.89  4990.1  115.63  4994.1  110.25
  4998.6   109.2  5005.3  110.39  5011.8  116.11    5020  119.79  5024.1  118.91
  5039.1  121.87  5084.1   119.7  5174.1  118.83  5938.3  119.95  6183.3  119.24
  6198.3  117.35  6213.3  119.52    6500  120.23  8457.8  119.56  8472.9   121.2
#Mann= 5 , 1 , 0
  2623.7     .99       0    3853      .1       0    4983    .035       0
    5020      .1       0    6500     .99       0
Bank Sta=4983,5020
XS Rating Curve= 0 ,0
Exp/Cntr=0.3,0.1

Type RM Length L Ch R = 1 ,217089.5,460.9,628.6,748.3
BEGIN DESCRIPTION:
Cross Section 217089.5
END DESCRIPTION:
XS GIS Cut Line= 6
      3059626.38     13910582.67      3059873.43     13909154.49
      3059851.19     13908318.16      3059860.09     13908082.38
      3059900.12     13907299.43      3059972.93     13904890.49
#Sta/Elev= 30
  2552.3   121.5  3412.3   119.1  3552.3   120.9  3722.3   119.1  3842.3   120.8
    4000   120.4  4141.7   120.4  4201.7   119.3  4211.7   118.1  4321.7   119.6
  4731.7     118  4761.7   119.6    4983  117.68  4990.1  114.42  4994.1  109.04
  4998.6  107.99  5005.3  109.18  5011.8   114.9    5020  118.58  5044.8  118.44
  5058.3   120.3  6278.2   118.1    6500  119.46  6968.2     119  7228.2     120
  7258.2     122  7298.2   119.9  7728.2   118.8  8268.2   119.6  8268.3   121.6
#Mann= 5 , 1 , 0
  2552.3     .99       0    4000      .1       0    4983    .035       0
    5020      .1       0    6500     .99       0
Bank Sta=4983,5020
XS Rating Curve= 0 ,0
Exp/Cntr=0.3,0.1

Type RM Length L Ch R = 1 ,216460.9,490.4,524.5,626.9
BEGIN DESCRIPTION:
Cross Section 216460.9 - Interpolated
END DESCRIPTION:
XS GIS Cut Line= 6
      3059690.07     13910642.31      3060059.97     13909902.51
      3060268.64     13909703.33      3060439.36     13908403.93
      3060543.69     13908052.99      3060704.93     13904553.14
#Sta/Elev= 30
  2490.4  121.49  2878.6   120.5  3327.5  120.24  3472.5  118.16  3517.5   119.6
  4464.5  118.75    4876  117.31    4896  119.71  4936.6  121.35  4975.3   119.2
  4995.6  107.48  4999.2  107.19  5004.3  107.55  5012.5  114.83  5021.5  118.85
  5031.6  118.01  5051.6  121.19  5166.6  116.91  5191.6  119.87  5221.6  118.24
  5332.7  119.52  5717.7  118.18  6362.7  119.53  6467.7  117.04  6697.7  119.79
  6861.9  118.82  8571.7  117.86  8767.8  118.24  8786.4  118.66  8786.5  120.66
#Mann= 6 , 1 , 0
  2490.4      .2       0  2878.6     .12       0  4464.5      .1       0
  4975.3    .035       0  5021.5      .1       0  6861.9     .99       0
#XS Ineff= 2 , 0
       0  4134.5   120.7  6689.8       0   120.2
Permanent Ineff=
       F       F
Bank Sta=4975.3,5021.5
XS Rating Curve= 0 ,0
Exp/Cntr=0.3,0.1

Type RM Length L Ch R = 1 ,215936.4,648.6,610,421.8
BEGIN DESCRIPTION:
Cross Section 215936.4
END DESCRIPTION:
XS GIS Cut Line= 6
       3059757.5     13910664.62      3060533.18     13909684.27
      3060952.44     13908533.44      3061512.88      13906210.4
      3061564.21     13905654.23      3061594.01     13904627.95
#Sta/Elev= 30
  2462.4   121.4  2878.6  119.85  3102.4   118.1  3132.4   119.7  3912.5   119.1
  4262.5   120.7  4386.4   119.8  4426.4     117  4464.5  117.62  4736.4   117.7
  4866.4   119.6  4975.3  118.54  4995.6  106.82  4999.2  106.53  5004.3  106.89
  5012.5  114.17  5021.6  118.19  5202.8   119.4  5232.8   117.7  5342.8   119.9
  5582.8   118.3  5812.8   119.2  5942.8   117.3  6549.8   118.7  6569.8   117.2
  6599.8   118.9  6861.9   118.6  8765.7   117.6    8911   118.5  8912.4   120.3
#Mann= 6 , 1 , 0
  2462.4      .2       0  2878.6     .12       0  4464.5      .1       0
  4975.3    .035       0  5021.6      .1       0  6861.9     .99       0
#XS Ineff= 2 , 0
       0  4262.5   120.7  6599.8       0   119.2
Permanent Ineff=
       F       F
Bank Sta=4975.3,5021.6
XS Rating Curve= 0 ,0
Exp/Cntr=0.3,0.1

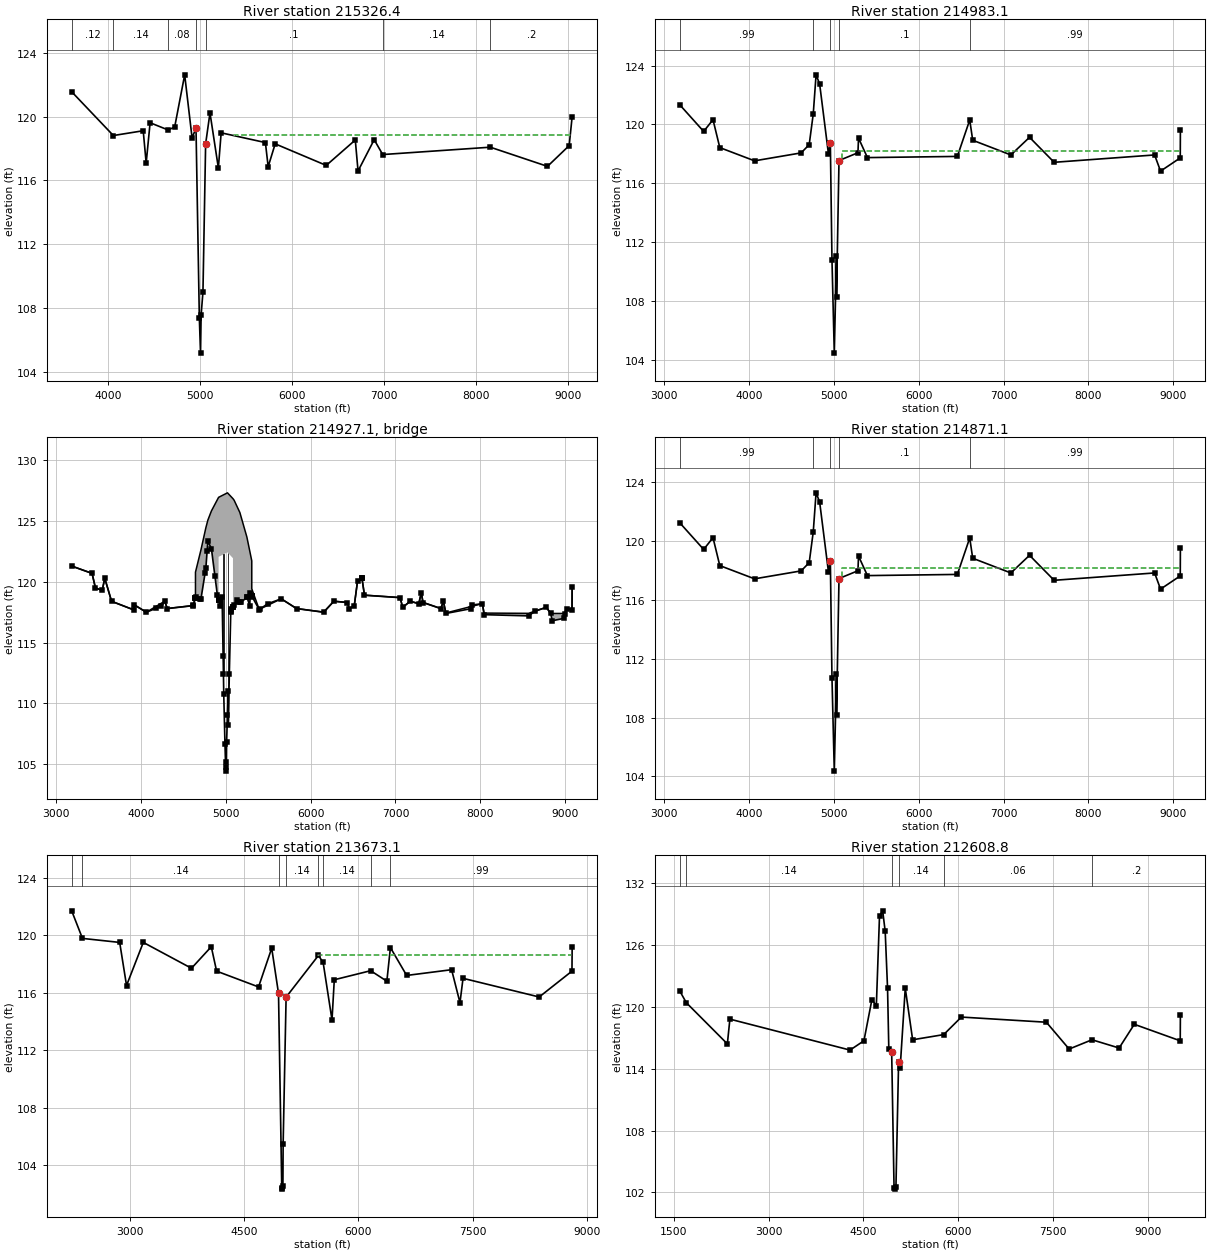
Type RM Length L Ch R = 1 ,215326.4,382.1,343.3,251.2
BEGIN DESCRIPTION:
Cross Section 215326.4-Interpolated
END DESCRIPTION:
XS GIS Cut Line= 4
      3061188.79     13910002.47      3061531.64     13908755.77
      3061584.97     13908435.78      3061865.17     13904619.74
#Sta/Elev= 30
  3601.9  121.55    4055  118.81  4379.8  119.11    4412  117.09  4454.9  119.61
  4650.3  119.16    4722  119.34  4830.9  122.61  4911.6  118.65    4954  119.29
  4990.4  107.39  5003.3  105.19  5009.7  107.58  5029.6  109.01  5058.8  118.29
  5106.1  120.23  5197.3  116.78  5227.6  118.98  5708.9  118.37    5739  116.86
  5815.3  118.29  6370.7  116.94  6686.6  118.53  6716.6  116.59  6892.1  118.55
  6984.9  117.62  8155.1  118.08  8777.2  116.88  9013.1  118.18  9045.6     120
#Mann= 7 , 1 , 0
  3601.9     .12       0    4055     .14       0  4650.3     .08       0
    4954    .035       0  5058.8      .1       0  6984.9     .14       0
  8155.1      .2       0
#XS Ineff= 2 , 0
       0  4877.6   120.3    5363       0  118.84
Permanent Ineff=
       F       F
Bank Sta=4954,5058.8
XS Rating Curve= 0 ,0
Exp/Cntr=0.5,0.3

Type RM Length L Ch R = 1 ,214983.1,112,112,112
BEGIN DESCRIPTION:
Upstream Section of Bridge/Culvert/Weir
END DESCRIPTION:
XS GIS Cut Line= 6
      3061145.84     13910318.47      3061741.43     13909661.02
      3061791.47      13909279.9      3061876.85     13908753.72
      3061960.16     13906578.57      3062054.44     13904663.11
#Sta/Elev= 30
  3183.4  121.32  3463.4  119.52  3573.4  120.32  3653.4  118.42  4063.4  117.52
  4612.5  118.06  4707.4  118.62  4755.2  120.71  4788.5  123.37  4830.6  122.75
    4934  118.01  4956.7  118.75    4976  110.78  5003.3  104.44    5029  111.06
  5029.6  108.26  5058.8  117.54  5282.3  118.07  5288.8  119.07  5393.9  117.74
  6453.9  117.82    6600   120.3    6635  118.92    7085  117.92    7305  119.12
    7595  117.42  8779.4  117.92  8849.4  116.82  9081.8  117.72  9083.4  119.62
#Mann= 5 , 1 , 0
  3183.4     .99       0  4755.2      .1       0  4956.7    .035       0
  5058.8      .1       0    6600     .99       0
#XS Ineff= 2 , 0
       0    4900   118.9  5098.2       0   118.2
Permanent Ineff=
       F       F
Bank Sta=4956.7,5058.8
XS Rating Curve= 0 ,0
Exp/Cntr=0.5,0.3

Type RM Length L Ch R = 3 ,214927.1,,,
BEGIN DESCRIPTION:
GESSNER ROAD
Structure ID: P00-88
END DESCRIPTION:
Bridge Culvert--1,0,-1,-1, 0
Deck Dist Width WeirC Skew NumUp NumDn MinLoCord MaxHiCord MaxSubmerge Is_Ogee
10,92,2.6,0, 60, 60, , , 0.95, 0, 1,1,,
  3183.4  3423.4  3463.4  3543.4  3573.4  3653.4  3913.4  3923.4  4063.4  4280.4
  4310.4  4612.5 4642.59  4642.7  4707.4  4764.9  4788.5  4830.6 4915.31  4915.4
  5019.9 5084.79  5084.9  5098.3    5166  5248.7  5282.3  5288.8  5306.4 5306.51
  5393.9  5653.9  5833.9  6153.9  6273.9  6433.9  6453.9  6513.9  6553.9    6605
    6635    7055    7085    7175    7275    7305    7325    7535    7565    7595
    8025    8045  8569.4  8779.4  8829.4  8849.4  8989.4  9019.4  9081.8  9083.4
   121.3   120.7   119.5   119.3   120.3   118.4   117.7   118.1   117.5  118.41
  117.81  118.05  118.67   120.8  122.64  124.45  125.08  125.84  126.96  126.96
  127.33  126.85  126.85  126.72  125.71  123.69  122.55  122.33  121.73  119.43
  117.73  118.61  117.81  117.51  118.41  118.31  117.81  118.01  120.11  120.31
  118.91  118.71  117.91  118.41  118.21  119.11  118.31  117.81  118.41  117.44
  118.21  117.43  117.41  117.91   117.4   117.4   117.4   117.8   117.7   119.6
   121.3   120.7   119.5   119.3   120.3   118.4   117.7   118.1   117.5   118.4
   117.8  118.04  118.66  118.67   118.6  121.11  123.35  122.73  118.52  122.06
  122.43  121.95  117.96  118.11  118.35  118.73  118.05  119.05  118.83  118.83
  117.72   118.6   117.8   117.5   118.4   118.3   117.8     118   120.1   120.3
   118.9   118.7   117.9   118.4   118.2   119.1   118.3   117.8   118.4   117.4
   118.2   117.3   117.2   117.9   117.4   116.8     117   117.8   117.7   119.6
  3183.4  3423.4  3463.4  3543.4  3573.4  3653.4  3913.4  3923.4  4063.4  4280.4
  4310.4  4612.5 4642.59  4642.7  4707.4  4764.9  4788.5  4830.6 4915.31  4915.4
  5019.9 5084.79  5084.9  5098.3    5166  5248.7  5282.3  5288.8  5306.4 5306.51
  5393.9  5653.9  5833.9  6153.9  6273.9  6433.9  6453.9  6513.9  6553.9    6605
    6635    7055    7085    7175    7275    7305    7325    7535    7565    7595
    8025    8045  8569.4  8779.4  8829.4  8849.4  8989.4  9019.4  9081.8  9083.4
   121.3   120.7   119.5   119.3   120.3   118.4   117.7   118.1   117.5  118.41
  117.81  118.05  118.67   120.8  122.64  124.45  125.08  125.84  126.96  126.96
  127.33  126.85  126.85  126.72  125.71  123.69  122.55  122.33  121.73  119.43
  117.73  118.61  117.81  117.51  118.41  118.31  117.81  118.01  120.11  120.31
  118.91  118.71  117.91  118.41  118.21  119.11  118.31  117.81  118.41  117.44
  118.21  117.43  117.41  117.91   117.4   117.4   117.4   117.8   117.7   119.6
  121.26  120.66  119.46  119.26  120.26  118.36  117.66  118.06  117.46  118.36
  117.76     118  118.62  118.63  118.56  121.07  123.31  122.69  118.48  122.02
  122.39  121.91  117.92  118.07  118.31  118.69  118.01  119.01  118.79  118.79
  117.68  118.56  117.76  117.46  118.36  118.26  117.76  117.96  120.06  120.26
  118.86  118.66  117.86  118.36  118.16  119.06  118.26  117.76  118.36  117.36
  118.16  117.26  117.16  117.86  117.36  116.76  116.96  117.76  117.66  119.56
Pier Skew, UpSta & Num, DnSta & Num=  ,4972.4, 2 ,4972.4, 2 , 0 , 0 , 0 ,,
     1.4     1.4
  111.09  123.42
     1.4     1.4
  111.05  123.38
Pier Skew, UpSta & Num, DnSta & Num=  ,5029, 2 ,5029, 2 , 0 , 0 , 0 ,,
     1.4     1.4
  107.27  123.37
     1.4     1.4
  107.23  123.33
Abutment Skew #Up #Dn= , 2 , 2
  4915.2  4916.7
  122.06  118.48
  4915.2  4916.7
  122.02  118.44
Abutment Skew #Up #Dn= , 2 , 2
  5082.2 5084.99
  117.93  121.95
  5082.2 5084.99
  117.89  121.91
BR Coef= 1 , 1 , 0 ,1.25, 0 ,,,0.8,0,2,0,
WSPro=,,,, 1 ,,,, 0 ,,,, 0 ,,,,-1 ,-1 ,-1 , 0 , 0 , 0 , 0 , 0
BR U #Sta/Elev= 103
  3183.4   121.3  3423.4   120.7  3463.4   119.5  3543.4   119.3  3573.4   120.3
  3653.4   118.4  3913.4   117.7  3923.4   118.1  4063.4   117.5  4180.5  117.83
  4240.4     118  4280.4   118.4  4310.4   117.8  4612.5  118.04  4615.1  118.09
 4642.59  118.66  4642.7  118.67 4642.81  118.67  4645.3  118.72  4690.3  118.63
  4707.4   118.6  4755.2  120.69  4764.9  121.11  4780.2  122.56  4788.5  123.35
  4830.6  122.73  4872.1  120.47  4900.3  118.94 4915.31  118.52  4915.4  118.51
  4915.7  118.51  4916.7  118.48    4934  117.99  4956.7  118.73  4968.7   113.9
  4972.4  112.41    4976  110.76  4990.4  106.62  4996.7  105.14  5003.3  104.42
    5007  104.72  5009.7  106.81  5019.9  109.05    5029  111.04  5029.6  108.24
  5041.8  112.43  5058.8  117.52  5061.6  117.64  5063.6  117.73  5082.2  117.93
 5084.79  117.96  5084.9  117.96  5098.3  118.11  5137.1  118.53  5140.3  118.37
    5166  118.35  5182.8  118.33  5248.7  118.73  5249.8  118.74  5282.3  118.05
  5288.8  119.05 5306.29  118.83  5306.4  118.83 5306.51  118.83  5312.1  118.76
  5393.9  117.72  5403.2  117.76  5493.9   118.2  5653.9   118.6  5833.9   117.8
  6153.9   117.5  6273.9   118.4  6433.9   118.3  6453.9   117.8  6513.9     118
  6553.9   120.1    6600  120.28  6603.9   120.3    6605   120.3    6635   118.9
    7055   118.7    7085   117.9    7175   118.4    7275   118.2    7305   119.1
    7325   118.3    7535   117.8    7565   118.4    7595   117.4    7895   117.8
    7905   118.1    8025   118.2    8045   117.3  8569.4   117.2  8649.4   117.6
  8779.4   117.9  8829.4   117.4  8849.4   116.8  8989.4     117  9003.2  117.37
  9019.4   117.8  9081.8   117.7  9083.4   119.6
BR U #Mann= 5
  3183.4     .99  4755.2      .1  4956.7    .035  5058.8      .1    6600     .99
BR U Banks=4956.7,5058.8
BR D #Sta/Elev= 103
  3183.4  121.26  3423.4  120.66  3463.4  119.46  3543.4  119.26  3573.4  120.26
  3653.4  118.36  3913.4  117.66  3923.4  118.06  4063.4  117.46  4180.5  117.79
  4240.4  117.96  4280.4  118.36  4310.4  117.76  4612.5     118  4615.1  118.05
 4642.59  118.62  4642.7  118.63 4642.81  118.63  4645.3  118.68  4690.3  118.59
  4707.4  118.56  4755.2  120.65  4764.9  121.07  4780.2  122.52  4788.5  123.31
  4830.6  122.69  4872.1  120.43  4900.3   118.9 4915.31  118.48  4915.4  118.47
  4915.7  118.47  4916.7  118.44    4934  117.95  4956.7  118.69  4968.7  113.86
  4972.4  112.37    4976  110.72  4990.4  106.58  4996.7   105.1  5003.3  104.38
    5007  104.68  5009.7  106.77  5019.9  109.01    5029     111  5029.6   108.2
  5041.8  112.39  5058.8  117.48  5061.6   117.6  5063.6  117.69  5082.2  117.89
 5084.79  117.92  5084.9  117.92  5098.3  118.07  5137.1  118.49  5140.3  118.33
    5166  118.31  5182.8  118.29  5248.7  118.69  5249.8   118.7  5282.3  118.01
  5288.8  119.01 5306.29  118.79  5306.4  118.79 5306.51  118.79  5312.1  118.72
  5393.9  117.68  5403.2  117.72  5493.9  118.16  5653.9  118.56  5833.9  117.76
  6153.9  117.46  6273.9  118.36  6433.9  118.26  6453.9  117.76  6513.9  117.96
  6553.9  120.06    6600  120.24  6603.9  120.26    6605  120.26    6635  118.86
    7055  118.66    7085  117.86    7175  118.36    7275  118.16    7305  119.06
    7325  118.26    7535  117.76    7565  118.36    7595  117.36    7895  117.76
    7905  118.06    8025  118.16    8045  117.26  8569.4  117.16  8649.4  117.56
  8779.4  117.86  8829.4  117.36  8849.4  116.76  8989.4  116.96  9003.2  117.33
  9019.4  117.76  9081.8  117.66  9083.4  119.56
BR D #Mann= 5
  3183.4     .99  4755.2      .1  4956.7    .035  5058.8      .1    6600     .99
BR D Banks=4956.7,5058.8
BC Design=,, 0 ,, 0 ,,,,,,
BC HTab HWMax=123.37
BC Use User HTab Curves=0
BC User HTab FreeFlow(D)= 0

Type RM Length L Ch R = 1 ,214871.1,1198,1198,1198
BEGIN DESCRIPTION:
Downstream Section of Bridge/Culvert/Weir
END DESCRIPTION:
XS GIS Cut Line= 6
      3061255.89     13910339.31      3061851.47     13909681.86
      3061901.51     13909300.74      3061986.89     13908774.56
       3062070.2     13906599.41      3062164.48     13904683.95
#Sta/Elev= 30
  3183.4  121.24  3463.4  119.44  3573.4  120.24  3653.4  118.34  4063.4  117.44
  4612.5  117.98  4707.4  118.54  4755.2  120.63  4788.5  123.29  4830.6  122.67
    4934  117.93  4956.7  118.67    4976   110.7  5003.3  104.36    5029  110.98
  5029.6  108.18  5058.8  117.46  5282.3  117.99  5288.8  118.99  5393.9  117.66
  6453.9  117.74    6600  120.22    6635  118.84    7085  117.84    7305  119.04
    7595  117.34  8779.4  117.84  8849.4  116.74  9081.8  117.64  9083.4  119.54
#Mann= 5 , 1 , 0
  3183.4     .99       0  4755.2      .1       0  4956.7    .035       0
  5058.8      .1       0    6600     .99       0
#XS Ineff= 2 , 0
       0    4900   118.9  5098.2       0   118.2
Permanent Ineff=
       F       F
Bank Sta=4956.7,5058.8
XS Rating Curve= 0 ,0
Exp/Cntr=0.5,0.3

Type RM Length L Ch R = 1 ,213673.1,727,1064.3,1171.1
BEGIN DESCRIPTION:
Cross Section 213673.1
END DESCRIPTION:
XS GIS Cut Line= 6
      3061149.26     13910407.16      3062590.44     13909778.25
      3063047.19     13909358.04      3063175.08     13909029.18
      3063202.49     13908508.48      3062950.47      13905014.9
#Sta/Elev= 30
  2235.2   121.7  2376.5  119.78  2865.2   119.5  2955.2   116.5  3175.2   119.5
  3807.6   117.7  4067.6   119.2  4137.6   117.5  4688.2   116.4  4861.1   119.1
  4950.3  115.95  4992.9   102.4  5000.1  102.32    5008  102.55  5010.9  105.45
    5050  115.69    5474  118.59  5535.8  118.11  5652.5   114.1  5682.5   116.9
  6159.9  117.53  6372.5   116.8  6419.2  119.14  6632.5   117.2  7222.5   117.6
  7332.5   115.3  7372.5     117  8372.5   115.7  8802.5   117.5  8805.2   119.2
#Mann= 8 , 1 , 0
  2235.2     .12       0  2376.5     .14       0  4950.3    .035       0
    5050     .14       0    5474     .06       0  5535.8     .14       0
  6159.9     .06       0  6419.2     .99       0
#XS Ineff= 2 , 0
       0  4861.1   119.1  5472.5       0   118.6
Permanent Ineff=
       F       F
Bank Sta=4950.3,5050
XS Rating Curve= 0 ,0
Exp/Cntr=0.3,0.1

Type RM Length L Ch R = 1 ,212608.8,199.4,548.2,1063.9
BEGIN DESCRIPTION:
Cross Section 212608.8
END DESCRIPTION:
XS GIS Cut Line= 6
      3061179.88     13910452.39      3063978.97      13909504.2
       3064170.8     13909239.29      3064115.97     13907994.43
      3063703.23     13907209.22      3063682.82     13904720.54
#Sta/Elev= 30
  1599.6   121.5  1701.1  120.39  2349.6   116.4  2389.6   118.8  4288.7   115.8
  4508.7   116.7  4634.9   120.7  4704.9   120.1  4754.9   128.8  4804.9   129.3
  4844.9   127.3    4882   121.8    4902   115.9  4947.2  115.62  4984.8  102.43
  4998.8  102.32  5014.8  102.56    5057  114.69  5081.4  114.07    5162   121.8
  5278.8   116.8  5769.6   117.3  6048.8     119  7392.8   118.5  7752.8   115.9
  8114.2   116.8  8542.8     116  8782.8   118.3    9509   116.7  9511.6   119.2
#Mann= 6 , 1 , 0
  1599.6     .12       0  1701.1     .14       0  4947.2    .035       0
    5057     .14       0  5769.6     .06       0  8114.2      .2       0
#XS Ineff= 2 , 0
       0  2389.6   118.8  6048.8       0     119
Permanent Ineff=
       F       F
Bank Sta=4947.2,5057
XS Rating Curve= 0 ,0
Exp/Cntr=0.3,0.1