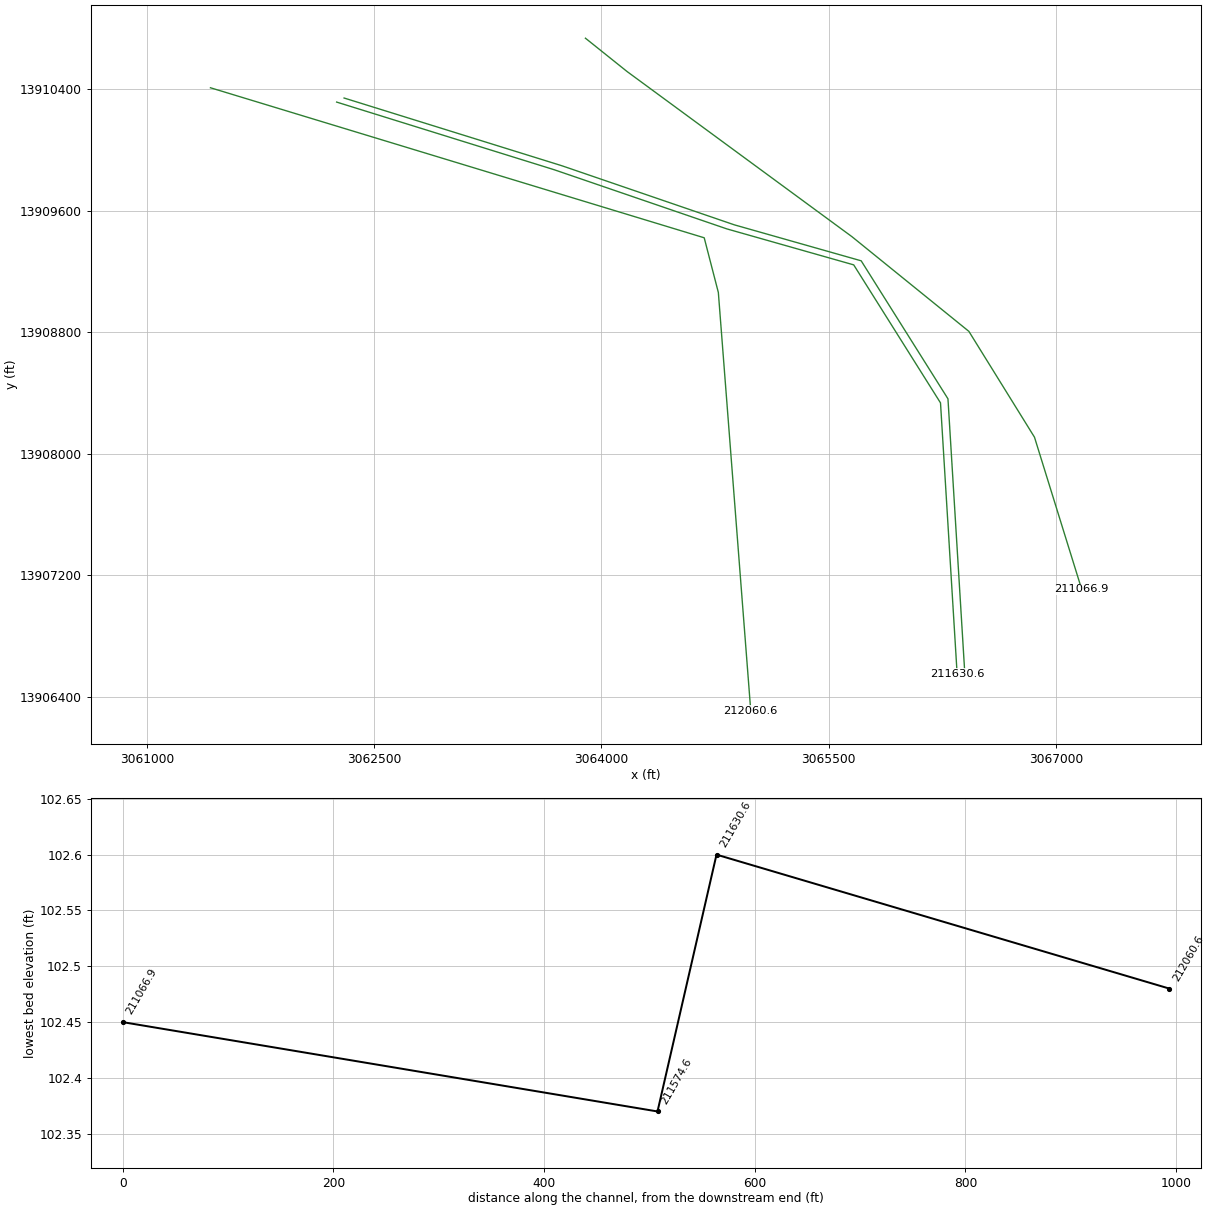
HEC-RAS study P100-00-00.prj: P100-00-00

--- P100-00-00.g01 (geometry) --- (continued)

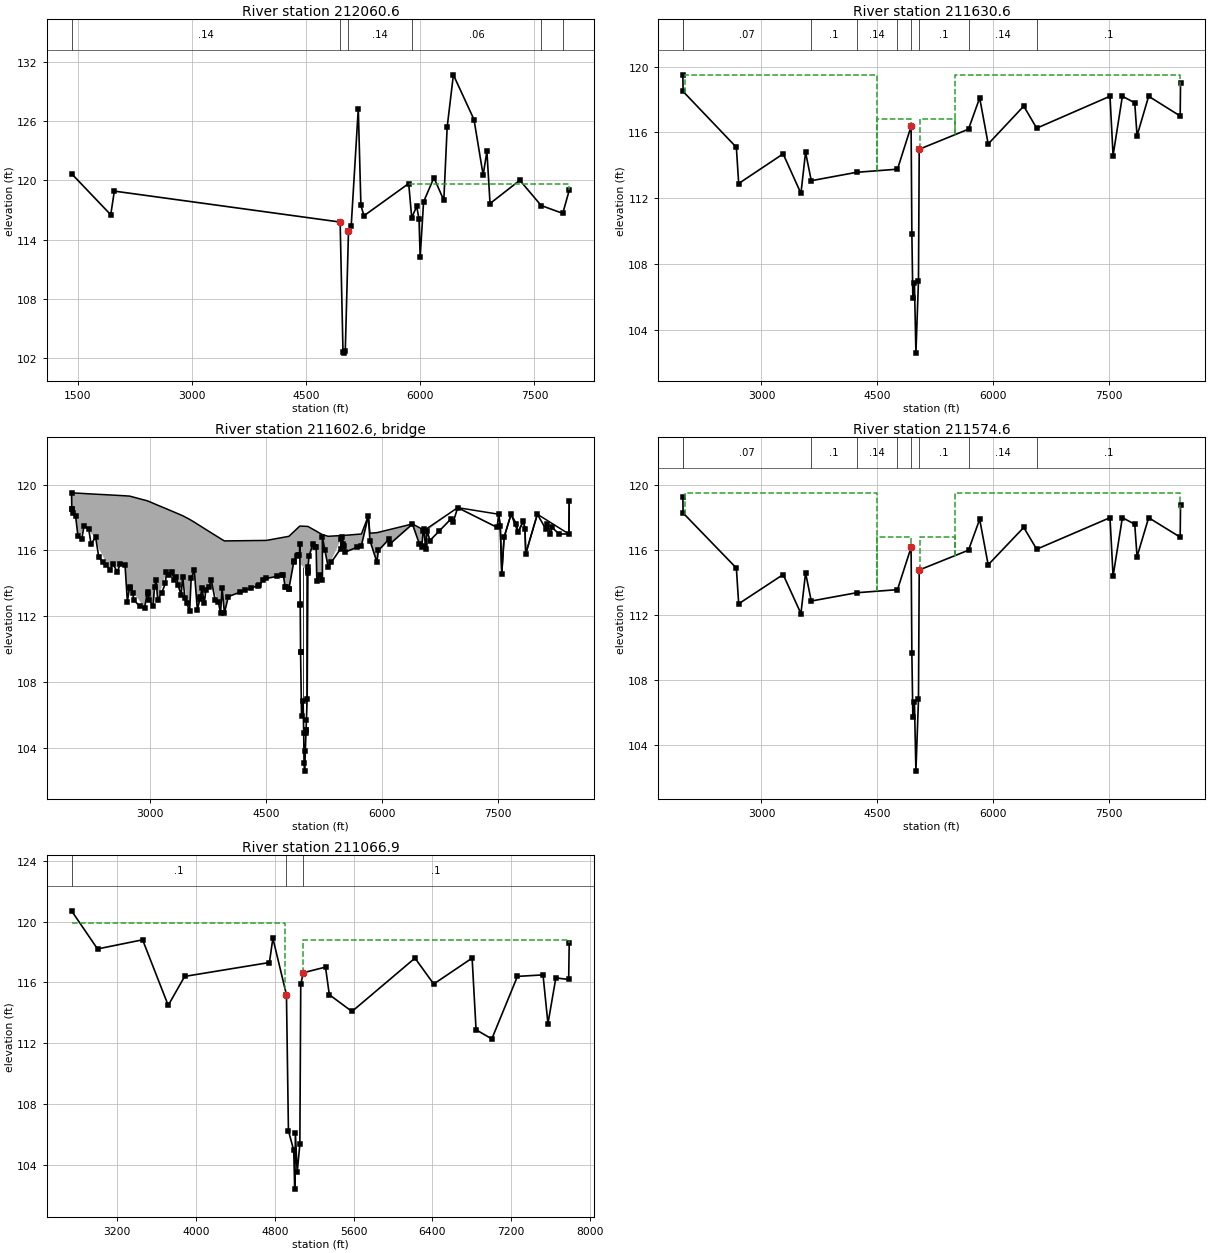
Type RM Length L Ch R = 1 ,212060.6,167,430,1254.5
BEGIN DESCRIPTION:
Cross Section 212060.6-Interpolated
END DESCRIPTION:
XS GIS Cut Line= 4
      3061419.83     13910409.79      3064678.19     13909422.41
      3064771.52     13909062.42      3064985.26     13906310.48
#Sta/Elev= 30
  1419.4  120.69  1934.2  116.52  1981.3  118.92  4947.2  115.78  4984.8  102.59
  4998.8  102.48  5014.8  102.72    5057  114.85  5092.6  115.39  5185.6  127.29
  5220.1  117.47  5260.1  116.42  5847.9  119.69  5887.2  116.23  5953.2  117.37
  5983.3  116.08  5998.3   112.2  6043.1  117.83  6178.9  120.28  6309.1  117.99
    6353   125.4  6434.6  130.72  6705.5  126.18  6825.8  120.54    6875  122.96
  6916.1  117.66  7307.3  120.02  7587.1  117.46  7871.3  116.66  7956.2     119
#Mann= 6 , 1 , 0
  1419.4     .14       0  4947.2    .035       0    5057     .14       0
  5887.2     .06       0  7587.1      .1       0  7871.3      .2       0
#XS Ineff= 2 , 0
       0  1981.3  118.92  5847.9       0  119.69
Permanent Ineff=
       F       F
Bank Sta=4947.2,5057
XS Rating Curve= 0 ,0
Exp/Cntr=0.5,0.3

Type RM Length L Ch R = 1 ,211630.6,56,56,56
BEGIN DESCRIPTION:
Upstream Section of Bridge/Culvert/Weir
END DESCRIPTION:
XS GIS Cut Line= 6
      3062252.66     13910315.53      3063690.06     13909869.69
      3064827.54     13909480.94      3065664.79     13909244.12
      3066237.52     13908335.79      3066347.13     13906553.38
#Sta/Elev= 30
  1983.1   119.5  1986.1  118.49  2675.1   115.1  2705.1   112.9  3280.3   114.7
  3510.3   112.3  3570.3   114.8    3644  113.07  4229.8  113.58    4759  113.77
 4935.18  116.37 4945.16  109.85 4957.79  105.94 4978.23  106.88 4997.48   102.6
 5030.66  107.01 5040.32  114.98  5677.7   116.2  5822.2   118.1  5932.2   115.3
  6392.2   117.6  6559.5  116.26  7507.7   118.2  7547.7   114.6  7667.7   118.2
  7827.7   117.8  7857.7   115.8  8007.7   118.2  8415.5     117  8420.1     119
#Mann= 9 , 1 , 0
  1983.1     .14       0  1986.1     .07       0    3644      .1       0
  4229.8     .14       0    4759      .1       0 4935.18    .035       0
 5040.32      .1       0  5677.7     .14       0  6559.5      .1       0
#XS Ineff= 4 ,-1
    2008    4500   119.5  4500.1    4930   116.8    5050    5500   116.8
  5500.1  8419.3   119.5
Permanent Ineff=
       F       F       F       F
Bank Sta=4935.18,5040.32
XS Rating Curve= 0 ,0
Exp/Cntr=0.5,0.3

Type RM Length L Ch R = 3 ,211602.6,,,
BEGIN DESCRIPTION:
MILLS ROAD - 45 degree skew
Structure ID: P00-86
END DESCRIPTION:
Bridge Culvert--1,0,-1,-1, 0
Deck Dist Width WeirC Skew NumUp NumDn MinLoCord MaxHiCord MaxSubmerge Is_Ogee
10,36,2.6,0, 60, 60, , , 0.95, 0, 1,1,,
  1983.1  1985.1  2065.1  2205.1  2485.1  2675.1  2705.1  2735.1  2926.9  2966.9
  3036.9  3076.9  3096.9  3210.3  3400.3  3420.3  3510.3  3530.3  3570.3  3610.3
  3790.3  3910.3  3930.3  3960.3  4502.8  4794.9 4935.18 4940.69 4940.78 5040.04
 5104.44 5146.72 5155.68 5227.71 5227.78  5302.2  5482.2  5522.2  5732.2  5822.2
  5842.2  5932.2  6392.2  6512.2  6542.2  6562.2  6582.2  6977.7  7507.7  7527.7
  7547.7  7577.7  7667.7  7757.7  7827.7  7847.7  7857.7  8007.7  8415.5  8420.1
   119.5   119.5  119.48  119.44  119.37  119.32  119.31   119.3  119.06  119.01
  118.87  118.79  118.75  118.53  118.15  118.11  117.89  117.83  117.72   117.6
  117.07  116.72  116.66  116.58  116.61  116.86  117.48  117.48  117.48  117.46
  117.29  117.18  117.15  116.96  116.96  116.86  116.91  116.92     117  118.11
  117.05  117.08  117.61  117.31  117.32  117.33  117.34   118.6   118.2   117.5
   114.6   116.8   118.2   117.1   117.8   117.3   115.8   118.2     117     119
   119.5   118.5   116.9   117.3   114.8   115.1   112.9   113.8   112.5   113.5
   112.6   114.2     113   114.7   113.3   114.4   112.3   114.3   114.8   112.4
   114.2   112.2   113.7   112.2   114.3  113.69  116.37  112.77  115.18  114.75
  116.41  116.19  114.15  114.21  116.79     115   116.8   115.9   116.3   118.1
   116.6   115.3   117.6   116.2   117.3   116.1   117.2   118.6   118.2   117.5
   114.6   116.8   118.2   117.1   117.8   117.3   115.8   118.2     117     119
  1983.1  1985.1  2065.1  2205.1  2485.1  2675.1  2705.1  2735.1  2926.9  2966.9
  3036.9  3076.9  3096.9  3210.3  3400.3  3420.3  3510.3  3530.3  3570.3  3610.3
  3790.3  3910.3  3930.3  3960.3  4502.8  4794.9 4935.18 4940.69 4940.78 5040.04
 5104.44 5146.72 5155.68 5227.71 5227.78  5302.2  5482.2  5522.2  5732.2  5822.2
  5842.2  5932.2  6392.2  6512.2  6542.2  6562.2  6582.2  6977.7  7507.7  7527.7
  7547.7  7577.7  7667.7  7757.7  7827.7  7847.7  7857.7  8007.7  8415.5  8420.1
   119.5   119.5  119.48  119.44  119.37  119.32  119.31   119.3  119.06  119.01
  118.87  118.79  118.75  118.53  118.15  118.11  117.89  117.83  117.72   117.6
  117.07  116.72  116.66  116.58  116.61  116.86  117.48  117.48  117.48  117.46
  117.29  117.18  117.15  116.96  116.96  116.86  116.91  116.92     117  118.11
  117.05  117.08  117.61  117.31  117.32  117.33  117.34   118.6   118.2   117.5
   114.6   116.8   118.2   117.1   117.8   117.3   115.8   118.2     117     119
  119.27  118.27  116.67  117.07  114.57  114.87  112.67  113.57  112.27  113.27
  112.37  113.97  112.77  114.47  113.07  114.17  112.07  114.07  114.57  112.17
  113.97  111.97  113.47  111.97  114.07  113.46  116.14  112.54  114.95  114.52
  116.18  115.96  113.92  113.98  116.56  114.77  116.57  115.67  116.07  117.87
  116.37  115.07  117.37  115.97  117.07  115.87  116.97  118.37  117.97  117.27
  114.37  116.57  117.97  116.87  117.57  117.07  115.57  117.97  116.77  118.77
Pier Skew, UpSta & Num, DnSta & Num=  ,4978.2, 2 ,4978.2, 2 , 0 , 0 , 0 ,,
     1.4     1.4
  105.69  116.19
     1.4     1.4
  105.46  115.96
Pier Skew, UpSta & Num, DnSta & Num=  ,5016.7, 2 ,5016.7, 2 , 0 , 0 , 0 ,,
     1.4     1.4
  104.06  116.21
     1.4     1.4
  103.83  115.98
Abutment Skew #Up #Dn= , 2 , 2
 4940.58 4945.26
  115.18  109.82
 4940.58 4945.26
  114.95  109.59
Abutment Skew #Up #Dn= , 2 , 2
 5016.66 5040.13
  105.12  115.16
 5016.66 5040.13
  104.89  114.93
BR Coef= 1 , 1 , 0 ,1.25, 0 ,,,0.8,0,2,0,
WSPro=,,,, 1 ,,,, 0 ,,,, 0 ,,,,-1 ,-1 ,-1 , 0 , 0 , 0 , 0 , 0
BR U #Sta/Elev= 157
  1983.1   119.5  1985.1   118.5  1986.1  118.49  2005.1   118.3  2035.1   118.1
  2065.1   116.9  2115.1   116.7  2145.1   117.5  2205.1   117.3  2235.1   116.4
  2295.1   116.8  2335.1   115.6  2385.1   115.3  2435.1   115.1  2485.1   114.8
  2515.1   115.2  2575.1   114.7  2615.1   115.2  2675.1   115.1  2705.1   112.9
  2735.1   113.8  2743.1  113.72  2775.1   113.4  2786.9     113  2866.9   112.6
  2926.9   112.5  2966.9   113.5  2973.1  113.35  2986.9     113  3036.9   112.6
  3056.9   113.8  3076.9   114.2  3096.9     113  3146.9   113.4  3196.9     114
  3210.3   114.7  3240.3   114.5  3280.3   114.7  3310.3   114.2  3340.3   114.4
  3360.3   113.9  3400.3   113.3  3420.3   114.4  3450.3   113.1  3473.1   112.8
  3510.3   112.3  3530.3   114.3  3570.3   114.8  3610.3   112.4    3644  113.07
  3650.3   113.2  3670.3   113.7  3700.3   112.8  3720.3   113.6  3760.3   113.8
  3790.3   114.2  3840.3     113  3880.3   112.9  3910.3   112.2  3930.3   113.7
  3960.3   112.2  4010.3   113.2    4158  113.46  4229.8  113.58    4298   113.7
    4398  113.87  4412.8   113.9  4462.8   114.2  4502.8   114.3  4635.9  114.42
  4706.1  114.48  4722.8   114.5 4744.43   113.8    4759  113.77  4794.8  113.69
  4794.9  113.69 4856.64  115.28  4866.1  115.36 4905.01  115.69  4914.1  115.71
  4927.9  115.75 4935.18  116.37 4940.69  112.77 4940.78  112.71 4945.16  109.85
 4945.26  109.82 4957.79  105.94 4978.23  106.88 4985.72  104.89 4990.34  103.11
 4997.48   102.6 5006.16  103.81 5014.21  104.92 5016.56  105.11 5016.66  105.12
  5021.1  105.72 5030.66  107.01 5039.93  114.66 5040.04  114.75 5040.32  114.98
 5055.65  115.65 5104.44  116.41  5137.6  116.24 5146.72  116.19 5155.68  114.15
 5195.44  114.49 5227.71  114.21 5227.78  116.79  5259.3  116.03  5302.2     115
  5341.6  115.27  5462.2   116.1  5472.2   116.7  5482.2   116.8  5492.2   116.4
  5512.2   116.3  5522.2   115.9  5677.7   116.2  5732.2   116.3  5822.2   118.1
  5842.2   116.6  5932.2   115.3  5952.2     116  6092.2   116.7  6102.2   116.4
  6392.2   117.6  6482.2   116.4  6512.2   116.2  6532.2   117.2  6542.2   117.3
  6559.5  116.26  6562.2   116.1  6582.2   117.2  6617.7   116.6  6734.3  117.16
  6887.7   117.9  6917.7   117.7  6977.7   118.6  7487.7   117.4  7507.7   118.2
  7527.7   117.5  7547.7   114.6  7577.7   116.8  7667.7   118.2  7737.7   117.6
  7757.7   117.1  7827.7   117.8  7847.7   117.3  7857.7   115.8  8007.7   118.2
  8117.7   117.3  8137.7   117.6  8177.7     117  8197.7   117.4  8287.7     117
  8415.5     117  8420.1     119
BR U #Mann= 9
  1983.1     .14  1986.1     .07    3644      .1  4229.8     .14    4759      .1
 4935.18    .035 5040.32      .1  5677.7     .14  6559.5      .1
BR U Banks=4935.18,5040.32
BR D #Sta/Elev= 157
  1983.1  119.27  1985.1  118.27  1986.1  118.26  2005.1  118.07  2035.1  117.87
  2065.1  116.67  2115.1  116.47  2145.1  117.27  2205.1  117.07  2235.1  116.17
  2295.1  116.57  2335.1  115.37  2385.1  115.07  2435.1  114.87  2485.1  114.57
  2515.1  114.97  2575.1  114.47  2615.1  114.97  2675.1  114.87  2705.1  112.67
  2735.1  113.57  2743.1  113.49  2775.1  113.17  2786.9  112.77  2866.9  112.37
  2926.9  112.27  2966.9  113.27  2973.1  113.12  2986.9  112.77  3036.9  112.37
  3056.9  113.57  3076.9  113.97  3096.9  112.77  3146.9  113.17  3196.9  113.77
  3210.3  114.47  3240.3  114.27  3280.3  114.47  3310.3  113.97  3340.3  114.17
  3360.3  113.67  3400.3  113.07  3420.3  114.17  3450.3  112.87  3473.1  112.57
  3510.3  112.07  3530.3  114.07  3570.3  114.57  3610.3  112.17    3644  112.84
  3650.3  112.97  3670.3  113.47  3700.3  112.57  3720.3  113.37  3760.3  113.57
  3790.3  113.97  3840.3  112.77  3880.3  112.67  3910.3  111.97  3930.3  113.47
  3960.3  111.97  4010.3  112.97    4158  113.23  4229.8  113.35    4298  113.47
    4398  113.64  4412.8  113.67  4462.8  113.97  4502.8  114.07  4635.9  114.19
  4706.1  114.25  4722.8  114.27 4744.43  113.57    4759  113.54  4794.8  113.46
  4794.9  113.46 4856.64  115.05  4866.1  115.13 4905.01  115.46  4914.1  115.48
  4927.9  115.52 4935.18  116.14 4940.69  112.54 4940.78  112.48 4945.16  109.62
 4945.26  109.59 4957.79  105.71 4978.23  106.65 4985.72  104.66 4990.34  102.88
 4997.48  102.37 5006.16  103.58 5014.21  104.69 5016.56  104.88 5016.66  104.89
  5021.1  105.49 5030.66  106.78 5039.93  114.43 5040.04  114.52 5040.32  114.75
 5055.65  115.42 5104.44  116.18  5137.6  116.01 5146.72  115.96 5155.68  113.92
 5195.44  114.26 5227.71  113.98 5227.78  116.56  5259.3   115.8  5302.2  114.77
  5341.6  115.04  5462.2  115.87  5472.2  116.47  5482.2  116.57  5492.2  116.17
  5512.2  116.07  5522.2  115.67  5677.7  115.97  5732.2  116.07  5822.2  117.87
  5842.2  116.37  5932.2  115.07  5952.2  115.77  6092.2  116.47  6102.2  116.17
  6392.2  117.37  6482.2  116.17  6512.2  115.97  6532.2  116.97  6542.2  117.07
  6559.5  116.03  6562.2  115.87  6582.2  116.97  6617.7  116.37  6734.3  116.93
  6887.7  117.67  6917.7  117.47  6977.7  118.37  7487.7  117.17  7507.7  117.97
  7527.7  117.27  7547.7  114.37  7577.7  116.57  7667.7  117.97  7737.7  117.37
  7757.7  116.87  7827.7  117.57  7847.7  117.07  7857.7  115.57  8007.7  117.97
  8117.7  117.07  8137.7  117.37  8177.7  116.77  8197.7  117.17  8287.7  116.77
  8415.5  116.77  8420.1  118.77
BR D #Mann= 9
  1983.1     .14  1986.1     .07    3644      .1  4229.8     .14    4759      .1
 4935.18    .035 5040.32      .1  5677.7     .14  6559.5      .1
BR D Banks=4935.18,5040.32
BC Design=,, 0 ,, 0 ,,,,,,
BC HTab HWMax=119.5
BC Use User HTab Curves=0
BC User HTab FreeFlow(D)= 0

Type RM Length L Ch R = 1 ,211574.6,507.7,507.7,507.7
BEGIN DESCRIPTION:
Downstream Section of Bridge/Culvert/Weir
END DESCRIPTION:
XS GIS Cut Line= 6
      3062301.87     13910342.25      3063739.28     13909896.41
      3064876.76     13909507.66      3065714.01     13909270.84
      3066286.74     13908362.51      3066396.34     13906580.11
#Sta/Elev= 30
  1983.1  119.27  1986.1  118.26  2675.1  114.87  2705.1  112.67  3280.3  114.47
  3510.3  112.07  3570.3  114.57    3644  112.84  4229.8  113.35    4759  113.54
 4935.18  116.14 4945.16  109.62 4957.79  105.71 4978.23  106.65 4997.48  102.37
 5030.66  106.78 5040.32  114.75  5677.7  115.97  5822.2  117.87  5932.2  115.07
  6392.2  117.37  6559.5  116.03  7507.7  117.97  7547.7  114.37  7667.7  117.97
  7827.7  117.57  7857.7  115.57  8007.7  117.97  8415.5  116.77  8420.1  118.77
#Mann= 9 , 1 , 0
  1983.1     .14       0  1986.1     .07       0    3644      .1       0
  4229.8     .14       0    4759      .1       0 4935.18    .035       0
 5040.32      .1       0  5677.7     .14       0  6559.5      .1       0
#XS Ineff= 4 ,-1
    2008    4500   119.5  4500.1    4930   116.8    5050    5500   116.8
  5500.1  8419.3   119.5
Permanent Ineff=
       F       F       F       F
Bank Sta=4935.18,5040.32
XS Rating Curve= 0 ,0
Exp/Cntr=0.5,0.3

Type RM Length L Ch R = 1 ,211066.9,580,580,580
BEGIN DESCRIPTION:
Upstream Section of Bridge/Culvert/Weir
END DESCRIPTION:
XS GIS Cut Line= 6
       3063894.4     13910735.92      3064168.99     13910516.77
      3065653.35     13909429.51      3066424.68     13908806.54
      3066857.73     13908109.84      3067169.42     13907107.98
#Sta/Elev= 30
  2735.5   120.7  2999.3   118.2    3457   118.8    3717   114.5    3884   116.4
  4744.5  117.31 4779.78   118.9 4917.54  115.19 4937.67  106.28 4991.46  104.99
 5001.47  102.45 5008.54   106.1 5026.53  103.55 5053.59  105.39 5062.65  115.87
 5088.13  116.64 5314.02  117.01  5352.7   115.2  5582.7   114.1  6222.7   117.6
  6412.7   115.9  6802.7   117.6  6842.7   112.9  7002.7   112.3  7262.7   116.4
  7522.7   116.5  7572.7   113.3  7652.7   116.3    7783   116.2  7788.7   118.6
#Mann= 3 , 1 , 0
  2735.5      .1       0 4917.54    .035       0 5088.13      .1       0
#XS Ineff= 2 , 0
       0    4903   119.9    5089       0   118.8
Permanent Ineff=
       F       F
Bank Sta=4917.54,5088.13
XS Rating Curve= 0 ,0
Exp/Cntr=0.5,0.3