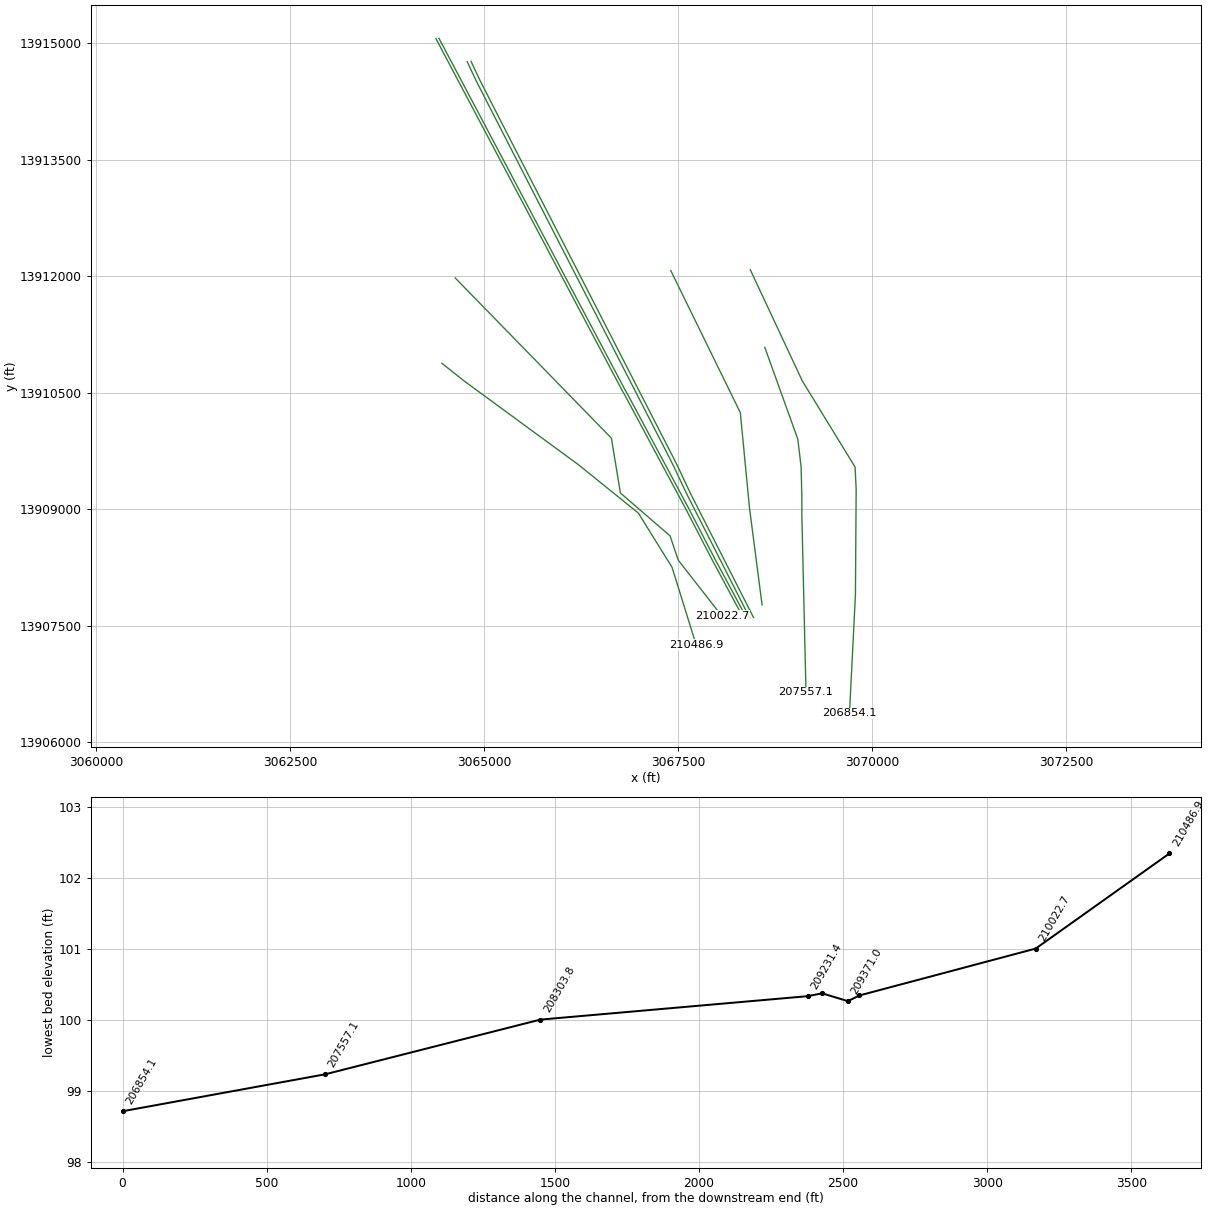
HEC-RAS study P100-00-00.prj: P100-00-00

--- P100-00-00.g01 (geometry) --- (continued)

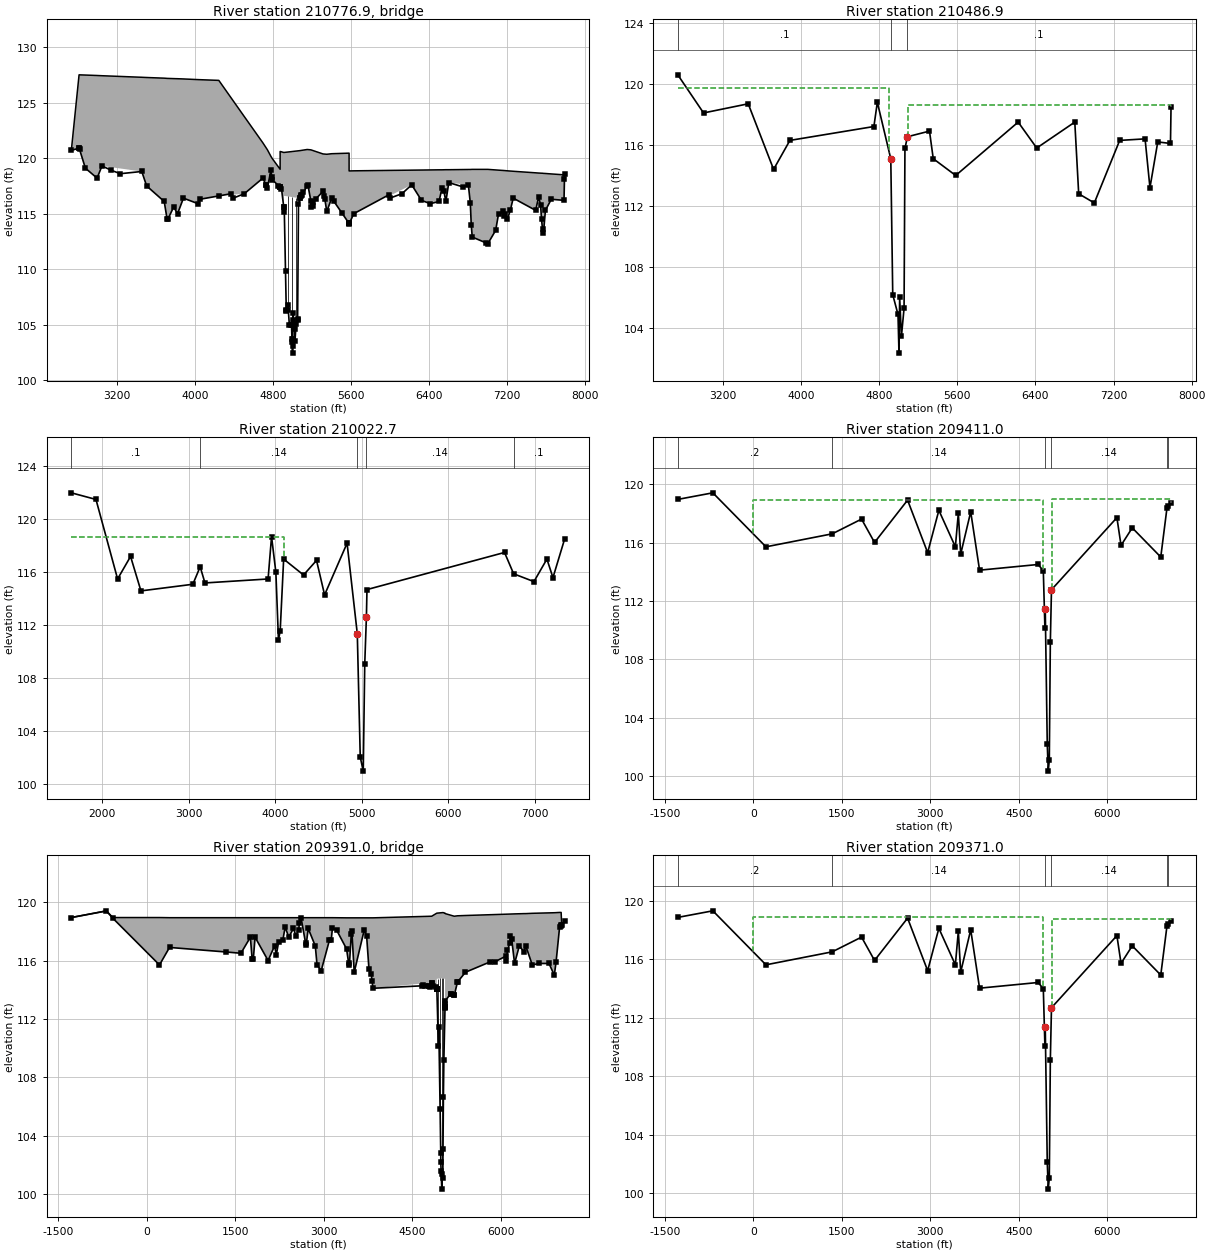
Type RM Length L Ch R = 3 ,210776.9,,,
BEGIN DESCRIPTION:
FM 249 TOMBALL PARKWAY - 45 degree skew
Structure ID: P00-84
END DESCRIPTION:
Bridge Culvert--1,0,-1,-1, 0
Deck Dist Width WeirC Skew NumUp NumDn MinLoCord MaxHiCord MaxSubmerge Is_Ogee
10,560,2.6,0, 60, 60, , , 0.95, 0, 1,1,,
  2735.5  2814.7  2879.3  2999.3  3049.3    3457    3507    3687    3717    3784
    3824    3884    4034  4246.4  4507.8  4697.8  4744.5 4779.78 4793.71 4874.59
  4874.7 4888.49 4912.27 4912.36 5079.73  5151.6 5188.86 5189.14 5314.02  5352.7
  5402.7  5581.2 5581.31  5582.7  5628.8  6222.7  6322.7  6412.7  6502.7  6532.7
  6572.7  6602.7  6802.7  6822.7  6842.7  7002.7  7082.7  7112.7  7162.7  7202.7
  7262.7  7492.7  7522.7  7542.7  7562.7  7572.7  7592.7  7652.7    7783  7788.7
   120.7   127.5  127.48  127.44  127.42  127.28  127.26   127.2  127.18  127.16
  127.15  127.13  127.07     127  123.74  121.38  120.75  120.17  119.97     119
   120.6  120.57  120.51  120.51  120.68  120.78  120.75  120.75  120.38  120.35
   120.4  120.45  118.85  118.85  118.86  118.92  118.93  118.94  118.95  118.95
  118.96  118.96  118.98  118.98  118.99  118.99  118.94  118.92  118.89  118.86
  118.82  118.68  118.66  118.65  118.64  118.63  118.62  118.58   118.5   118.6
   120.7   120.9   119.1   118.2   119.3   118.8   117.5   116.1   114.5   115.6
     115   116.4   115.9   116.6   116.8   118.2  117.31   118.9  118.07  117.37
  117.37  117.25  115.56  116.61  116.39  117.51  116.17  115.63  117.01   115.2
   116.4  114.12  114.12   114.1     115   117.6   116.2   115.9   116.1   117.3
   116.1   117.8   117.6     116   112.9   112.3   113.5     115   115.2   114.5
   116.4   115.3   116.5   115.8   113.6   113.3   115.3   116.3   116.2   118.6
  2735.5  2814.7  2879.3  2999.3  3049.3    3457    3507    3687    3717    3784
    3824    3884    4034  4246.4  4507.8  4697.8  4744.5 4779.78 4793.71 4874.59
  4874.7 4888.49 4912.27 4912.36 5079.73  5151.6 5188.86 5189.14 5314.02  5352.7
  5402.7  5581.2 5581.31  5582.7  5628.8  6222.7  6322.7  6412.7  6502.7  6532.7
  6572.7  6602.7  6802.7  6822.7  6842.7  7002.7  7082.7  7112.7  7162.7  7202.7
  7262.7  7492.7  7522.7  7542.7  7562.7  7572.7  7592.7  7652.7    7783  7788.7
   120.7   127.5  127.48  127.44  127.42  127.28  127.26   127.2  127.18  127.16
  127.15  127.13  127.07     127  123.74  121.38  120.75  120.17  119.97     119
   120.6  120.57  120.51  120.51  120.68  120.78  120.75  120.75  120.38  120.35
   120.4  120.45  118.85  118.85  118.86  118.92  118.93  118.94  118.95  118.95
  118.96  118.96  118.98  118.98  118.99  118.99  118.94  118.92  118.89  118.86
  118.82  118.68  118.66  118.65  118.64  118.63  118.62  118.58   118.5   118.6
  120.62  120.82  119.02  118.12  119.22  118.72  117.42  116.02  114.42  115.52
  114.92  116.32  115.82  116.52  116.72  118.12  117.23  118.82  117.99  117.29
  117.29  117.17  115.48  116.53  116.31  117.43  116.09  115.55  116.93  115.12
  116.32  114.04  114.04  114.02  114.92  117.52  116.12  115.82  116.02  117.22
  116.02  117.72  117.52  115.92  112.82  112.22  113.42  114.92  115.12  114.42
  116.32  115.22  116.42  115.72  113.52  113.22  115.22  116.22  116.12  118.52
Pier Skew, UpSta & Num, DnSta & Num=  ,4954.6, 2 ,4954.6, 2 , 0 , 0 , 0 ,,
     1.4     1.4
  105.62  117.53
     1.4     1.4
  105.54  117.45
Pier Skew, UpSta & Num, DnSta & Num=  ,4996.4, 2 ,4996.4, 2 , 0 , 0 , 0 ,,
     1.4     1.4
  102.53  117.46
     1.4     1.4
  102.45  117.38
Pier Skew, UpSta & Num, DnSta & Num=  ,5038, 2 ,5038, 2 , 0 , 0 , 0 ,,
     1.4     1.4
  103.94   117.6
     1.4     1.4
  103.86  117.52
Abutment Skew #Up #Dn= , 2 , 2
 4912.16 4937.77
  116.61  106.28
 4912.16 4937.77
  116.53   106.2
Abutment Skew #Up #Dn= , 2 , 2
 5053.69 5079.82
  105.51  116.78
 5053.69 5079.82
  105.43   116.7
BR Coef= 1 , 1 , 0 ,1.25, 0 ,,,0.8,0,2,0,
WSPro=,,,, 1 ,,,, 0 ,,,, 0 ,,,,-1 ,-1 ,-1 , 0 , 0 , 0 , 0 , 0
BR U #Sta/Elev= 122
  2735.5   120.7  2814.7   120.9  2815.5   120.9  2819.3   120.8  2879.3   119.1
  2999.3   118.2  3049.3   119.3    3147   118.9    3237   118.6    3457   118.8
    3507   117.5    3687   116.1    3717   114.5    3724   114.5    3784   115.6
    3824     115    3884   116.4    4034   115.9    4054   116.3  4246.4   116.6
    4374   116.8    4394   116.4  4507.8   116.8  4697.8   118.2  4730.6  117.57
  4730.9  117.57  4744.5  117.31 4779.78   118.9  4789.7  118.31 4793.71  118.07
  4856.5  117.53 4874.59  117.37  4874.7  117.37 4874.81  117.37 4888.49  117.25
 4912.27  115.56 4912.36  115.56 4917.54  115.19  4929.7  109.81 4937.57  106.32
 4937.67  106.28 4952.68  106.31 4954.64  106.79 4969.41  104.96  4985.7  104.98
 4991.46  104.99 4996.36  103.48 4999.16  103.68 5001.47  102.45 5003.36   103.1
  5004.5  103.76 5008.54   106.1 5011.62   105.4 5024.85  104.58 5026.53  103.55
 5038.01  105.03 5053.59  105.39 5053.69  105.51 5062.65  115.87 5079.62  116.38
 5079.73  116.39    5086  116.58 5088.13  116.64 5101.15  116.71  5113.9  116.91
  5151.6  117.51  5158.2  117.62 5188.86  116.17 5189.14  115.63 5211.19   115.7
 5213.43  116.08  5240.2  116.33 5314.02  117.01  5325.5  116.57  5332.7   116.3
  5352.7   115.2  5402.7   116.4  5425.4  116.11  5508.7  115.05    5581  114.12
 5581.09  114.12  5581.2  114.12 5581.31  114.12  5582.7   114.1  5628.8     115
  5988.8   116.7  5998.8   116.4  6122.7   116.8  6222.7   117.6  6322.7   116.2
  6412.7   115.9  6502.7   116.1  6532.7   117.3  6552.7     117  6572.7   116.1
  6602.7   117.8  6752.7   117.4  6802.7   117.6  6822.7     116  6832.7     114
  6842.7   112.9  6979.2  112.39  7002.7   112.3  7082.7   113.5  7112.7     115
  7162.7   115.2  7172.7   114.8  7182.7     115  7202.7   114.5  7232.7   115.3
  7262.7   116.4  7492.7   115.3  7522.7   116.5  7542.7   115.8  7552.7   114.5
  7562.7   113.6  7572.7   113.3  7592.7   115.3  7652.7   116.3    7783   116.2
  7787.6  118.14  7788.7   118.6
BR U #Mann= 3
  2735.5      .1 4917.54    .035 5088.13      .1
BR U Banks=4917.54,5088.13
BR D #Sta/Elev= 122
  2735.5  120.62  2814.7  120.82  2815.5  120.82  2819.3  120.72  2879.3  119.02
  2999.3  118.12  3049.3  119.22    3147  118.82    3237  118.52    3457  118.72
    3507  117.42    3687  116.02    3717  114.42    3724  114.42    3784  115.52
    3824  114.92    3884  116.32    4034  115.82    4054  116.22  4246.4  116.52
    4374  116.72    4394  116.32  4507.8  116.72  4697.8  118.12  4730.6  117.49
  4730.9  117.49  4744.5  117.23 4779.78  118.82  4789.7  118.23 4793.71  117.99
  4856.5  117.45 4874.59  117.29  4874.7  117.29 4874.81  117.29 4888.49  117.17
 4912.27  115.48 4912.36  115.48 4917.54  115.11  4929.7  109.73 4937.57  106.24
 4937.67   106.2 4952.68  106.23 4954.64  106.71 4969.41  104.88  4985.7   104.9
 4991.46  104.91 4996.36   103.4 4999.16   103.6 5001.47  102.37 5003.36  103.02
  5004.5  103.68 5008.54  106.02 5011.62  105.32 5024.85   104.5 5026.53  103.47
 5038.01  104.95 5053.59  105.31 5053.69  105.43 5062.65  115.79 5079.62   116.3
 5079.73  116.31    5086   116.5 5088.13  116.56 5101.15  116.63  5113.9  116.83
  5151.6  117.43  5158.2  117.54 5188.86  116.09 5189.14  115.55 5211.19  115.62
 5213.43     116  5240.2  116.25 5314.02  116.93  5325.5  116.49  5332.7  116.22
  5352.7  115.12  5402.7  116.32  5425.4  116.03  5508.7  114.97    5581  114.04
 5581.09  114.04  5581.2  114.04 5581.31  114.04  5582.7  114.02  5628.8  114.92
  5988.8  116.62  5998.8  116.32  6122.7  116.72  6222.7  117.52  6322.7  116.12
  6412.7  115.82  6502.7  116.02  6532.7  117.22  6552.7  116.92  6572.7  116.02
  6602.7  117.72  6752.7  117.32  6802.7  117.52  6822.7  115.92  6832.7  113.92
  6842.7  112.82  6979.2  112.31  7002.7  112.22  7082.7  113.42  7112.7  114.92
  7162.7  115.12  7172.7  114.72  7182.7  114.92  7202.7  114.42  7232.7  115.22
  7262.7  116.32  7492.7  115.22  7522.7  116.42  7542.7  115.72  7552.7  114.42
  7562.7  113.52  7572.7  113.22  7592.7  115.22  7652.7  116.22    7783  116.12
  7787.6  118.06  7788.7  118.52
BR D #Mann= 3
  2735.5      .1 4917.54    .035 5088.13      .1
BR D Banks=4917.54,5088.13
BC Design=,, 0 ,, 0 ,,,,,,
BC HTab HWMax=120.9
BC Use User HTab Curves=0
BC User HTab FreeFlow(D)= 0

Type RM Length L Ch R = 1 ,210486.9,464.2,464.2,464.2
BEGIN DESCRIPTION:
Downstream Section of Bridge/Culvert/Weir
END DESCRIPTION:
XS GIS Cut Line= 6
      3064456.31     13910879.66      3064730.89     13910660.51
      3066215.25     13909573.25      3066986.58     13908950.28
      3067419.63     13908253.58      3067731.32     13907251.72
#Sta/Elev= 30
  2735.5  120.59  2999.3  118.09    3457  118.69    3717  114.39    3884  116.29
  4744.5   117.2 4779.78  118.79 4917.54  115.08 4937.67  106.17 4991.46  104.88
 5001.47  102.34 5008.54  105.99 5026.53  103.44 5053.59  105.28 5062.65  115.76
 5088.13  116.53 5314.02   116.9  5352.7  115.09  5582.7  113.99  6222.7  117.49
  6412.7  115.79  6802.7  117.49  6842.7  112.79  7002.7  112.19  7262.7  116.29
  7522.7  116.39  7572.7  113.19  7652.7  116.19    7783  116.09  7788.7  118.49
#Mann= 3 , 1 , 0
  2735.5      .1       0 4917.54    .035       0 5088.13      .1       0
#XS Ineff= 2 , 0
       0    4903   119.7    5089       0   118.6
Permanent Ineff=
       F       F
Bank Sta=4917.54,5088.13
XS Rating Curve= 0 ,0
Exp/Cntr=0.5,0.3

Type RM Length L Ch R = 1 ,210022.7,628.9,611.7,483.3
BEGIN DESCRIPTION:
Cross Section 210022.7-Interpolated
END DESCRIPTION:
XS GIS Cut Line= 6
      3064627.26     13911979.11      3066639.07     13909915.68
      3066755.21     13909209.16      3067394.89     13908657.01
        3067500.     13908344.02      3068062.32     13907624.25
#Sta/Elev= 30
  1641.3     122  1926.2   121.5  2176.2   115.5  2326.2   117.2  2446.2   114.6
  3046.2   115.1    3131  116.42  3186.2   115.2  3916.2   115.5  3956.2   118.7
  4006.2     116  4036.2   110.9  4056.2   111.6  4096.2     117  4326.2   115.8
  4476.2   116.9  4569.5   114.3  4829.5   118.2  4947.6  111.37  4981.8  102.06
  5016.4     101  5033.8  109.09  5053.1  112.66  5059.5   114.7  6649.9   117.5
  6755.2  115.89  6989.9   115.3  7139.9     117  7209.9   115.6  7344.1   118.5
#Mann= 5 , 1 , 0
  1641.3      .1       0    3131     .14       0  4947.6    .035       0
  5053.1     .14       0  6755.2      .1       0
#XS Ineff= 2 , 0
       0  4100.2   118.7  6649.9       0   117.5
Permanent Ineff=
       F       F
Bank Sta=4947.6,5053.1
XS Rating Curve= 0 ,0
Exp/Cntr=0.5,0.3

Type RM Length L Ch R = 1 ,209411.0,40,40,40
BEGIN DESCRIPTION:
Upstream Section of Bridge/Culvert/Weir
END DESCRIPTION:
XS GIS Cut Line= 6
      3064378.32      13915062.6       3066774.7     13910535.23
      3066812.32     13910469.72      3067597.25     13909003.61
      3067932.88     13908355.97      3068296.11     13907679.95
#Sta/Elev= 30
 -1278.9  118.96  -685.1  119.41   214.9  115.71  1337.6   116.6  1834.9  117.61
  2054.9  116.01  2614.9  118.91  2954.9  115.31  3144.9  118.21  3424.6  115.71
  3474.6  118.01  3514.6  115.21  3684.6  118.11  3834.6  114.11  4827.3   114.5
  4914.8  114.07  4941.7  110.15  4947.6  111.48  4981.8  102.17  4998.6  100.34
  5016.4  101.11  5033.8   109.2  5053.1  112.77  6161.8  117.71  6231.8  115.81
  6421.8  117.01    6905  115.01  7010.8  118.39  7030.6  118.48    7079  118.71
#Mann= 6 , 1 , 0
 -1278.9      .2       0  1337.6     .14       0  4947.6    .035       0
  5053.1     .14       0  7010.8      .1       0  7030.6      .2       0
#XS Ineff= 2 , 0
       0    4903   118.9    5063       0     119
Permanent Ineff=
       F       F
Bank Sta=4947.6,5053.1
XS Rating Curve= 0 ,0
Exp/Cntr=0.5,0.3

Type RM Length L Ch R = 3 ,209391.0,,,
BEGIN DESCRIPTION:
NORTHERN CENTER RAILROAD
Structure ID: P00-82
END DESCRIPTION:
Bridge Culvert--1,0,-1,-1, 0
Deck Dist Width WeirC Skew NumUp NumDn MinLoCord MaxHiCord MaxSubmerge Is_Ogee
10,20,2.6,0, 60, 60, , , 0.95, 0, 1,1,,
 -1278.9  -685.1  -575.1   214.9   384.9  1594.9  1754.9  1784.9  1804.9  1834.9
  2054.9  2164.9  2194.9  2234.9  2304.9  2344.9  2404.9  2484.9  2524.9  2614.9
  2694.9  2734.9  2854.9  2884.9  2954.9  3094.9  3124.9  3144.9  3384.6  3424.6
  3474.6  3514.6  3684.6  3724.6  3764.6  3804.6  3834.6  4827.3 4914.01  4914.1
    5019 5053.39  5053.5  5055.9  5209.8  5264.5  5399.9  6091.8  6161.8  6231.8
  6311.8  6391.8  6421.8  6531.8    6815    6905    6995  7021.1  7030.6    7079
  118.95  119.41  118.95  118.95  118.94  118.94  118.94  118.94  118.94  118.94
  118.94  118.94  118.94  118.94  118.94  118.94  118.94  118.94  118.94  118.94
  118.94  118.94  118.94  118.94  118.94  118.94  118.94  118.94  118.93  118.93
  118.93  118.93  118.93  118.93  118.93  118.93  118.93  119.04  119.25  119.25
  119.29  119.25  119.25  119.22  119.04  119.07  119.09  119.18  119.19   119.2
  119.21  119.22  119.22  119.24  119.27  119.28   119.3   119.3  118.47   118.7
  118.95   119.4   118.9   115.7   116.9   116.5   117.6   116.1   116.1   117.6
     116     117   116.4   117.3   117.4   118.3   117.6   118.2   117.7   118.9
   117.1   118.2     117   115.7   115.3   117.4   117.4   118.2   116.8   115.7
     118   115.2   118.1   117.7   115.4   115.1   114.1  114.49  114.07  114.75
  114.79  114.75  112.83  113.24  113.61  114.53   115.2     116   117.7   115.8
     117   116.6     117   115.7   115.8     115   118.3  118.42  118.47   118.7
 -1278.9  -685.1  -575.1   214.9   384.9  1594.9  1754.9  1784.9  1804.9  1834.9
  2054.9  2164.9  2194.9  2234.9  2304.9  2344.9  2404.9  2484.9  2524.9  2614.9
  2694.9  2734.9  2854.9  2884.9  2954.9  3094.9  3124.9  3144.9  3384.6  3424.6
  3474.6  3514.6  3684.6  3724.6  3764.6  3804.6  3834.6  4827.3 4914.01  4914.1
    5019 5053.39  5053.5  5055.9  5209.8  5264.5  5399.9  6091.8  6161.8  6231.8
  6311.8  6391.8  6421.8  6531.8    6815    6905    6995  7021.1  7030.6    7079
  118.95  119.41  118.95  118.95  118.94  118.94  118.94  118.94  118.94  118.94
  118.94  118.94  118.94  118.94  118.94  118.94  118.94  118.94  118.94  118.94
  118.94  118.94  118.94  118.94  118.94  118.94  118.94  118.94  118.93  118.93
  118.93  118.93  118.93  118.93  118.93  118.93  118.93  119.04  119.25  119.25
  119.29  119.25  119.25  119.22  119.04  119.07  119.09  119.18  119.19   119.2
  119.21  119.22  119.22  119.24  119.27  119.28   119.3   119.3  118.47   118.7
  118.87  119.32  118.82  115.62  116.82  116.42  117.52  116.02  116.02  117.52
  115.92  116.92  116.32  117.22  117.32  118.22  117.52  118.12  117.62  118.82
  117.02  118.12  116.92  115.62  115.22  117.32  117.32  118.12  116.72  115.62
  117.92  115.12  118.02  117.62  115.32  115.02  114.02  114.41  113.99  114.67
  114.71  114.67  112.75  113.16  113.53  114.45  115.12  115.92  117.62  115.72
  116.92  116.52  116.92  115.62  115.72  114.92  118.22  118.34  118.39  118.62
Pier Skew, UpSta & Num, DnSta & Num=  ,4941.7, 2 ,4941.7, 2 , 0 , 0 , 0 ,,
     1.4     1.4
  109.24  115.78
     1.4     1.4
  109.16   115.7
Pier Skew, UpSta & Num, DnSta & Num=  ,4969.9, 2 ,4969.9, 2 , 0 , 0 , 0 ,,
     1.4     1.4
  104.64   115.8
     1.4     1.4
  104.56  115.72
Pier Skew, UpSta & Num, DnSta & Num=  ,4998.6, 2 ,4998.6, 2 , 0 , 0 , 0 ,,
     1.4     1.4
   99.41  115.81
     1.4     1.4
   99.33  115.73
Pier Skew, UpSta & Num, DnSta & Num=  ,5025.8, 2 ,5025.8, 2 , 0 , 0 , 0 ,,
     1.4     1.4
  105.27  115.78
     1.4     1.4
  105.19   115.7
BR Coef= 1 , 1 , 0 ,1.25, 0 ,,,0.8,0,2,0,
WSPro=,,,, 1 ,,,, 0 ,,,, 0 ,,,,-1 ,-1 ,-1 , 0 , 0 , 0 , 0 , 0
BR U #Sta/Elev= 109
 -1278.9  118.95  -685.1   119.4  -575.1   118.9   214.9   115.7   384.9   116.9
  1337.6  116.59  1594.9   116.5  1754.9   117.6  1784.9   116.1  1804.9   116.1
  1834.9   117.6  2054.9     116  2164.9     117  2194.9   116.4  2234.9   117.3
  2304.9   117.4  2344.9   118.3  2404.9   117.6  2484.9   118.2  2524.9   117.7
  2574.9   118.1  2584.9   118.6  2614.9   118.9  2694.9   117.1  2704.9   117.2
  2734.9   118.2  2854.9     117  2884.9   115.7  2954.9   115.3  3094.9   117.4
  3124.9   117.4  3144.9   118.2  3214.6   118.1  3384.6   116.8  3424.6   115.7
  3434.6   115.8  3464.6   117.8  3474.6     118  3514.6   115.2  3684.6   118.1
  3724.6   117.7  3764.6   115.4  3804.6   115.1  3814.6   114.6  3834.6   114.1
  4666.9  114.27  4678.4   114.3  4722.4  114.29  4781.8  114.28  4784.5  114.28
    4795  114.22    4827  114.49  4827.3  114.49  4850.7  114.24  4902.7  114.22
  4913.4  114.08  4913.9  114.07 4914.01  114.07  4914.1  114.07  4914.2  114.07
  4914.8  114.06  4941.7  110.14  4947.6  111.47  4969.9  105.83    4981  102.78
  4981.8  102.16  4987.2  101.57  4998.6  100.33    5002  101.35  5016.4   101.1
    5019  103.05  5025.8  106.64  5033.8  109.19  5053.1  112.76  5053.3  112.79
 5053.39  112.81  5053.5  112.83  5053.6  112.85  5054.6  113.02  5055.9  113.24
  5151.4  113.73  5152.7  113.74  5209.7  113.61  5209.8  113.61  5264.5  114.53
  5265.3  114.53  5399.9   115.2  5811.8   115.9  5891.8   115.9  6081.8   116.3
  6091.8     116  6111.8   116.7  6151.8   117.2  6161.8   117.7  6181.8   117.5
  6231.8   115.8  6311.8     117  6391.8   116.6  6421.8     117  6531.8   115.7
  6651.8   115.8    6815   115.8    6905     115    6935   115.9    6995   118.3
  7010.8  118.38  7021.1  118.42  7030.6  118.47    7079   118.7
BR U #Mann= 6
 -1278.9      .2  1337.6     .14  4947.6    .035  5053.1     .14  7010.8      .1
  7030.6      .2
BR U Banks=4947.6,5053.1
BR D #Sta/Elev= 109
 -1278.9  118.87  -685.1  119.32  -575.1  118.82   214.9  115.62   384.9  116.82
  1337.6  116.51  1594.9  116.42  1754.9  117.52  1784.9  116.02  1804.9  116.02
  1834.9  117.52  2054.9  115.92  2164.9  116.92  2194.9  116.32  2234.9  117.22
  2304.9  117.32  2344.9  118.22  2404.9  117.52  2484.9  118.12  2524.9  117.62
  2574.9  118.02  2584.9  118.52  2614.9  118.82  2694.9  117.02  2704.9  117.12
  2734.9  118.12  2854.9  116.92  2884.9  115.62  2954.9  115.22  3094.9  117.32
  3124.9  117.32  3144.9  118.12  3214.6  118.02  3384.6  116.72  3424.6  115.62
  3434.6  115.72  3464.6  117.72  3474.6  117.92  3514.6  115.12  3684.6  118.02
  3724.6  117.62  3764.6  115.32  3804.6  115.02  3814.6  114.52  3834.6  114.02
  4666.9  114.19  4678.4  114.22  4722.4  114.21  4781.8   114.2  4784.5   114.2
    4795  114.14    4827  114.41  4827.3  114.41  4850.7  114.16  4902.7  114.14
  4913.4     114  4913.9  113.99 4914.01  113.99  4914.1  113.99  4914.2  113.99
  4914.8  113.98  4941.7  110.06  4947.6  111.39  4969.9  105.75    4981   102.7
  4981.8  102.08  4987.2  101.49  4998.6  100.25    5002  101.27  5016.4  101.02
    5019  102.97  5025.8  106.56  5033.8  109.11  5053.1  112.68  5053.3  112.71
 5053.39  112.73  5053.5  112.75  5053.6  112.77  5054.6  112.94  5055.9  113.16
  5151.4  113.65  5152.7  113.66  5209.7  113.53  5209.8  113.53  5264.5  114.45
  5265.3  114.45  5399.9  115.12  5811.8  115.82  5891.8  115.82  6081.8  116.22
  6091.8  115.92  6111.8  116.62  6151.8  117.12  6161.8  117.62  6181.8  117.42
  6231.8  115.72  6311.8  116.92  6391.8  116.52  6421.8  116.92  6531.8  115.62
  6651.8  115.72    6815  115.72    6905  114.92    6935  115.82    6995  118.22
  7010.8   118.3  7021.1  118.34  7030.6  118.39    7079  118.62
BR D #Mann= 6
 -1278.9      .2  1337.6     .14  4947.6    .035  5053.1     .14  7010.8      .1
  7030.6      .2
BR D Banks=4947.6,5053.1
BC Design=,, 0 ,, 0 ,,,,,,
BC HTab HWMax=119.41
BC Use User HTab Curves=0
BC User HTab FreeFlow(D)= 0

Type RM Length L Ch R = 1 ,209371.0,89.6,89.6,89.6
BEGIN DESCRIPTION:
Downstream Section of Bridge/Culvert/Weir
END DESCRIPTION:
XS GIS Cut Line= 6
      3064418.22     13915065.43       3066814.6     13910538.05
      3066852.22     13910472.54      3067637.15     13909006.43
      3067972.78     13908358.79      3068336.01     13907682.78
#Sta/Elev= 30
 -1278.9  118.88  -685.1  119.33   214.9  115.63  1337.6  116.52  1834.9  117.53
  2054.9  115.93  2614.9  118.83  2954.9  115.23  3144.9  118.13  3424.6  115.63
  3474.6  117.93  3514.6  115.13  3684.6  118.03  3834.6  114.03  4827.3  114.42
  4914.8  113.99  4941.7  110.07  4947.6   111.4  4981.8  102.09  4998.6  100.26
  5016.4  101.03  5033.8  109.12  5053.1  112.69  6161.8  117.63  6231.8  115.73
  6421.8  116.93    6905  114.93  7010.8  118.31  7030.6   118.4    7079  118.63
#Mann= 6 , 1 , 0
 -1278.9      .2       0  1337.6     .14       0  4947.6    .035       0
  5053.1     .14       0  7010.8      .1       0  7030.6      .2       0
#XS Ineff= 2 , 0
       0    4903   118.9    5063       0   118.8
Permanent Ineff=
       F       F
Bank Sta=4947.6,5053.1
XS Rating Curve= 0 ,0
Exp/Cntr=0.5,0.3

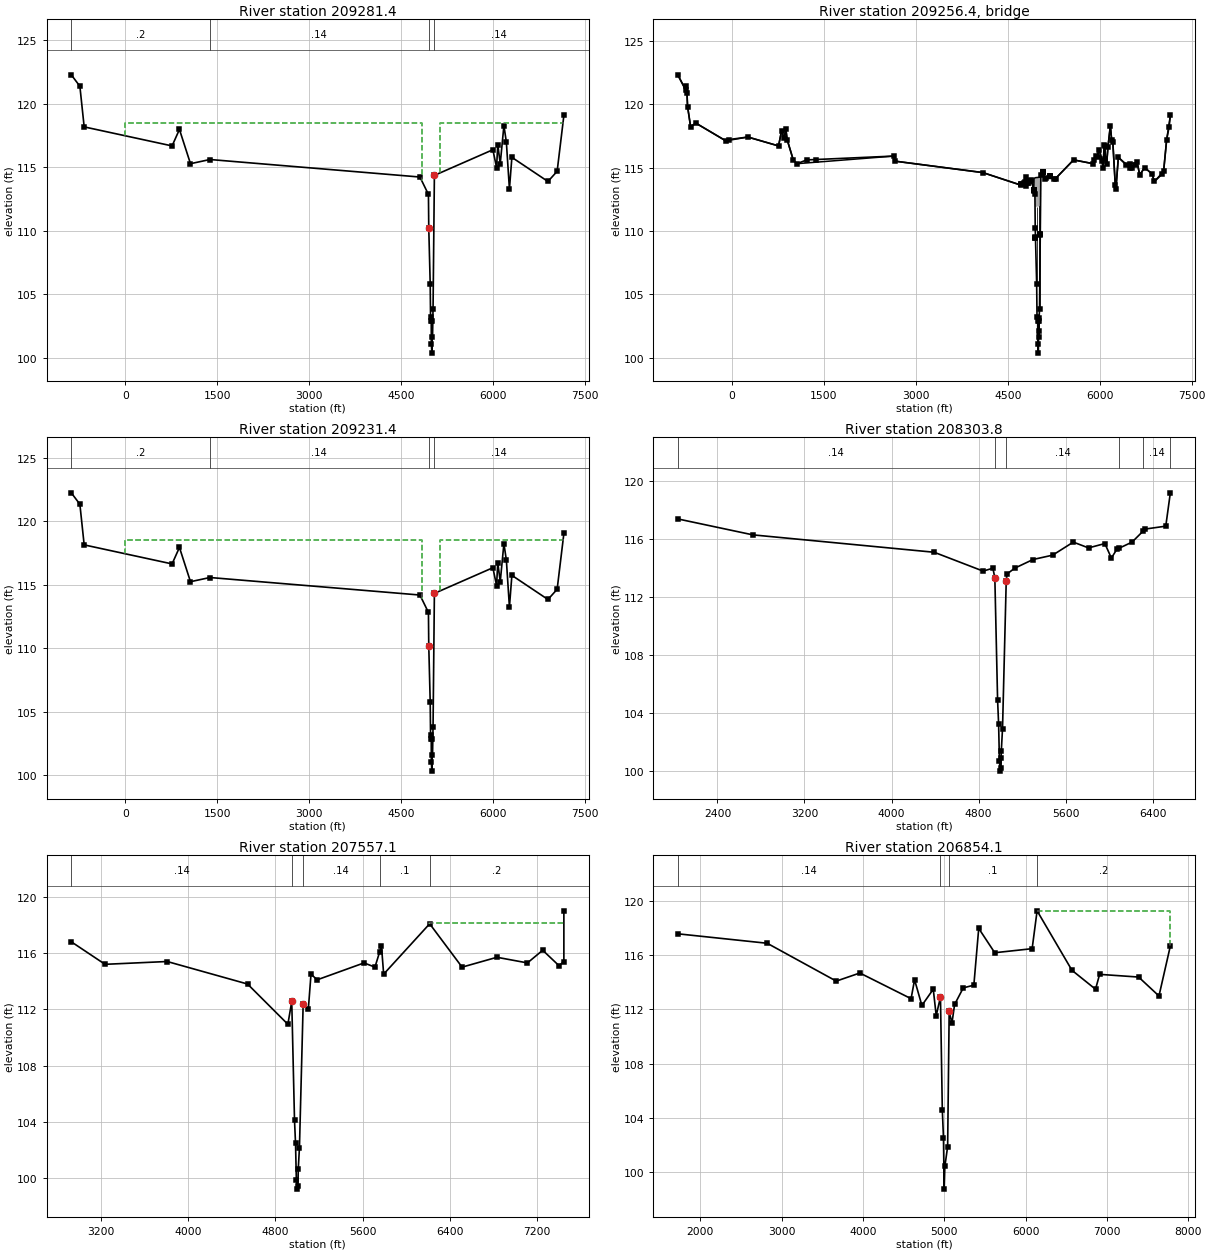
Type RM Length L Ch R = 1 ,209281.4,50,50,50
BEGIN DESCRIPTION:
Upstream Section of Bridge/Culvert/Weir
END DESCRIPTION:
XS GIS Cut Line= 6
      3064781.19     13914766.14      3064899.57     13914513.66
      3067394.23     13909647.74      3067459.89     13909513.79
      3067602.44     13909210.87      3068419.67     13907602.65
#Sta/Elev= 30
  -882.6  122.29  -742.6  121.39  -672.6  118.19   761.4  116.69   881.4  117.99
  1061.4  115.29  1379.2  115.62  4804.3  114.24  4943.1  112.87  4948.2  110.26
  4971.7  105.85  4977.5  103.21  4988.9  102.91  4990.3   101.1  4999.3  100.37
  5004.6  102.92  5006.8  101.61  5018.2  103.81  5040.1  114.37  5994.1  116.39
  6054.1  114.99  6074.1  116.79  6114.1  115.29  6174.1  118.29  6214.1  116.99
  6264.1  113.29  6304.1  115.79  6892.3  113.89  7042.3  114.69  7152.3  119.09
#Mann= 4 , 1 , 0
  -882.6      .2       0  1379.2     .14       0  4948.2    .035       0
  5040.1     .14       0
#XS Ineff= 2 , 0
       0    4837   118.5    5130       0   118.5
Permanent Ineff=
       F       F
Bank Sta=4948.2,5040.1
XS Rating Curve= 0 ,0
Exp/Cntr=0.5,0.3

Type RM Length L Ch R = 3 ,209256.4,,,
BEGIN DESCRIPTION:
H. L. & P. ACCESS BRIDGE
Structure ID: P00-81
END DESCRIPTION:
Bridge Culvert--1,0,-1,-1, 0
Deck Dist Width WeirC Skew NumUp NumDn MinLoCord MaxHiCord MaxSubmerge Is_Ogee
10,30,2.6,0, 60, 60, , , 0.95, 0, 1,1,,
  -882.6  -752.6  -742.6  -732.6  -722.6  -672.6  -588.6   -98.6   261.4   761.4
   811.4   851.4   881.4   901.4  1001.4  1061.4  2641.4  2661.4  4094.1  4722.2
  4804.3  4804.7  4881.1  4924.6  4928.9  4943.1  4948.2 4952.31  4952.4 5030.49
  5030.6  5040.1  5068.4  5111.2  5279.4  5574.1  5894.1  5994.1  6054.1  6074.1
  6084.1  6094.1  6114.1  6134.1  6174.1  6194.1  6214.1  6254.1  6264.1  6304.1
  6494.1  6502.3  6612.3  6652.3  6732.3  6852.3  6892.3  7042.3  7092.3  7152.3
   122.3   121.1   121.4   120.9   119.8   118.2   118.5   117.1   117.4   116.7
   117.9   117.3     118   117.2   115.6   115.3   115.9   115.5   114.6   113.6
  114.26  114.07   114.1  113.23  114.15  114.18  114.19   114.2   114.2  114.24
  114.24  114.39  114.66  114.14  114.13   115.6   115.3   116.4     115   116.8
   116.7   115.7   115.3   116.6   118.3   117.2     117   113.6   113.3   115.8
     115   115.3   115.4   114.4     115   114.5   113.9   114.7   117.2   119.1
   122.3   121.1   121.4   120.9   119.8   118.2   118.5   117.1   117.4   116.7
   117.9   117.3     118   117.2   115.6   115.3   115.9   115.5   114.6   113.6
  114.25  113.53  114.03  113.22  113.14  112.88  110.27   109.5   111.9  111.94
   109.8  114.38  114.65  114.08  114.13   115.6   115.3   116.4     115   116.8
   116.7   115.7   115.3   116.6   118.3   117.2     117   113.6   113.3   115.8
     115   115.3   115.4   114.4     115   114.5   113.9   114.7   117.2   119.1
  -882.6  -752.6  -742.6  -732.6  -722.6  -672.6  -588.6   -98.6   261.4   761.4
   811.4   851.4   881.4   901.4  1001.4  1061.4  2641.4  2661.4  4094.1  4722.2
  4804.3  4804.7  4881.1  4924.6  4928.9  4943.1  4948.2 4952.31  4952.4 5030.49
  5030.6  5040.1  5068.4  5111.2  5279.4  5574.1  5894.1  5994.1  6054.1  6074.1
  6084.1  6094.1  6114.1  6134.1  6174.1  6194.1  6214.1  6254.1  6264.1  6304.1
  6494.1  6502.3  6612.3  6652.3  6732.3  6852.3  6892.3  7042.3  7092.3  7152.3
   122.3   121.1   121.4   120.9   119.8   118.2   118.5   117.1   117.4   116.7
   117.9   117.3     118   117.2   115.6   115.3   115.9   115.5   114.6   113.6
  114.26  114.07   114.1  113.23  114.15  114.18  114.19   114.2   114.2  114.24
  114.24  114.39  114.66  114.14  114.13   115.6   115.3   116.4     115   116.8
   116.7   115.7   115.3   116.6   118.3   117.2     117   113.6   113.3   115.8
     115   115.3   115.4   114.4     115   114.5   113.9   114.7   117.2   119.1
  122.25  121.05  121.35  120.85  119.75  118.15  118.45  117.05  117.35  116.65
  117.85  117.25  117.95  117.15  115.55  115.25  115.85  115.45  114.55  113.55
   114.2  113.48  113.98  113.17  113.09  112.83  110.22  109.45  111.85  111.89
  109.75  114.33   114.6  114.03  114.08  115.55  115.25  116.35  114.95  116.75
  116.65  115.65  115.25  116.55  118.25  117.15  116.95  113.55  113.25  115.75
  114.95  115.25  115.35  114.35  114.95  114.45  113.85  114.65  117.15  119.05
Pier Skew, UpSta & Num, DnSta & Num=  ,4971.7, 2 ,4971.7, 2 , 0 , 0 , 0 ,,
     1.4     1.4
  104.54  112.93
     1.4     1.4
  104.49  112.88
Pier Skew, UpSta & Num, DnSta & Num=  ,5018.2, 2 ,5018.2, 2 , 0 , 0 , 0 ,,
     1.4     1.4
  102.75  112.97
     1.4     1.4
   102.7  112.92
BR Coef= 1 , 1 , 0 ,1.25, 0 ,,,0.8,0,2,0,
WSPro=,,,, 1 ,,,, 0 ,,,, 0 ,,,,-1 ,-1 ,-1 , 0 , 0 , 0 , 0 , 0
BR U #Sta/Elev= 102
  -882.6   122.3  -752.6   121.1  -742.6   121.4  -732.6   120.9  -722.6   119.8
  -672.6   118.2  -588.6   118.5   -98.6   117.1   -48.6   117.2   261.4   117.4
   761.4   116.7   811.4   117.9   851.4   117.3   881.4     118   901.4   117.2
  1001.4   115.6  1061.4   115.3  1221.4   115.6  1379.2  115.63  2641.4   115.9
  2661.4   115.5  4094.1   114.6  4722.2   113.6  4723.5  113.67  4723.6  113.68
  4771.6  113.81  4774.7  113.85  4804.3  114.25  4804.7  113.53  4824.6  113.78
  4826.4  113.79  4881.1  114.03  4884.3  113.97  4924.4  113.23 4924.49  113.23
  4924.6  113.22 4924.71  113.22  4928.9  113.14  4943.1  112.88  4948.2  110.27
 4952.31   109.5  4952.4  109.48  4952.5  109.46  4971.7  105.86  4977.5  103.22
  4988.9  102.92  4990.3  101.11  4999.3  100.38  5004.6  102.93    5006   102.1
  5006.8  101.62  5011.1  103.15  5018.2  103.82  5030.4   109.7 5030.49  109.75
  5030.6   109.8  5040.1  114.38  5068.4  114.65 5070.09  114.63  5070.2  114.63
 5070.31  114.62  5111.2  114.08  5130.8  114.15  5187.9  114.34  5188.2  114.34
  5191.6  114.35    5248  114.13  5279.4  114.13  5574.1   115.6  5894.1   115.3
  5914.1   115.6  5934.1   115.9  5964.1   115.8  5994.1   116.4  6044.1   115.5
  6054.1     115  6074.1   116.8  6084.1   116.7  6094.1   115.7  6114.1   115.3
  6134.1   116.6  6174.1   118.3  6194.1   117.2  6214.1     117  6254.1   113.6
  6264.1   113.3  6304.1   115.8  6434.1   115.2  6494.1     115  6502.3   115.3
  6532.3     115  6582.3   115.2  6612.3   115.4  6652.3   114.4  6732.3     115
  6852.3   114.5  6892.3   113.9  7022.3   114.5  7042.3   114.7  7092.3   117.2
  7132.3   118.2  7152.3   119.1
BR U #Mann= 4
  -882.6      .2  1379.2     .14  4948.2    .035  5040.1     .14
BR U Banks=4948.2,5040.1
BR D #Sta/Elev= 102
  -882.6  122.25  -752.6  121.05  -742.6  121.35  -732.6  120.85  -722.6  119.75
  -672.6  118.15  -588.6  118.45   -98.6  117.05   -48.6  117.15   261.4  117.35
   761.4  116.65   811.4  117.85   851.4  117.25   881.4  117.95   901.4  117.15
  1001.4  115.55  1061.4  115.25  1221.4  115.55  1379.2  115.58  2641.4  115.85
  2661.4  115.45  4094.1  114.55  4722.2  113.55  4723.5  113.62  4723.6  113.63
  4771.6  113.76  4774.7   113.8  4804.3   114.2  4804.7  113.48  4824.6  113.73
  4826.4  113.74  4881.1  113.98  4884.3  113.92  4924.4  113.18 4924.49  113.18
  4924.6  113.17 4924.71  113.17  4928.9  113.09  4943.1  112.83  4948.2  110.22
 4952.31  109.45  4952.4  109.43  4952.5  109.41  4971.7  105.81  4977.5  103.17
  4988.9  102.87  4990.3  101.06  4999.3  100.33  5004.6  102.88    5006  102.05
  5006.8  101.57  5011.1   103.1  5018.2  103.77  5030.4  109.65 5030.49   109.7
  5030.6  109.75  5040.1  114.33  5068.4   114.6 5070.09  114.58  5070.2  114.58
 5070.31  114.57  5111.2  114.03  5130.8   114.1  5187.9  114.29  5188.2  114.29
  5191.6   114.3    5248  114.08  5279.4  114.08  5574.1  115.55  5894.1  115.25
  5914.1  115.55  5934.1  115.85  5964.1  115.75  5994.1  116.35  6044.1  115.45
  6054.1  114.95  6074.1  116.75  6084.1  116.65  6094.1  115.65  6114.1  115.25
  6134.1  116.55  6174.1  118.25  6194.1  117.15  6214.1  116.95  6254.1  113.55
  6264.1  113.25  6304.1  115.75  6434.1  115.15  6494.1  114.95  6502.3  115.25
  6532.3  114.95  6582.3  115.15  6612.3  115.35  6652.3  114.35  6732.3  114.95
  6852.3  114.45  6892.3  113.85  7022.3  114.45  7042.3  114.65  7092.3  117.15
  7132.3  118.15  7152.3  119.05
BR D #Mann= 4
  -882.6      .2  1379.2     .14  4948.2    .035  5040.1     .14
BR D Banks=4948.2,5040.1
BC Design=,, 0 ,, 0 ,,,,,,
BC HTab HWMax=122.29
BC Use User HTab Curves=0
BC User HTab FreeFlow(D)= 0

Type RM Length L Ch R = 1 ,209231.4,927.6,927.6,927.6
BEGIN DESCRIPTION:
Downstream Section of Bridge/Culvert/Weir
END DESCRIPTION:
XS GIS Cut Line= 6
      3064831.06     13914769.67      3064949.45      13914517.2
      3067444.11     13909651.28      3067509.77     13909517.33
      3067652.32     13909214.41      3068469.55     13907606.19
#Sta/Elev= 30
  -882.6  122.25  -742.6  121.35  -672.6  118.15   761.4  116.65   881.4  117.95
  1061.4  115.25  1379.2  115.58  4804.3   114.2  4943.1  112.83  4948.2  110.22
  4971.7  105.81  4977.5  103.17  4988.9  102.87  4990.3  101.06  4999.3  100.33
  5004.6  102.88  5006.8  101.57  5018.2  103.77  5040.1  114.33  5994.1  116.35
  6054.1  114.95  6074.1  116.75  6114.1  115.25  6174.1  118.25  6214.1  116.95
  6264.1  113.25  6304.1  115.75  6892.3  113.85  7042.3  114.65  7152.3  119.05
#Mann= 4 , 1 , 0
  -882.6      .2       0  1379.2     .14       0  4948.2    .035       0
  5040.1     .14       0
#XS Ineff= 2 , 0
       0    4837   118.5    5130       0   118.5
Permanent Ineff=
       F       F
Bank Sta=4948.2,5040.1
XS Rating Curve= 0 ,0
Exp/Cntr=0.5,0.3

Type RM Length L Ch R = 1 ,208303.8,712.7,746.7,824.6
BEGIN DESCRIPTION:
Cross Section 208303.8-Interpolated
END DESCRIPTION:
XS GIS Cut Line= 4
      3067404.01     13912073.75      3068299.61     13910244.03
      3068417.25     13909020.56       3068579.8     13907768.93
#Sta/Elev= 30
    2035   117.4    2725   116.3  4392.2   115.1  4842.2   113.8  4932.2     114
    4950  113.33  4975.3  104.89  4984.6  103.26  4992.2  100.67  5000.9     100
  5007.2  100.24  5007.8  100.94  5009.7  101.42  5020.6  102.94  5054.7  113.13
  5062.2   113.6  5132.2     114  5301.3   114.6  5481.3   114.9  5671.3   115.8
  5811.3   115.4  5961.3   115.7  6021.3   114.7  6071.3   115.3  6087.3  115.36
  6211.3   115.8  6311.8  116.55  6331.3   116.7  6521.3   116.9  6563.4   119.2
#Mann= 6 , 1 , 0
    2035     .14       0    4950    .035       0  5054.7     .14       0
  6087.3      .1       0  6311.8     .14       0  6563.4      .2       0
#XS Ineff= 2 , 0
       0                  5671.3       0   115.8
Permanent Ineff=
       F       F
Bank Sta=4950,5054.7
XS Rating Curve= 0 ,0
Exp/Cntr=0.3,0.1

Type RM Length L Ch R = 1 ,207557.1,659.7,703,708.2
BEGIN DESCRIPTION:
Cross Section 207557.1
END DESCRIPTION:
XS GIS Cut Line= 6
      3068614.63     13911085.03       3069040.1     13909903.19
      3069082.64     13909543.92       3069092.1     13909151.56
       3069092.1     13908924.65      3069145.51     13906640.98
#Sta/Elev= 30
  2926.3   116.8  3236.3   115.2  3806.3   115.4  4544.2   113.8  4914.4  110.94
    4950  112.56  4975.3  104.12  4984.6  102.49  4992.2    99.9  5000.9   99.23
  5007.2   99.47  5009.7  100.65  5020.6  102.17  5054.7  112.36  5102.2  112.02
  5126.7   114.5  5183.6   114.1  5613.6   115.3  5713.6     115  5755.7  116.05
  5773.6   116.5  5793.6   114.5    6216  118.08  6513.6     115  6833.6   115.7
  7113.6   115.3  7253.6   116.2  7403.6   115.1  7447.9   115.4    7448     119
#Mann= 5 , 1 , 0
  2926.3     .14       0    4950    .035       0  5054.7     .14       0
  5755.7      .1       0    6216      .2       0
#XS Ineff= 2 , 0
       0                  6213.6       0   118.1
Permanent Ineff=
       F       F
Bank Sta=4950,5054.7
XS Rating Curve= 0 ,0
Exp/Cntr=0.3,0.1

Type RM Length L Ch R = 1 ,206854.1,371.9,680.1,1180.7
BEGIN DESCRIPTION:
Cross Section 206854.1
END DESCRIPTION:
XS GIS Cut Line= 6
      3068427.88     13912085.32      3069096.82     13910654.83
      3069777.55     13909543.92      3069791.73     13909260.29
      3069782.27     13907898.84      3069705.73     13906370.79
#Sta/Elev= 30
  1722.9   117.6  2822.9   116.9  3672.1   114.1  3962.1   114.7  4592.1   112.8
    4635   114.2    4725   112.3    4865   113.5  4901.2  111.55  4953.5  112.92
  4976.1   104.6  4990.5  102.51  4999.2   98.71  5007.4  100.39  5041.8  101.86
  5060.7  111.87  5094.4  110.98  5127.3  112.37    5234   113.6    5364   113.8
    5424     118  5620.9   116.2  6080.9   116.5  6141.9   119.3  6570.5   114.9
  6860.5   113.5  6910.5   114.6  7390.5   114.4  7640.5     113  7780.5   116.7
#Mann= 4 , 1 , 0
  1722.9     .14       0  4953.5    .035       0  5060.7      .1       0
  6141.9      .2       0
#XS Ineff= 2 , 0
       0  3962.1   114.7  6141.9       0   119.3
Permanent Ineff=
       F       F
Bank Sta=4953.5,5060.7
XS Rating Curve= 0 ,0
Exp/Cntr=0.5,0.3