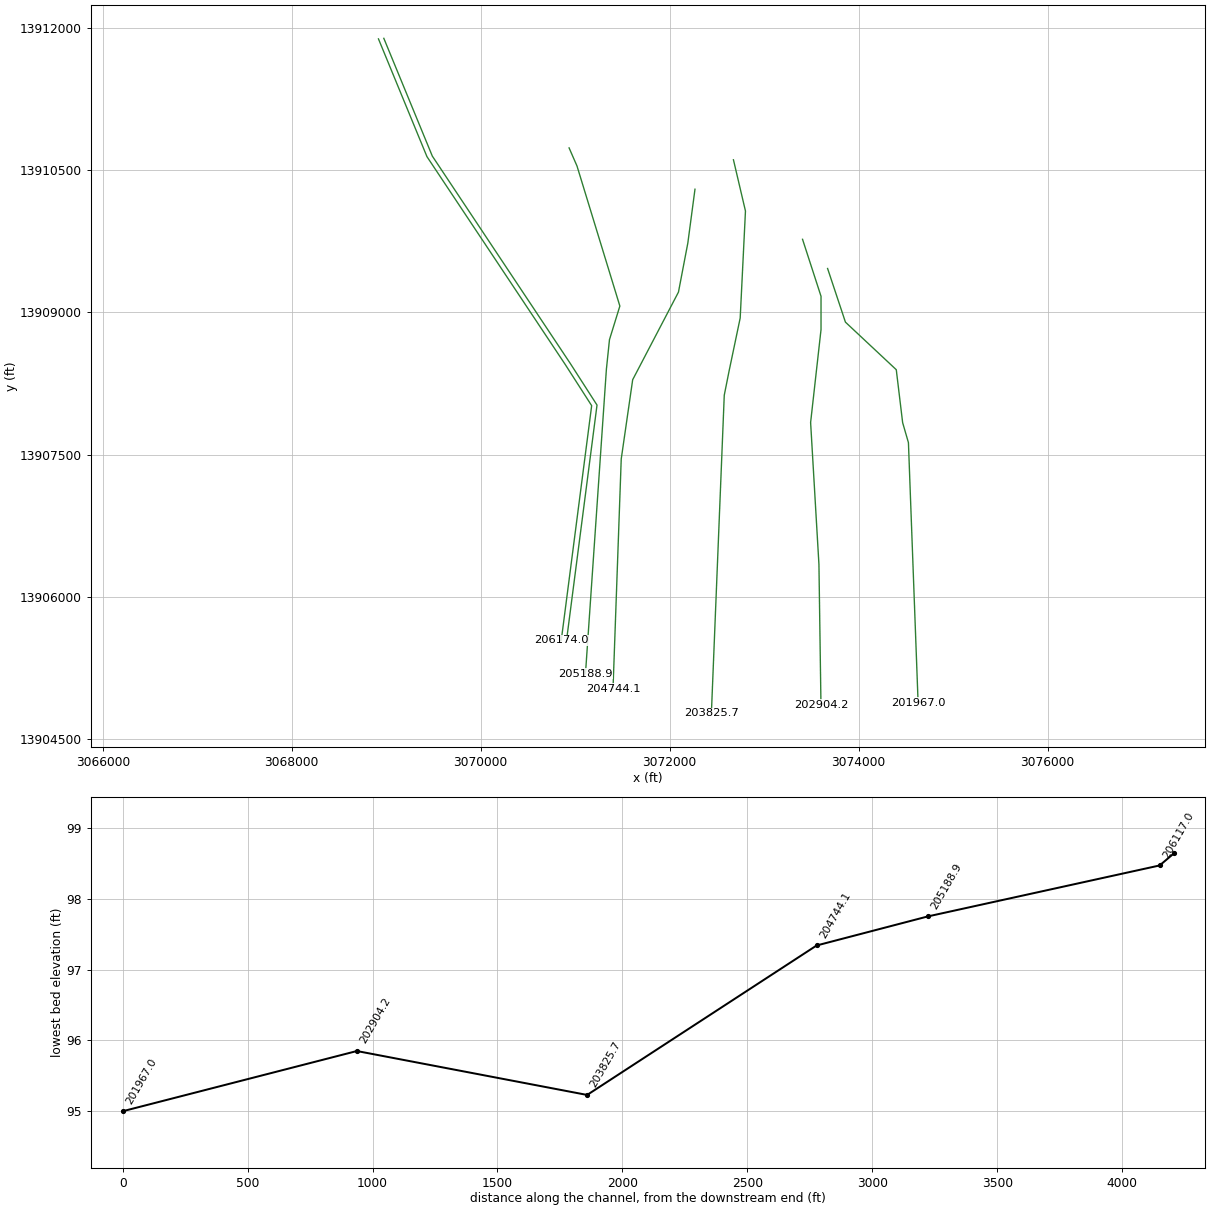
HEC-RAS study P100-00-00.prj: P100-00-00

--- P100-00-00.g01 (geometry) --- (continued)

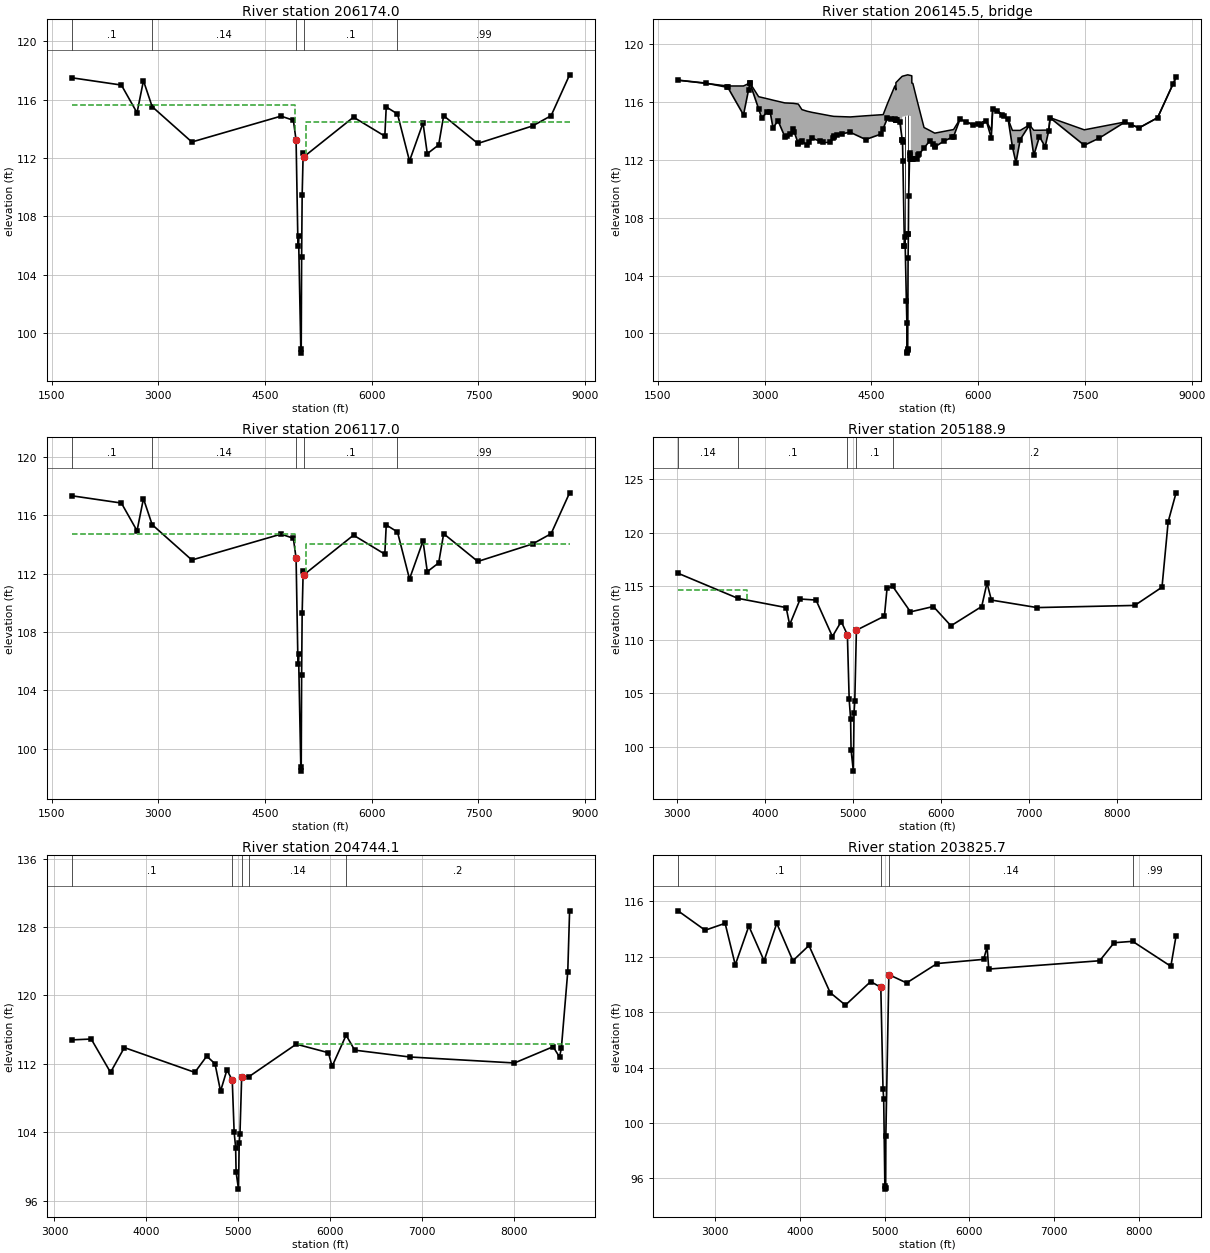
Type RM Length L Ch R = 1 ,206174.0,57,57,57
BEGIN DESCRIPTION:
Upstream Section of Bridge/Culvert/Weir
END DESCRIPTION:
XS GIS Cut Line= 5
       3068918.4     13911888.17      3069431.69     13910645.03
      3070896.61     13908448.67      3071174.98     13908016.19
      3070853.02     13905537.35
#Sta/Elev= 30
  1781.5   117.5  2481.5     117  2701.5   115.1  2791.5   117.3    2914  115.52
  3471.7   113.1  4724.4  114.87 4898.48  114.59 4936.61  113.22 4962.94  106.01
  4971.3  106.67  5004.1   98.64 5008.86   98.92 5014.43   105.2 5022.06  109.48
 5036.16  112.32 5043.79  112.08  5743.6   114.8  6183.6   113.5  6203.6   115.5
  6361.5  115.02  6530.5   111.8  6720.5   114.4  6780.5   112.3  6940.5   112.9
  7010.5   114.9  7490.5     113  8260.5   114.2  8520.5   114.9  8780.5   117.7
#Mann= 5 , 1 , 0
  1781.5      .1       0    2914     .14       0 4936.61    .035       0
 5043.79      .1       0  6361.5     .99       0
#XS Ineff= 2 , 0
       0    4920   115.6    5076       0   114.5
Permanent Ineff=
       F       F
Bank Sta=4936.61,5043.79
XS Rating Curve= 0 ,0
Exp/Cntr=0.5,0.3

Type RM Length L Ch R = 3 ,206145.5,,,
BEGIN DESCRIPTION:
CUTTEN ROAD - 35 degree skew
Structure ID: P00-80
END DESCRIPTION:
Bridge Culvert--1,0,-1,-1, 0
Deck Dist Width WeirC Skew NumUp NumDn MinLoCord MaxHiCord MaxSubmerge Is_Ogee
10,37,2.6,0, 60, 60, , , 0.95, 0, 1,1,,
  1781.5  2481.5  2701.5  2791.5    2914  2956.3  3076.3  3116.3  3186.3  3281.7
  3401.7  3471.7  3521.7  3591.7  3661.7  3920.8  3970.8  4200.8  4418.9    4631
  4664.4  4724.4  4828.6 4843.19  4843.3 4861.58 4898.48 4931.77 4931.86 5008.86
 5053.85 5053.96  5066.9 5067.01  5081.5 5134.32  5238.4 5320.87  5389.3  5653.6
  5743.6  5933.6  6113.6  6183.6  6203.6  6420.5  6480.5  6530.5  6590.5  6720.5
  6780.5  6860.5  6940.5  6990.5  7010.5  7490.5  8060.5  8260.5  8520.5  8780.5
   117.5   117.1   117.1  117.31  116.36  116.31  116.17  116.12  116.04  115.93
   115.9  115.85  115.47  115.36  115.28  115.04     115  114.96  115.04  115.11
  115.12  115.88   117.1  116.83  117.33  117.42  117.61  117.77  117.77  117.87
  117.82  117.82   117.8   117.3  117.28  116.23  114.23  114.02  113.84  114.09
  114.81  114.41  114.71  114.02  115.51  114.81  114.03  114.03  114.03  114.41
  114.04  114.04  114.05  114.05  114.91  114.07  114.61  114.21  114.91   117.7
   117.5     117   115.1   117.3  115.52   114.9   115.3   114.2   114.7   113.6
   114.1   113.1   113.3     113   113.5   113.2   113.6   113.9   113.4  113.77
  114.16  114.87  114.79  114.77  114.77  114.76  114.59  113.39  114.97  115.07
  115.02  112.08  112.08  112.08  112.08  112.08  112.81  113.32  112.92   113.6
   114.8   114.4   114.7   113.5   115.5   114.8   112.9   111.8   113.4   114.4
   112.3   113.6   112.9     114   114.9     113   114.6   114.2   114.9   117.7
  1781.5  2481.5  2701.5  2791.5    2914  2956.3  3076.3  3116.3  3186.3  3281.7
  3401.7  3471.7  3521.7  3591.7  3661.7  3920.8  3970.8  4200.8  4418.9    4631
  4664.4  4724.4  4828.6 4843.19  4843.3 4861.58 4898.48 4931.77 4931.86 5008.86
 5053.85 5053.96  5066.9 5067.01  5081.5 5134.32  5238.4 5320.87  5389.3  5653.6
  5743.6  5933.6  6113.6  6183.6  6203.6  6420.5  6480.5  6530.5  6590.5  6720.5
  6780.5  6860.5  6940.5  6990.5  7010.5  7490.5  8060.5  8260.5  8520.5  8780.5
   117.5   117.1   117.1  117.31  116.36  116.31  116.17  116.12  116.04  115.93
   115.9  115.85  115.47  115.36  115.28  115.04     115  114.96  115.04  115.11
  115.12  115.88   117.1  116.83  117.33  117.42  117.61  117.77  117.77  117.87
  117.82  117.82   117.8   117.3  117.28  116.23  114.23  114.02  113.84  114.09
  114.81  114.41  114.71  114.02  115.51  114.81  114.03  114.03  114.03  114.41
  114.04  114.04  114.05  114.05  114.91  114.07  114.61  114.21  114.91   117.7
  117.34  116.84  114.94  117.14  115.36  114.74  115.14  114.04  114.54  113.44
  113.94  112.94  113.14  112.84  113.34  113.04  113.44  113.74  113.24  113.61
     114  114.71  114.63  114.61  114.61   114.6  114.43  113.23  114.81  114.91
  114.86  111.92  111.92  111.92  111.92  111.92  112.65  113.16  112.76  113.44
  114.64  114.24  114.54  113.34  115.34  114.64  112.74  111.64  113.24  114.24
  112.14  113.44  112.74  113.84  114.74  112.84  114.44  114.04  114.74  117.54
Pier Skew, UpSta & Num, DnSta & Num=  ,4971.3, 2 ,4971.3, 2 , 0 , 0 , 0 ,,
     1.4     1.4
  105.51  116.04
     1.4     1.4
  105.35  115.88
Pier Skew, UpSta & Num, DnSta & Num=  ,5014.4, 2 ,5014.4, 2 , 0 , 0 , 0 ,,
     1.4     1.4
  103.41  116.06
     1.4     1.4
  103.25   115.9
Abutment Skew #Up #Dn= , 2 , 2
 4931.66 4962.94
  114.97  106.01
 4931.66 4962.94
  114.81  105.85
Abutment Skew #Up #Dn= , 2 , 2
 5018.53 5054.05
  106.88  115.02
 5018.53 5054.05
  106.72  114.86
BR Coef= 1 , 1 , 0 ,1.25, 0 ,,,0.8,-1,2,0,
WSPro=,,,, 1 ,,,, 0 ,,,, 0 ,,,,-1 ,-1 ,-1 , 0 , 0 , 0 , 0 , 0
BR U #Sta/Elev= 112
  1781.5   117.5  2171.5   117.3    2472  117.01  2481.5     117  2701.5   115.1
    2772  116.82  2791.5   117.3    2792  117.29    2914  115.52  2956.3   114.9
  3036.3   115.3  3076.3   115.3  3116.3   114.2  3186.3   114.7  3281.7   113.6
  3306.4  113.67  3351.7   113.8  3401.7   114.1  3416.4  113.89  3466.4  113.18
  3471.7   113.1  3506.4  113.24  3521.7   113.3  3591.7     113  3626.4  113.25
  3661.7   113.5  3776.4  113.28  3820.8   113.2  3920.8   113.2  3956.4  113.48
  3970.8   113.6  3976.4  113.61  4016.4  113.68  4080.8   113.8  4200.8   113.9
  4418.9   113.4    4631  113.77  4664.4  114.16  4724.4  114.87  4769.3  114.83
  4828.6  114.79 4843.19  114.77  4843.3  114.77 4843.41  114.77 4861.58  114.76
 4898.48  114.59 4931.77  113.39 4931.86  113.39 4936.61  113.22  4941.4  111.91
 4962.84  106.04 4962.94  106.01  4971.3  106.67 4990.41  102.22 4997.62   100.7
 4999.84   98.71  5004.1   98.64  5007.6   98.85 5008.86   98.92 5014.43   105.2
 5018.43  106.84 5018.53  106.88 5022.06  109.48 5036.16  112.32 5041.49  112.46
 5043.79  112.08 5053.85  112.08 5053.96  112.08 5066.79  112.08  5066.9  112.08
 5067.01  112.08  5081.5  112.08 5134.32  112.08 5156.54  112.31  5168.7  112.38
  5238.4  112.81 5320.87  113.32  5362.5   113.1  5389.3  112.92  5392.5   112.9
  5522.5   113.3  5636.4  113.56  5653.6   113.6  5743.6   114.8  5826.5  114.63
  5933.6   114.4  5993.6   114.5  6043.6   114.4  6113.6   114.7  6183.6   113.5
  6203.6   115.5  6270.5   115.4  6340.5   115.1  6361.5  115.02  6420.5   114.8
  6480.5   112.9  6530.5   111.8  6590.5   113.4  6720.5   114.4  6780.5   112.3
  6860.5   113.6  6940.5   112.9  6990.5     114  7010.5   114.9  7490.5     113
  7700.5   113.5  8060.5   114.6  8150.8  114.42  8260.5   114.2  8520.5   114.9
  8740.8  117.27  8780.5   117.7
BR U #Mann= 5
  1781.5      .1    2914     .14 4936.61    .035 5043.79      .1  6361.5     .99
BR U Banks=4936.61,5043.79
BR D #Sta/Elev= 112
  1781.5  117.34  2171.5  117.14    2472  116.85  2481.5  116.84  2701.5  114.94
    2772  116.66  2791.5  117.14    2792  117.13    2914  115.36  2956.3  114.74
  3036.3  115.14  3076.3  115.14  3116.3  114.04  3186.3  114.54  3281.7  113.44
  3306.4  113.51  3351.7  113.64  3401.7  113.94  3416.4  113.73  3466.4  113.02
  3471.7  112.94  3506.4  113.08  3521.7  113.14  3591.7  112.84  3626.4  113.09
  3661.7  113.34  3776.4  113.12  3820.8  113.04  3920.8  113.04  3956.4  113.32
  3970.8  113.44  3976.4  113.45  4016.4  113.52  4080.8  113.64  4200.8  113.74
  4418.9  113.24    4631  113.61  4664.4     114  4724.4  114.71  4769.3  114.67
  4828.6  114.63 4843.19  114.61  4843.3  114.61 4843.41  114.61 4861.58   114.6
 4898.48  114.43 4931.77  113.23 4931.86  113.23 4936.61  113.06  4941.4  111.75
 4962.84  105.88 4962.94  105.85  4971.3  106.51 4990.41  102.06 4997.62  100.54
 4999.84   98.55  5004.1   98.48  5007.6   98.69 5008.86   98.76 5014.43  105.04
 5018.43  106.68 5018.53  106.72 5022.06  109.32 5036.16  112.16 5041.49   112.3
 5043.79  111.92 5053.85  111.92 5053.96  111.92 5066.79  111.92  5066.9  111.92
 5067.01  111.92  5081.5  111.92 5134.32  111.92 5156.54  112.15  5168.7  112.22
  5238.4  112.65 5320.87  113.16  5362.5  112.94  5389.3  112.76  5392.5  112.74
  5522.5  113.14  5636.4   113.4  5653.6  113.44  5743.6  114.64  5826.5  114.47
  5933.6  114.24  5993.6  114.34  6043.6  114.24  6113.6  114.54  6183.6  113.34
  6203.6  115.34  6270.5  115.24  6340.5  114.94  6361.5  114.86  6420.5  114.64
  6480.5  112.74  6530.5  111.64  6590.5  113.24  6720.5  114.24  6780.5  112.14
  6860.5  113.44  6940.5  112.74  6990.5  113.84  7010.5  114.74  7490.5  112.84
  7700.5  113.34  8060.5  114.44  8150.8  114.26  8260.5  114.04  8520.5  114.74
  8740.8  117.11  8780.5  117.54
BR D #Mann= 5
  1781.5      .1    2914     .14 4936.61    .035 5043.79      .1  6361.5     .99
BR D Banks=4936.61,5043.79
BC Design=,, 0 ,, 0 ,,,,,,
BC HTab HWMax=117.7
BC Use User HTab Curves=0
BC User HTab FreeFlow(D)= 0

Type RM Length L Ch R = 1 ,206117.0,928.1,928.1,928.1
BEGIN DESCRIPTION:
Downstream Section of Bridge/Culvert/Weir
END DESCRIPTION:
XS GIS Cut Line= 5
      3068975.09     13911894.16      3069488.37     13910651.01
      3070953.29     13908454.65      3071231.66     13908022.17
      3070909.71     13905543.33
#Sta/Elev= 30
  1781.5  117.33  2481.5  116.83  2701.5  114.93  2791.5  117.13    2914  115.35
  3471.7  112.93  4724.4   114.7 4898.48  114.42 4936.61  113.05 4962.94  105.84
  4971.3   106.5  5004.1   98.47 5008.86   98.75 5014.43  105.03 5022.06  109.31
 5036.16  112.15 5043.79  111.91  5743.6  114.63  6183.6  113.33  6203.6  115.33
  6361.5  114.85  6530.5  111.63  6720.5  114.23  6780.5  112.13  6940.5  112.73
  7010.5  114.73  7490.5  112.83  8260.5  114.03  8520.5  114.73  8780.5  117.53
#Mann= 5 , 1 , 0
  1781.5      .1       0    2914     .14       0 4936.61    .035       0
 5043.79      .1       0  6361.5     .99       0
#XS Ineff= 2 , 0
       0    4920   114.7    5076       0     114
Permanent Ineff=
       F       F
Bank Sta=4936.61,5043.79
XS Rating Curve= 0 ,0
Exp/Cntr=0.5,0.3

Type RM Length L Ch R = 1 ,205188.9,680.6,444.8,340.5
BEGIN DESCRIPTION:
Cross Section 205188.9-Interpolated
END DESCRIPTION:
XS GIS Cut Line= 6
      3070936.08     13910737.51      3071019.93     13910545.69
      3071473.42     13909067.65      3071363.57     13908712.94
      3071330.78     13908398.32      3071109.47     13905185.98
#Sta/Elev= 30
    3010   116.2  3691.2  113.86  4239.3     113  4279.3   111.4  4399.3   113.8
  4579.3   113.7  4765.3   110.3  4865.3   111.7  4935.6  110.47    4956  104.44
  4972.4  102.62  4977.4   99.74  5003.5   97.75  5011.1  103.15  5019.6  104.25
  5038.1  110.89  5356.7   112.2  5386.7   114.8    5450  114.99    5653   112.6
    5913   113.1    6113   111.3    6463   113.1    6523   115.3    6573   113.7
    7093     113    8203   113.2    8513   114.9    8583     121    8673   123.7
#Mann= 5 , 1 , 0
    3010     .14       0  3691.2      .1       0  4935.6    .035       0
  5038.1      .1       0    5450      .2       0
#XS Ineff= 2 , 0
       0  3789.3   114.6    6523       0   115.3
Permanent Ineff=
       F       F
Bank Sta=4935.6,5038.1
XS Rating Curve= 0 ,0
Exp/Cntr=0.3,0.1

Type RM Length L Ch R = 1 ,204744.1,735.5,918.4,1216.1
BEGIN DESCRIPTION:
Cross Section 204744.1
END DESCRIPTION:
XS GIS Cut Line= 6
      3072268.62     13910301.32      3072192.85     13909732.64
      3072093.72     13909214.97       3071609.1     13908289.78
      3071487.94      13907452.7      3071400.88     13905024.25
#Sta/Elev= 30
  3186.2   114.8  3400.2   114.9  3610.2     111  3760.9   113.9    4528     111
    4658   112.9    4748     112    4808   108.8    4878   111.3  4935.6  110.06
    4956  104.03  4972.4  102.21  4977.4   99.33  5003.5   97.34  5011.1  102.74
  5019.6  103.84  5038.1  110.48  5119.1  110.51  5632.5   114.3  5982.5   113.3
  6022.5   111.7  6175.2  115.35  6268.3   113.6  6868.3   112.8  8008.3   112.1
  8428.3     114  8498.3   112.8  8518.3   113.8  8588.3   122.8  8608.3   129.9
#Mann= 5 , 1 , 0
  3186.2      .1       0  4935.6    .035       0  5038.1      .1       0
  5119.1     .14       0  6175.2      .2       0
#XS Ineff= 2 , 0
       0  3760.9   113.9  5662.5       0   114.3
Permanent Ineff=
       F       F
Bank Sta=4935.6,5038.1
XS Rating Curve= 0 ,0
Exp/Cntr=0.3,0.1

Type RM Length L Ch R = 1 ,203825.7,873,921.5,1022.5
BEGIN DESCRIPTION:
Cross Section 203825.7
Structure ID: PL1_P00-79_DSPL
END DESCRIPTION:
XS GIS Cut Line= 6
      3072675.76     13910611.88      3072802.93     13910070.73
      3072747.13     13908941.41      3072630.32     13908385.39
       3072578.5     13908126.31      3072442.26     13904767.31
#Sta/Elev= 30
  2558.9   115.3  2878.9   113.9  3114.8   114.4  3234.8   111.4  3394.8   114.2
  3574.8   111.7  3724.8   114.4  3914.8   111.7  4104.8   112.8  4355.5   109.4
  4535.5   108.5  4833.7   110.2 4953.29  109.78 4979.19  102.47 4987.29  101.74
 5000.99   95.49 5005.29   95.23 5010.59   95.34 5012.69   99.08 5048.09   110.7
  5257.9   110.1  5617.9   111.5  6167.9   111.8  6207.9   112.7  6227.9   111.1
  7537.9   111.7  7707.9     113  7926.6   113.1  8377.9   111.3  8439.6   113.5
#Mann= 4 , 1 , 0
  2558.9      .1       0 4953.29    .035       0 5048.09     .14       0
  7926.6     .99       0
#XS Ineff= 2 , 0
       0  3724.8   114.4  6207.9       0   112.7
Permanent Ineff=
       F       F
Bank Sta=4953.29,5048.09
XS Rating Curve= 0 ,0
Exp/Cntr=0.3,0.1

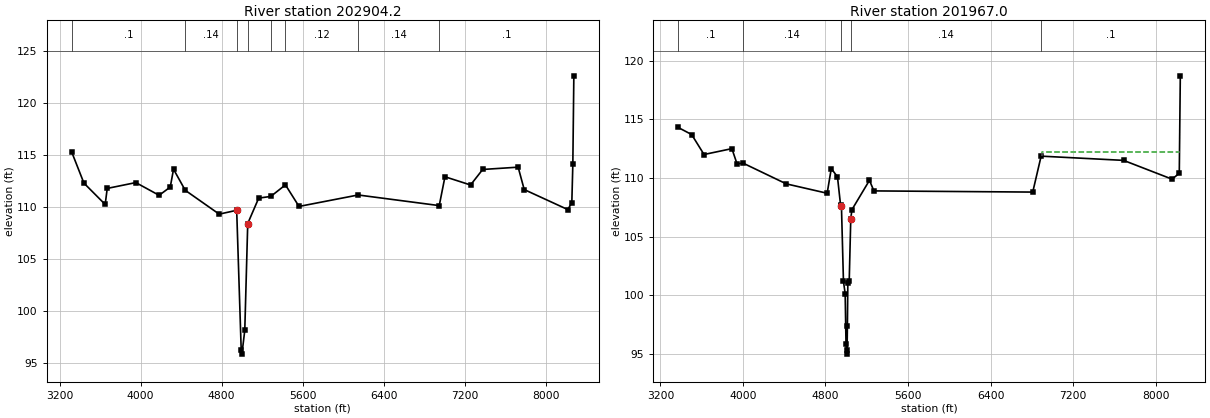
Type RM Length L Ch R = 1 ,202904.2,754.4,937.2,998.6
BEGIN DESCRIPTION:
Cross Section 202904.2
END DESCRIPTION:
XS GIS Cut Line= 6
      3073407.07     13909772.41      3073602.66     13909170.91
      3073602.66     13908818.46      3073492.52      13907838.2
      3073580.64     13906340.27       3073602.1     13904858.28
#Sta/Elev= 30
  3319.7  115.24  3439.7  112.27  3649.7  110.22  3669.7  111.76  3952.1  112.32
  4182.1   111.1  4292.1  111.89  4324.6   113.6  4440.1  111.58  4775.5  109.29
  4948.1  109.66  4992.9   96.21  4999.6   95.85    5028   98.13  5057.2  108.39
  5165.5  110.83  5284.5  110.99  5429.5   112.1  5563.6  110.03  6147.5  111.13
  6948.2  110.11  7004.6  112.88  7257.3  112.09  7377.3  113.58  7727.3   113.8
  7787.3  111.65  8217.3  109.73  8257.3  110.39  8267.3  114.06  8277.3  122.57
#Mann= 8 , 1 , 0
  3319.7      .1       0  4440.1     .14       0  4948.1    .035       0
  5057.2     .14       0  5284.5      .2       0  5429.5     .12       0
  6147.5     .14       0  6948.2      .1       0
#XS Ineff= 2 , 0
       0  4324.6   113.6  7004.6       0  112.88
Permanent Ineff=
       F       F
Bank Sta=4948.1,5057.2
XS Rating Curve= 0 ,0
Exp/Cntr=0.3,0.1

Type RM Length L Ch R = 1 ,201967.0,120.9,234,257.7
BEGIN DESCRIPTION:
Cross Section 201967.0-Interpolated
END DESCRIPTION:
XS GIS Cut Line= 6
      3073672.22     13909464.28      3073860.99     13908897.98
      3074399.21     13908395.54      3074466.65     13907836.57
      3074527.85     13907625.78      3074630.39      13904877.6
#Sta/Elev= 30
  3373.1   114.3  3503.1   113.7  3623.1     112  3893.1   112.5  3943.1   111.2
  4000.2  111.27    4420   109.5  4816.3   108.7  4856.3   110.8  4916.3   110.1
  4946.3   107.7 4954.85   107.6 4974.35  101.19 4990.85  100.16 4999.05   95.88
 5005.65      95 5009.35   95.38 5012.55   97.37 5016.75  101.06 5030.25  101.25
 5045.15  106.53  5056.3   107.3  5226.3   109.8  5269.4   108.9  6808.8   108.8
    6890  111.86    7689   111.5    8159   109.9    8229   110.4    8239   118.7
#Mann= 5 , 1 , 0
  3373.1      .1       0  4000.2     .14       0 4954.85    .035       0
 5045.15     .14       0    6890      .1       0
#XS Ineff= 2 , 0
       0                    6899       0   112.2
Permanent Ineff=
       F       F
Bank Sta=4954.85,5045.15
XS Rating Curve= 0 ,0
Exp/Cntr=0.3,0.1