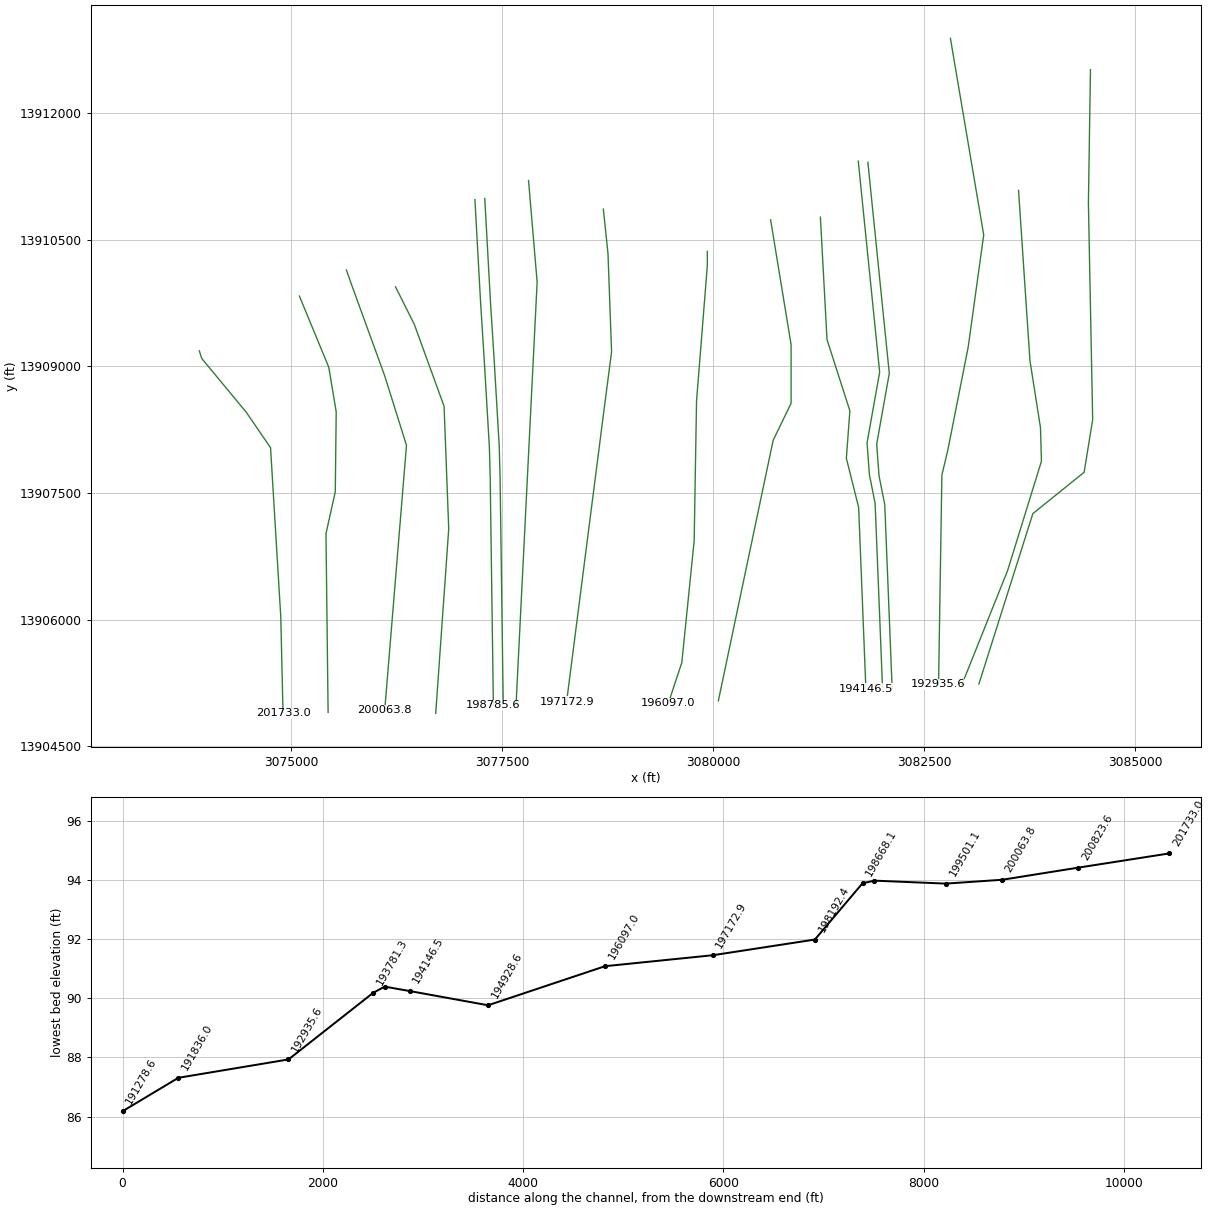
HEC-RAS study P100-00-00.prj: P100-00-00

--- P100-00-00.g01 (geometry) --- (continued)

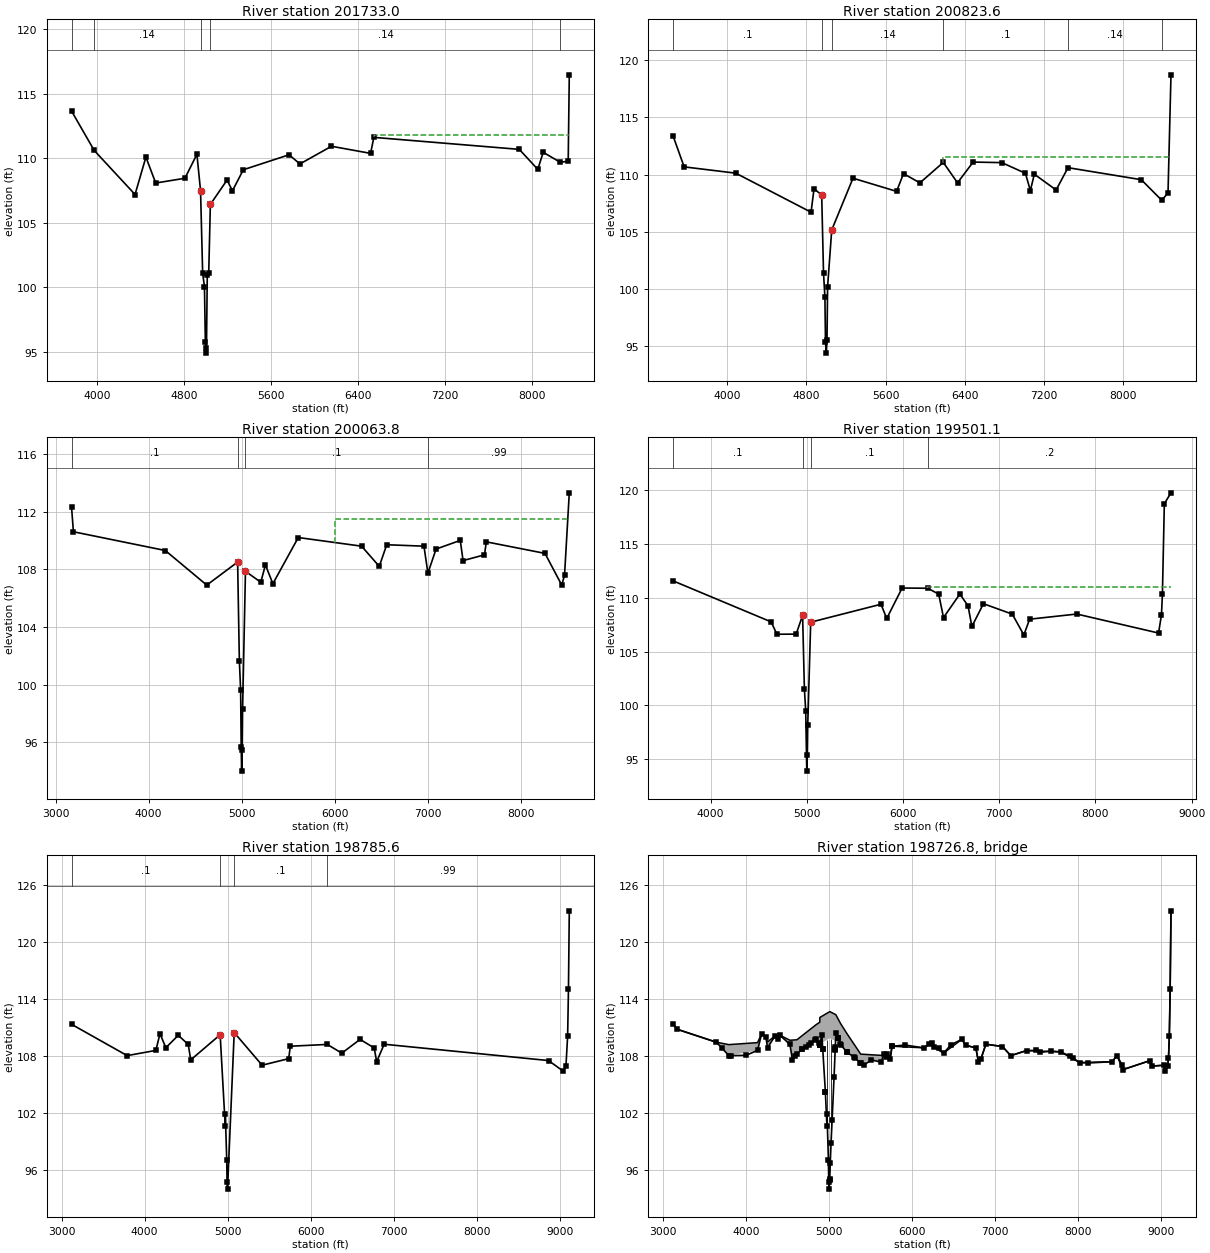
Type RM Length L Ch R = 1 ,201733.0,1120,909.4,642.6
BEGIN DESCRIPTION:
Cross Section 201733.0
END DESCRIPTION:
XS GIS Cut Line= 6
      3073915.26     13909183.39       3073944.1     13909093.82
      3074472.78     13908454.99      3074759.15     13908036.45
      3074880.31     13906031.87      3074906.84     13904892.19
#Sta/Elev= 30
  3768.1  113.66  3976.2  110.61  4352.2  107.19  4452.2  110.09  4542.2  108.08
  4811.4  108.45  4921.4  110.31 4954.85  107.49 4974.35  101.08 4990.85  100.05
 4999.05   95.77 5005.65   94.89 5009.35   95.27 5016.75  100.95 5030.25  101.14
 5045.15  106.42  5198.5  108.31  5248.5  107.48  5348.5  109.11  5769.3  110.27
  5869.3  109.56  6159.3  110.93  6519.3  110.38  6549.3  111.62  7887.4  110.69
  8057.4  109.14  8107.4  110.46  8266.4  109.68  8337.4  109.78  8347.4  116.47
#Mann= 5 , 1 , 0
  3768.1      .1       0  3976.2     .14       0 4954.85    .035       0
 5045.15     .14       0  8266.4      .1       0
#XS Ineff= 2 , 0
       0                  6549.3       0  111.82
Permanent Ineff=
       F       F
Bank Sta=4954.85,5045.15
XS Rating Curve= 0 ,0
Exp/Cntr=0.3,0.1

Type RM Length L Ch R = 1 ,200823.6,606.3,759.8,865.4
BEGIN DESCRIPTION:
Cross Section 200823.6
END DESCRIPTION:
XS GIS Cut Line= 6
      3075100.88     13909832.35      3075448.64     13908990.28
      3075536.75      13908461.6      3075525.74     13907514.38
       3075415.6     13907018.74      3075440.82       13904901.
#Sta/Elev= 30
  3455.1  113.34  3565.1  110.68  4086.5  110.13  4846.7  106.72  4876.7  108.77
  4954.1  108.22  4972.6  101.38  4986.5   99.33  4992.5   95.38  5000.8   94.41
  5007.6    95.6  5013.8  100.22  5055.4  105.17  5270.3  109.69  5710.3  108.54
  5780.3  110.09  5945.7  109.28  6181.9  111.07  6325.7  109.29  6483.4   111.1
  6773.4  111.05  7011.3  110.12  7061.3  108.61  7101.3  110.04  7321.3  108.66
  7441.1  110.61  8181.3  109.56  8388.3  107.76  8451.3  108.41  8481.3  118.72
#Mann= 6 , 1 , 0
  3455.1      .1       0  4954.1    .035       0  5055.4     .14       0
  6181.9      .1       0  7441.1     .14       0  8388.3      .1       0
#XS Ineff= 2 , 0
       0                  6175.4       0   111.5
Permanent Ineff=
       F       F
Bank Sta=4954.1,5055.4
XS Rating Curve= 0 ,0
Exp/Cntr=0.3,0.1

Type RM Length L Ch R = 1 ,200063.8,540.7,562.7,568.9
BEGIN DESCRIPTION:
Cross Section 200063.8-Interpolated
END DESCRIPTION:
XS GIS Cut Line= 5
      3075657.35     13910141.04      3075719.63     13909964.87
      3076111.11      13908888.3      3076369.16     13908064.98
      3076111.11     13904924.56
#Sta/Elev= 30
  3172.4   112.3  3192.4   110.6  4179.2   109.3  4624.8   106.9  4956.2   108.5
  4974.7  101.66  4988.5   99.61  4994.5   95.66  4999.4      94  5005.4   95.48
  5009.5   98.29  5040.4  107.86  5204.8   107.1  5254.8   108.3  5334.8     107
  5607.6   110.2  6287.6   109.6  6477.6   108.2  6557.6   109.7  6957.6   109.6
    7000  107.73  7087.6   109.4  7347.6     110  7377.6   108.6  7607.6     109
  7627.6   109.9  8257.6   109.1  8437.6   106.9  8467.6   107.6  8518.6   113.3
#Mann= 4 , 1 , 0
  3172.4      .1       0  4956.2    .035       0  5040.4      .1       0
    7000     .99       0
#XS Ineff= 2 , 0
       0                    6000       0   111.5
Permanent Ineff=
       F       F
Bank Sta=4956.2,5040.4
XS Rating Curve= 0 ,0
Exp/Cntr=0.3,0.1

Type RM Length L Ch R = 1 ,199501.1,785.1,715.55,444.3
BEGIN DESCRIPTION:
Cross Section 199501.1
END DESCRIPTION:
XS GIS Cut Line= 5
      3076239.59     13909941.66      3076461.95     13909496.93
       3076814.4     13908527.69      3076869.47     13907073.81
      3076715.28     13904890.14
#Sta/Elev= 30
  3611.9  111.57  4629.1  107.76  4689.1  106.61  4889.1  106.62  4956.2  108.37
  4974.7  101.53  4988.5   99.48  4999.4   93.87  5005.4   95.35  5009.5   98.16
  5040.4  107.73  5770.5   109.4  5830.5  108.08  5990.5  110.91  6257.7  110.89
  6370.5  110.34  6420.5  108.16  6590.5  110.35  6675.4  109.25  6715.4  107.33
  6835.4  109.45  7135.4  108.48  7255.4  106.54  7315.4  108.01  7805.4  108.49
  8655.4  106.72  8685.4  108.41  8695.4  110.33  8715.4  118.76  8784.5  119.77
#Mann= 4 , 1 , 0
  3611.9      .1       0  4956.2    .035       0  5040.4      .1       0
  6257.7      .2       0
#XS Ineff= 2 , 0
       0                  6250.5       0  110.96
Permanent Ineff=
       F       F
Bank Sta=4956.2,5040.4
XS Rating Curve= 0 ,0
Exp/Cntr=0.5,0.3

Type RM Length L Ch R = 1 ,198785.6,117.5,117.5,117.5
BEGIN DESCRIPTION:
Upstream Section of Bridge/Culvert/Weir
END DESCRIPTION:
XS GIS Cut Line= 6
      3077179.64      13910975.2       3077246.1     13909769.41
       3077292.5     13909034.53      3077351.01     13908040.89
        3077361.     13907661.21       3077398.2     13904985.41
#Sta/Elev= 30
  3119.7  111.34  3789.7  108.04  4135.1  108.59  4185.1  110.36  4255.1  108.87
  4405.1  110.18  4525.1  109.22  4555.1  107.59  4909.7  110.24  4970.5  100.66
  4971.7  101.93  4988.8   97.02  4992.6   94.77  4998.3   93.97  5078.8  110.47
  5414.8  107.03  5734.9  107.72  5754.9  109.03  6199.7  109.22  6374.9   108.3
  6594.9  109.75  6764.9  108.85  6794.9   107.4  6884.9  109.24  8864.9  107.52
  9044.9  106.38  9074.9  106.97  9094.9  110.11  9104.9  115.02  9114.9   123.3
#Mann= 4 , 1 , 0
  3119.7      .1       0  4909.7    .035       0  5078.8      .1       0
  6199.7     .99       0
#XS Ineff= 2 , 0
       0    4911   109.8    5081       0   108.2
Permanent Ineff=
       F       F
Bank Sta=4909.7,5078.8
XS Rating Curve= 0 ,0
Exp/Cntr=0.5,0.3

Type RM Length L Ch R = 3 ,198726.8,,,
BEGIN DESCRIPTION:
BAMMEL NORTH HOUSTON ROAD
Structure ID: P00-78
END DESCRIPTION:
Bridge Culvert--1,0,-1,-1, 0
Deck Dist Width WeirC Skew NumUp NumDn MinLoCord MaxHiCord MaxSubmerge Is_Ogee
10,97.5,2.6,0, 60, 60, , , 0.95, 0, 1,1,,
  3119.7  3169.7  3639.7  3789.7  4135.1  4185.1  4235.1  4255.1  4345.1  4385.1
  4405.1  4525.1  4555.1  4608.8  4838.8  4884.7 4885.09  4885.2  4909.7 4920.31
  4920.4  5004.9 5070.39  5070.5  5078.8    5134  5212.7  5377.5  5504.8  5624.8
  5654.8  5734.9  5754.9  6134.9  6234.9  6254.9  6374.9  6594.9  6644.9  6764.9
  6794.9  6824.9  6884.9  7084.9  7184.9  7374.9  7784.9  8014.9  8404.9  8464.9
  8534.9  8864.9  8884.9  9024.9  9044.9  9074.9  9084.9  9094.9  9104.9  9114.9
  111.34  110.81  109.45   109.2  109.41  110.37  110.03  109.48  110.11  109.79
  110.19  109.66  109.68  109.71  111.29  111.56  111.56  112.06  112.19  112.24
  112.24  112.68  112.39  112.39  112.34  111.44  110.35   108.2  108.13  108.07
  108.19  108.01  109.03  108.86  109.42  108.95   108.3  109.75  109.13  108.85
   107.4  107.66  109.24     109  108.04  108.57  108.43  107.31   107.4  108.04
  106.56  107.52  106.94  107.02  106.38  106.97  107.75  110.11  115.02   123.3
  111.34  110.81  109.45  108.04  108.59  110.36  110.02  108.87   110.1  109.78
  110.18  109.22  107.59  108.18  109.81  109.19  109.21  109.21  110.24  108.73
  109.44  109.88  109.59  108.72  110.47  109.24  108.37  107.22  107.59  107.35
  108.18  107.72  109.03  108.86  109.42  108.95   108.3  109.75  109.13  108.85
   107.4  107.66  109.24     109  108.04  108.57  108.43  107.31   107.4  108.04
  106.56  107.52  106.94  107.02  106.38  106.97  107.75  110.11  115.02   123.3
  3119.7  3169.7  3639.7  3789.7  4135.1  4185.1  4235.1  4255.1  4345.1  4385.1
  4405.1  4525.1  4555.1  4608.8  4838.8  4884.7 4885.09  4885.2  4909.7 4920.31
  4920.4  5004.9 5070.39  5070.5  5078.8    5134  5212.7  5377.5  5504.8  5624.8
  5654.8  5734.9  5754.9  6134.9  6234.9  6254.9  6374.9  6594.9  6644.9  6764.9
  6794.9  6824.9  6884.9  7084.9  7184.9  7374.9  7784.9  8014.9  8404.9  8464.9
  8534.9  8864.9  8884.9  9024.9  9044.9  9074.9  9084.9  9094.9  9104.9  9114.9
  111.34  110.81  109.45   109.2  109.41  110.37  110.03  109.48  110.11  109.79
  110.19  109.66  109.68  109.71  111.29  111.56  111.56  112.06  112.19  112.24
  112.24  112.68  112.39  112.39  112.34  111.44  110.35   108.2  108.13  108.07
  108.19  108.01  109.03  108.86  109.42  108.95   108.3  109.75  109.13  108.85
   107.4  107.66  109.24     109  108.04  108.57  108.43  107.31   107.4  108.04
  106.56  107.52  106.94  107.02  106.38  106.97  107.75  110.11  115.02   123.3
  111.29  110.76   109.4  107.99  108.54  110.31  109.97  108.82  110.05  109.73
  110.13  109.17  107.54  108.13  109.76  109.14  109.16  109.16  110.19  108.68
  109.39  109.83  109.54  108.67  110.42  109.19  108.32  107.17  107.54   107.3
  108.13  107.67  108.98  108.81  109.37   108.9  108.25   109.7  109.08   108.8
  107.35  107.61  109.19  108.95  107.99  108.52  108.38  107.26  107.35  107.99
  106.51  107.47  106.89  106.97  106.33  106.92   107.7  110.06  114.97  123.25
Pier Skew, UpSta & Num, DnSta & Num=  ,4970.5, 2 ,4970.5, 2 , 0 , 0 , 0 ,,
     1.4     1.4
    99.8  110.71
     1.4     1.4
   99.75  110.66
Pier Skew, UpSta & Num, DnSta & Num=  ,5020.3, 2 ,5020.3, 2 , 0 , 0 , 0 ,,
     1.4     1.4
   97.67  110.81
     1.4     1.4
   97.62  110.76
Abutment Skew #Up #Dn= , 2 , 2
  4920.2  4952.2
  109.44  104.19
  4920.2  4952.2
  109.39  104.14
BR Coef= 1 , 1 , 0 ,1.25, 0 ,,,0.8,0,2,0,
WSPro=,,,, 1 ,,,, 0 ,,,, 0 ,,,,-1 ,-1 ,-1 , 0 , 0 , 0 , 0 , 0
BR U #Sta/Elev= 109
  3119.7  111.34  3169.7  110.81  3639.7  109.45    3708  108.81  3789.7  108.04
    3813  108.04  3995.1  108.07  4135.1  108.59  4185.1  110.36  4235.1  110.02
  4255.1  108.87  4345.1   110.1  4385.1  109.78  4405.1  110.18  4525.1  109.22
  4555.1  107.59  4590.5  108.02  4608.8  108.18  4667.4   108.7  4673.5  108.73
  4723.5  108.94  4756.1  109.19  4783.2  109.39  4822.1  109.68  4838.8  109.81
  4872.2  109.36  4884.7  109.19 4885.09  109.21  4885.2  109.21 4885.31  109.22
  4909.7  110.24 4920.31  108.73  4920.4  108.72  4952.1  104.21  4952.2  104.19
  4970.5  100.66  4971.7  101.93  4988.8   97.02  4992.6   94.77  4998.3   93.97
  5003.9   94.89  5004.9   95.06  5011.1   96.77  5020.3   98.83  5033.1  101.24
  5056.5  105.76  5070.3  108.67 5070.39  108.69  5070.5  108.72  5071.4  108.91
  5078.8  110.47 5104.29   109.9  5104.4   109.9 5104.51   109.9    5134  109.24
  5136.4  109.21  5212.7  108.37  5213.1  108.37  5302.6  107.87  5306.1  107.84
    5375  107.23  5377.5  107.22  5414.8  107.03  5504.8  107.59  5624.8  107.35
  5654.8  108.18  5684.8  107.88  5694.9  108.16  5734.9  107.72  5754.8  109.02
  5754.9  109.03  5914.9  109.15  6134.9  108.86  6199.7  109.22  6234.9  109.42
  6254.9  108.95  6314.9  108.83  6374.9   108.3  6464.9  109.18  6594.9  109.75
  6644.9  109.13  6764.9  108.85  6794.9   107.4  6824.9  107.66  6884.9  109.24
  7084.9     109  7184.9  108.04  7374.9  108.57  7484.9  108.59  7534.9  108.37
  7664.9  108.53  7784.9  108.43  7894.9  108.01  7934.9  107.79  8014.9  107.31
  8114.9  107.26  8404.9   107.4  8464.9  108.04  8524.9  107.07  8534.9  106.56
  8864.9  107.52  8884.9  106.94  9024.9  107.02  9044.9  106.38  9074.9  106.97
  9084.9  107.75  9094.9  110.11  9104.9  115.02  9114.9   123.3
BR U #Mann= 4
  3119.7      .1  4909.7    .035  5078.8      .1  6199.7     .99
BR U Banks=4909.7,5078.8
BR D #Sta/Elev= 109
  3119.7  111.29  3169.7  110.76  3639.7   109.4    3708  108.76  3789.7  107.99
    3813  107.99  3995.1  108.02  4135.1  108.54  4185.1  110.31  4235.1  109.97
  4255.1  108.82  4345.1  110.05  4385.1  109.73  4405.1  110.13  4525.1  109.17
  4555.1  107.54  4590.5  107.97  4608.8  108.13  4667.4  108.65  4673.5  108.68
  4723.5  108.89  4756.1  109.14  4783.2  109.34  4822.1  109.63  4838.8  109.76
  4872.2  109.31  4884.7  109.14 4885.09  109.16  4885.2  109.16 4885.31  109.17
  4909.7  110.19 4920.31  108.68  4920.4  108.67  4952.1  104.16  4952.2  104.14
  4970.5  100.61  4971.7  101.88  4988.8   96.97  4992.6   94.72  4998.3   93.92
  5003.9   94.84  5004.9   95.01  5011.1   96.72  5020.3   98.78  5033.1  101.19
  5056.5  105.71  5070.3  108.62 5070.39  108.64  5070.5  108.67  5071.4  108.86
  5078.8  110.42 5104.29  109.85  5104.4  109.85 5104.51  109.85    5134  109.19
  5136.4  109.16  5212.7  108.32  5213.1  108.32  5302.6  107.82  5306.1  107.79
    5375  107.18  5377.5  107.17  5414.8  106.98  5504.8  107.54  5624.8   107.3
  5654.8  108.13  5684.8  107.83  5694.9  108.11  5734.9  107.67  5754.8  108.97
  5754.9  108.98  5914.9   109.1  6134.9  108.81  6199.7  109.17  6234.9  109.37
  6254.9   108.9  6314.9  108.78  6374.9  108.25  6464.9  109.13  6594.9   109.7
  6644.9  109.08  6764.9   108.8  6794.9  107.35  6824.9  107.61  6884.9  109.19
  7084.9  108.95  7184.9  107.99  7374.9  108.52  7484.9  108.54  7534.9  108.32
  7664.9  108.48  7784.9  108.38  7894.9  107.96  7934.9  107.74  8014.9  107.26
  8114.9  107.21  8404.9  107.35  8464.9  107.99  8524.9  107.02  8534.9  106.51
  8864.9  107.47  8884.9  106.89  9024.9  106.97  9044.9  106.33  9074.9  106.92
  9084.9   107.7  9094.9  110.06  9104.9  114.97  9114.9  123.25
BR D #Mann= 4
  3119.7      .1  4909.7    .035  5078.8      .1  6199.7     .99
BR D Banks=4909.7,5078.8
BC Design=,, 0 ,, 0 ,,,,,,
BC HTab HWMax=123.3
BC Use User HTab Curves=0
BC User HTab FreeFlow(D)= 0

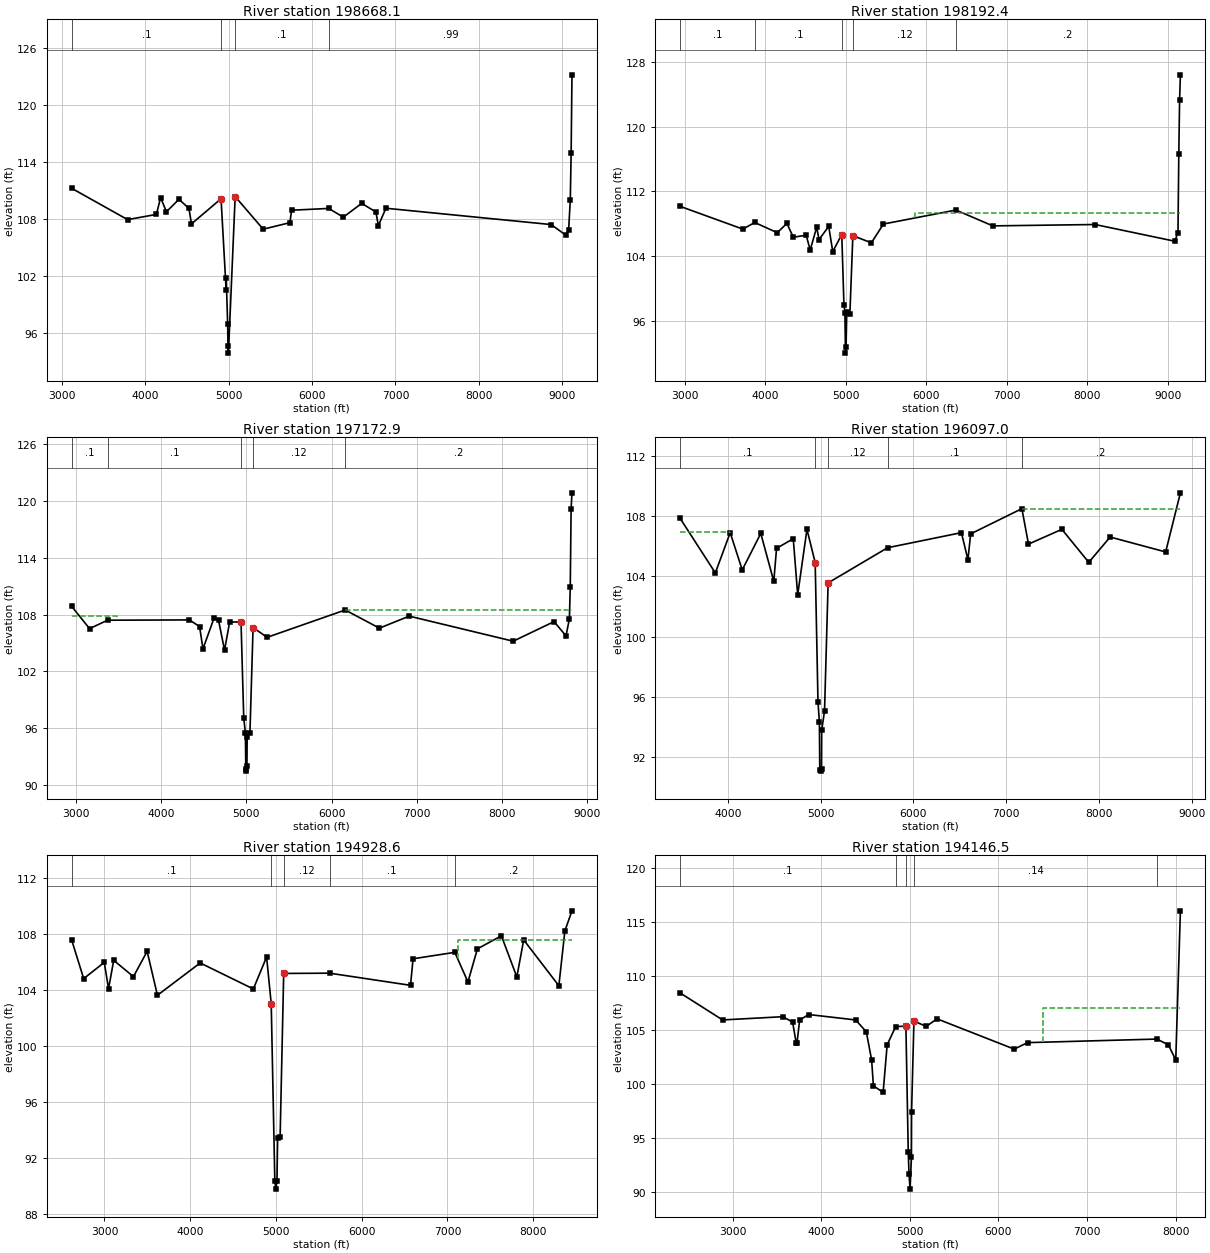
Type RM Length L Ch R = 1 ,198668.1,475.65,475.65,475.65
BEGIN DESCRIPTION:
Downstream Section of Bridge/Culvert/Weir
END DESCRIPTION:
XS GIS Cut Line= 6
      3077296.38     13910988.54      3077362.84     13909782.75
      3077409.24     13909047.87      3077467.75     13908054.23
      3077477.74     13907674.55      3077514.94     13904998.75
#Sta/Elev= 30
  3119.7  111.25  3789.7  107.95  4135.1   108.5  4185.1  110.27  4255.1  108.78
  4405.1  110.09  4525.1  109.13  4555.1   107.5  4909.7  110.15  4970.5  100.57
  4971.7  101.84  4988.8   96.93  4992.6   94.68  4998.3   93.88  5078.8  110.38
  5414.8  106.94  5734.9  107.63  5754.9  108.94  6199.7  109.13  6374.9  108.21
  6594.9  109.66  6764.9  108.76  6794.9  107.31  6884.9  109.15  8864.9  107.43
  9044.9  106.29  9074.9  106.88  9094.9  110.02  9104.9  114.93  9114.9  123.21
#Mann= 4 , 1 , 0
  3119.7      .1       0  4909.7    .035       0  5078.8      .1       0
  6199.7     .99       0
#XS Ineff= 2 , 0
       0    4911   109.5    5081       0   107.9
Permanent Ineff=
       F       F
Bank Sta=4909.7,5078.8
XS Rating Curve= 0 ,0
Exp/Cntr=0.5,0.3

Type RM Length L Ch R = 1 ,198192.4,1092.6,1019.5,821.4
BEGIN DESCRIPTION:
Cross Section 198192.4
END DESCRIPTION:
XS GIS Cut Line= 3
      3077814.75     13911200.54      3077916.66     13909998.22
      3077666.94     13904994.38
#Sta/Elev= 30
  2942.1  110.16  3722.1  107.34  3869.5  108.16  4148.8   106.9  4268.8  108.04
  4348.8  106.34  4508.8  106.58  4558.8  104.75  4638.8  107.57  4668.8  106.05
  4788.8  107.68  4838.8  104.56  4950.9  106.67  4977.8   97.97  4989.9   96.99
  4996.9   91.98  5004.1   92.71  5012.9   97.13  5051.9   96.88  5088.6  106.53
  5318.8  105.64  5468.8  107.97  6369.1   109.7  6828.8  107.74  8098.8  107.91
  9088.8  105.84  9128.8  106.92  9138.8  116.61  9148.8  123.36  9158.8  126.45
#Mann= 5 , 1 , 0
  2942.1      .1       0  3869.5      .1       0  4950.9    .035       0
  5088.6     .12       0  6369.1      .2       0
#XS Ineff= 2 , 0
       0                  5858.8       0  109.33
Permanent Ineff=
       F       F
Bank Sta=4950.9,5088.6
XS Rating Curve= 0 ,0
Exp/Cntr=0.3,0.1

Type RM Length L Ch R = 1 ,197172.9,1072.6,1075.9,1204
BEGIN DESCRIPTION:
Cross Section 197172.9
END DESCRIPTION:
XS GIS Cut Line= 5
      3078700.88     13910862.79       3078755.8     13910334.75
      3078798.32     13909172.49      3078713.28     13908520.49
      3078265.89     13905029.09
#Sta/Elev= 30
  2950.1  108.87  3160.1  106.52  3371.4  107.41    4331  107.44    4451  106.74
    4491  104.38    4621  107.64    4674  107.39    4744  104.24    4804  107.21
  4937.5  107.23  4969.4   97.07  4988.7    95.5  4993.7   91.71  4999.3   91.45
  5006.7   91.95  5009.5   95.02    5042   95.45  5078.9  106.63    5244   105.6
  6160.1  108.49  6561.5  106.57  6911.5  107.84  8131.5  105.19  8611.5  107.26
  8751.5  105.75  8791.5  107.57  8801.5  110.97  8811.5  119.22  8821.5  120.88
#Mann= 5 , 1 , 0
  2950.1      .1       0  3371.4      .1       0  4937.5    .035       0
  5078.9     .12       0  6160.1      .2       0
#XS Ineff= 2 , 0
       0    3481  107.87  6161.5       0  108.53
Permanent Ineff=
       F       F
Bank Sta=4937.5,5078.9
XS Rating Curve= 0 ,0
Exp/Cntr=0.3,0.1

Type RM Length L Ch R = 1 ,196097.0,1185.7,1168.4,881.7
BEGIN DESCRIPTION:
Cross Section 196097.0
END DESCRIPTION:
XS GIS Cut Line= 6
      3079932.23     13910362.71      3079932.23     13910193.01
      3079804.66     13908591.36      3079776.32     13906933.02
      3079630.11      13905491.8      3079470.23     13905008.63
#Sta/Elev= 30
  3485.7  107.84  3865.4  104.22  4025.4  106.89  4155.4  104.42  4355.4  106.84
  4495.4  103.66  4525.4  105.85  4705.4  106.49  4753.1  102.77  4853.1  107.11
  4941.8   104.9  4971.9   95.68    4987   94.34  4991.1   91.14  5000.1   91.08
    5010    91.2  5012.3   93.81  5042.5   95.07  5081.3  103.56  5722.4  105.89
    6518  106.89    6588   105.1    6618  106.81  7169.8  108.48    7241  106.13
    7601  107.11    7891  104.92    8121   106.6  8719.7  105.61  8878.6  109.53
#Mann= 5 , 1 , 0
  3485.7      .1       0  4941.8    .035       0  5081.3     .12       0
  5722.4      .1       0  7169.8      .2       0
#XS Ineff= 2 , 0
       0  4025.4  106.95    7171       0  108.48
Permanent Ineff=
       F       F
Bank Sta=4941.8,5081.3
XS Rating Curve= 0 ,0
Exp/Cntr=0.3,0.1

Type RM Length L Ch R = 1 ,194928.6,489.7,782.1,1197.8
BEGIN DESCRIPTION:
Cross Section 194928.6
END DESCRIPTION:
XS GIS Cut Line= 5
      3080681.79     13910736.32       3080924.4     13909257.54
       3080924.4     13908563.02      3080711.79     13908123.63
      3080062.69     13905038.25
#Sta/Elev= 30
  2617.9  107.58  2757.9  104.82  2997.9  105.98  3047.9  104.09  3107.9  106.13
  3337.9  104.96  3497.9  106.77  3617.9  103.63  4116.4  105.94  4736.4  104.08
  4890.9  106.37  4944.9  103.02    4987   90.31  4999.3   89.76  5011.9   90.36
  5019.5   93.41  5048.6   93.48  5090.3  105.19    5625  105.21  6569.1  104.34
  6599.1  106.24  7085.6   106.7  7239.1  104.58  7349.1  106.95  7629.1  107.88
  7809.1  104.94  7889.1  107.59  8299.1  104.31  8369.1  108.23    8452  109.67
#Mann= 5 , 1 , 0
  2617.9      .1       0  4944.9    .035       0  5090.3     .12       0
    5625      .1       0  7085.6      .2       0
#XS Ineff= 2 , 0
       0  3497.9  106.77  7119.1       0  107.57
Permanent Ineff=
       F       F
Bank Sta=4944.9,5090.3
XS Rating Curve= 0 ,0
Exp/Cntr=0.3,0.1

Type RM Length L Ch R = 1 ,194146.5,548.3,250.2,205.7
BEGIN DESCRIPTION:
Cross Section 194146.5-Interpolated
END DESCRIPTION:
XS GIS Cut Line= 6
      3081271.43     13910766.93      3081350.01     13909316.89
      3081620.63     13908473.78        3081579.     13907911.71
      3081724.72     13907328.82      3081810.08      13905184.2
#Sta/Elev= 30
  2406.2   108.4  2886.2   105.9  3566.2   106.2  3676.2   105.7  3716.2   103.8
  3726.2   103.8  3756.2   105.9  3858.4   106.4  4388.4   105.9  4508.4   104.8
  4568.4   102.2  4588.4    99.8  4698.4    99.2  4743.8   103.6  4839.7  105.28
 4955.38  105.33 4982.08   93.65 4990.68   91.64 5002.48   90.24 5017.98   93.21
 5019.28   97.36 5046.18   105.8  5183.8   105.3  5307.4     106  6178.3   103.2
  6328.3   103.8  7788.5  104.13  7918.3   103.6  8002.1   102.2  8054.6     116
#Mann= 5 , 1 , 0
  2406.2      .1       0  4839.7     .14       0 4955.38    .035       0
 5046.18     .14       0  7788.5      .1       0
#XS Ineff= 2 , 0
       0  3858.4   106.4    6500       0     107
Permanent Ineff=
       F       F
Bank Sta=4955.38,5046.18
XS Rating Curve= 0 ,0
Exp/Cntr=0.5,0.3

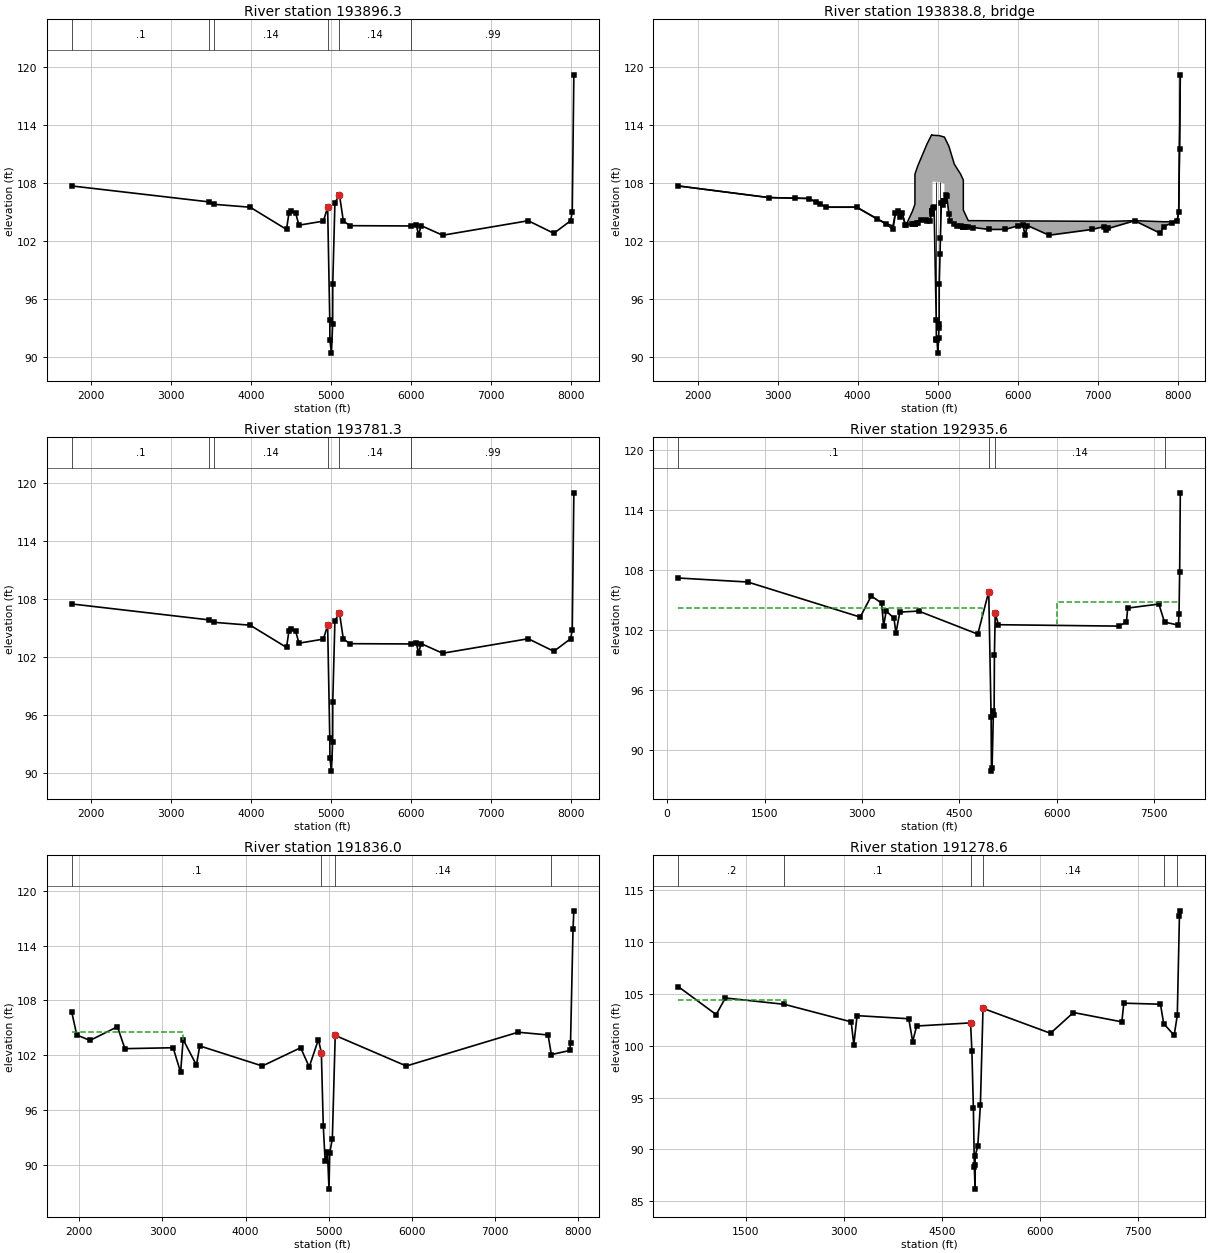
Type RM Length L Ch R = 1 ,193896.3,115,115,115
BEGIN DESCRIPTION:
Upstream Section of Bridge/Culvert/Weir
END DESCRIPTION:
XS GIS Cut Line= 6
      3081719.86     13911431.53      3081973.38     13908931.53
      3081824.21      13908094.3      3081851.87     13907718.16
      3081919.77     13907376.84      3082007.32      13905194.3
#Sta/Elev= 30
  1757.3  107.69  3473.9  106.04    3534  105.79  3987.3  105.49  4441.6  103.19
  4471.6  104.89  4501.6  105.09  4555.2  104.89  4596.9  103.63  4902.4  104.05
  4955.4  105.48  4982.1    93.8  4983.8   91.74  5002.5   90.39    5018   93.36
  5019.3   97.51  5046.2  105.95  5103.1  106.77  5151.6  104.06  5235.5  103.58
    6000  103.55  6062.7  103.69  6092.7  102.59  6122.7  103.59  6392.7  102.59
  7462.7  104.09  7782.7  102.79  7992.7  104.09  8012.7  104.99  8032.7  119.19
#Mann= 6 , 1 , 0
  1757.3      .1       0  3473.9     .07       0    3534     .14       0
  4955.4    .035       0  5103.1     .14       0    6000     .99       0
#XS Ineff= 2 , 0
       0  4955.4   105.2    5095       0   104.4
Permanent Ineff=
       F       F
Bank Sta=4955.4,5103.1
XS Rating Curve= 0 ,0
Exp/Cntr=0.5,0.3

Type RM Length L Ch R = 3 ,193838.8,,,
BEGIN DESCRIPTION:
ANTOINE DRIVE
Structure ID: P00-77
END DESCRIPTION:
Bridge Culvert--1,0,-1,-1, 0
Deck Dist Width WeirC Skew NumUp NumDn MinLoCord MaxHiCord MaxSubmerge Is_Ogee
10,95,2.6,0, 54, 54, , , 0.95, 0, 1,1,,
  1757.3  2887.3  3387.3  3607.3  3987.3  4351.6  4441.6  4471.6  4501.6  4531.6
  4555.2  4596.9  4604.4  4685.3 4715.69  4715.8  4752.4  4796.8  4866.6  4902.4
  4925.1 4935.11  4935.2    5018 5084.09  5084.2  5103.1  5112.8  5140.2  5151.6
  5208.2  5235.5  5286.2  5320.6 5320.71  5382.3  5639.7  5842.7  6062.7  6092.7
  6122.7  6392.7  6932.7  7082.7  7102.7  7132.7  7462.7  7782.7  7822.7  7928.4
  7992.7  8012.7  8022.7  8032.7
   107.7   106.5  106.41  105.51  105.51  103.81  103.57  104.91  105.11  104.51
  104.91  103.65  103.66   105.1  105.82  108.92   109.8  110.67  112.04  112.63
  113.01  112.95  112.95  112.91  112.76  112.76  112.44  112.27  111.81   111.5
  109.95  109.59  108.93  108.31  105.21  104.11   104.1  104.09  104.08  104.08
  104.08  104.07  104.04  104.04  104.04  104.03  104.11  104.01     104     104
   104.1     105   111.5   119.2
   107.7   106.5   106.4   105.5   105.5   103.8   103.2   104.9   105.1   104.5
   104.9  103.64  103.65  103.78   103.8   103.8   103.9  104.16  104.12  104.06
   104.8  105.13  108.15  108.11  107.96  106.19  106.78  106.63  104.82  104.07
  103.75  103.59  103.51  103.46  103.46  103.42   103.2   103.2   103.7   102.6
   103.6   102.6   103.2   103.5   103.1   103.3   104.1   102.8   103.5  103.87
   104.1     105   111.5   119.2
  1757.3  2887.3  3387.3  3607.3  3987.3  4351.6  4441.6  4471.6  4501.6  4531.6
  4555.2  4596.9  4604.4  4685.3 4715.69  4715.8  4752.4  4796.8  4866.6  4902.4
  4925.1 4935.11  4935.2    5018 5084.09  5084.2  5103.1  5112.8  5140.2  5151.6
  5208.2  5235.5  5286.2  5320.6 5320.71  5382.3  5639.7  5842.7  6062.7  6092.7
  6122.7  6392.7  6932.7  7082.7  7102.7  7132.7  7462.7  7782.7  7822.7  7928.4
  7992.7  8012.7  8022.7  8032.7
   107.7   106.5  106.41  105.51  105.51  103.81  103.57  104.91  105.11  104.51
  104.91  103.65  103.66   105.1  105.82  108.92   109.8  110.67  112.04  112.63
  113.01  112.95  112.95  112.91  112.76  112.76  112.44  112.27  111.81   111.5
  109.95  109.59  108.93  108.31  105.21  104.11   104.1  104.09  104.08  104.08
  104.08  104.07  104.04  104.04  104.04  104.03  104.11  104.01     104     104
   104.1     105   111.5   119.2
  107.51  106.31  106.21  105.31  105.31  103.61  103.01  104.71  104.91  104.31
  104.71  103.45  103.46  103.59  103.61  103.61  103.71  103.97  103.93  103.87
  104.61  104.94  107.96  107.92  107.77     106  106.59  106.44  104.63  103.88
  103.56   103.4  103.32  103.27  103.27  103.23  103.01  103.01  103.51  102.41
  103.41  102.41  103.01  103.31  102.91  103.11  103.91  102.61  103.31  103.68
  103.91  104.81  111.31  119.01
Pier Skew, UpSta & Num, DnSta & Num=  ,4983.8, 2 ,4983.8, 2 , 0 , 0 , 0 ,,
     1.4     1.4
   90.84  109.13
     1.4     1.4
   90.65  108.94
Pier Skew, UpSta & Num, DnSta & Num=  ,5034.1, 2 ,5034.1, 2 , 0 , 0 , 0 ,,
     1.4     1.4
  101.04  109.07
     1.4     1.4
  100.85  108.88
BR Coef= 1 , 1 , 0 ,1.25, 0 ,,,0.8,0,2,0,
WSPro=,,,, 1 ,,,, 0 ,,,, 0 ,,,,-1 ,-1 ,-1 , 0 , 0 , 0 , 0 , 0
BR U #Sta/Elev= 84
  1757.3   107.7  2887.3   106.5  3219.8  106.43  3387.3   106.4  3473.9  106.05
    3534   105.8  3607.3   105.5  3987.3   105.5  4237.9   104.3  4351.6   103.8
  4441.6   103.2  4471.6   104.9  4501.6   105.1  4531.6   104.5  4555.2   104.9
  4596.9  103.64  4604.4  103.65  4685.3  103.78  4688.6  103.78 4715.69   103.8
  4715.8   103.8 4715.91   103.8  4739.7  103.82  4752.4   103.9  4796.8  104.16
  4850.4  104.15  4866.6  104.12  4902.4  104.06  4925.1   104.8    4935  105.13
 4935.11  105.13  4935.2  105.13  4935.3  105.14  4942.4  105.37  4955.4  105.49
  4982.1   93.81  4983.8   91.75  4984.4   91.84  4990.7    91.8  5002.5    90.4
  5011.5   91.99  5016.2   92.99    5018   93.37  5019.3   97.52  5029.9  100.69
  5034.1  102.31  5046.2  105.96  5070.4  105.76    5084  106.18 5084.09  106.19
  5084.2  106.19  5084.3  106.19  5103.1  106.78  5112.8  106.63  5140.2  104.82
  5151.6  104.07  5208.2  103.75  5235.5  103.59  5286.2  103.51 5320.49  103.46
  5320.6  103.46 5320.71  103.46  5342.5  103.43  5382.3  103.42  5446.5   103.4
  5639.7   103.2  5842.7   103.2    6000  103.56  6062.7   103.7  6092.7   102.6
  6122.7   103.6  6392.7   102.6  6932.7   103.2  7082.7   103.5  7102.7   103.1
  7132.7   103.3  7462.7   104.1  7782.7   102.8  7822.7   103.5  7928.4  103.87
  7992.7   104.1  8012.7     105  8022.7   111.5  8032.7   119.2
BR U #Mann= 6
  1757.3      .1  3473.9     .07    3534     .14  4955.4    .035  5103.1     .14
    6000     .99
BR U Banks=4955.4,5103.1
BR D #Sta/Elev= 84
  1757.3  107.51  2887.3  106.31  3219.8  106.24  3387.3  106.21  3473.9  105.86
    3534  105.61  3607.3  105.31  3987.3  105.31  4237.9  104.11  4351.6  103.61
  4441.6  103.01  4471.6  104.71  4501.6  104.91  4531.6  104.31  4555.2  104.71
  4596.9  103.45  4604.4  103.46  4685.3  103.59  4688.6  103.59 4715.69  103.61
  4715.8  103.61 4715.91  103.61  4739.7  103.63  4752.4  103.71  4796.8  103.97
  4850.4  103.96  4866.6  103.93  4902.4  103.87  4925.1  104.61    4935  104.94
 4935.11  104.94  4935.2  104.94  4935.3  104.95  4942.4  105.18  4955.4   105.3
  4982.1   93.62  4983.8   91.56  4984.4   91.65  4990.7   91.61  5002.5   90.21
  5011.5    91.8  5016.2    92.8    5018   93.18  5019.3   97.33  5029.9   100.5
  5034.1  102.12  5046.2  105.77  5070.4  105.57    5084  105.99 5084.09     106
  5084.2     106  5084.3     106  5103.1  106.59  5112.8  106.44  5140.2  104.63
  5151.6  103.88  5208.2  103.56  5235.5   103.4  5286.2  103.32 5320.49  103.27
  5320.6  103.27 5320.71  103.27  5342.5  103.24  5382.3  103.23  5446.5  103.21
  5639.7  103.01  5842.7  103.01    6000  103.37  6062.7  103.51  6092.7  102.41
  6122.7  103.41  6392.7  102.41  6932.7  103.01  7082.7  103.31  7102.7  102.91
  7132.7  103.11  7462.7  103.91  7782.7  102.61  7822.7  103.31  7928.4  103.68
  7992.7  103.91  8012.7  104.81  8022.7  111.31  8032.7  119.01
BR D #Mann= 6
  1757.3      .1  3473.9     .07    3534     .14  4955.4    .035  5103.1     .14
    6000     .99
BR D Banks=4955.4,5103.1
BC Design=,, 0 ,, 0 ,,,,,,
BC HTab HWMax=119.19
BC Use User HTab Curves=0
BC User HTab FreeFlow(D)= 0

Type RM Length L Ch R = 1 ,193781.3,845.7,845.7,845.7
BEGIN DESCRIPTION:
Downstream Section of Bridge/Culvert/Weir
END DESCRIPTION:
XS GIS Cut Line= 6
      3081833.95     13911417.12      3082087.48     13908917.11
      3081938.31     13908079.88      3081965.97     13907703.74
      3082033.87     13907362.42      3082121.42     13905179.88
#Sta/Elev= 30
  1757.3  107.48  3473.9  105.83    3534  105.58  3987.3  105.28  4441.6  102.98
  4471.6  104.68  4501.6  104.88  4555.2  104.68  4596.9  103.42  4902.4  103.84
  4955.4  105.27  4982.1   93.59  4983.8   91.53  5002.5   90.18    5018   93.15
  5019.3    97.3  5046.2  105.74  5103.1  106.56  5151.6  103.85  5235.5  103.37
    6000  103.34  6062.7  103.48  6092.7  102.38  6122.7  103.38  6392.7  102.38
  7462.7  103.88  7782.7  102.58  7992.7  103.88  8012.7  104.78  8032.7  118.98
#Mann= 6 , 1 , 0
  1757.3      .1       0  3473.9     .07       0    3534     .14       0
  4955.4    .035       0  5103.1     .14       0    6000     .99       0
#XS Ineff= 2 , 0
       0  4955.4     105    5095       0   104.2
Permanent Ineff=
       F       F
Bank Sta=4955.4,5103.1
XS Rating Curve= 0 ,0
Exp/Cntr=0.5,0.3

Type RM Length L Ch R = 1 ,192935.6,853.1,1099.6,1151.9
BEGIN DESCRIPTION:
Cross Section 192935.6
END DESCRIPTION:
XS GIS Cut Line= 6
      3082811.33     13912885.32      3083205.85     13910556.79
      3083022.13     13909229.19      3082781.18     13908010.24
      3082710.31     13907712.58      3082671.08     13905232.88
#Sta/Elev= 30
   171.7   107.2  1241.7   106.8  2973.4   103.3  3143.4   105.4  3303.4   104.7
  3333.4   102.4  3373.4   103.9  3493.4   103.2  3523.4   101.7  3583.4   103.8
  3873.7   103.9  4783.7   101.6  4952.4  105.84  4989.1   93.29  4994.3   87.93
  5004.1   88.28  5024.9   93.92  5035.1   93.52    5040   99.47    5052  103.67
  5101.9  102.54  6952.2   102.4  7072.2   102.8  7092.2   104.2  7572.2   104.6
  7658.8   102.8  7872.2   102.5  7882.2   103.6  7892.2   107.8  7902.2   115.7
#Mann= 4 , 1 , 0
   171.7      .1       0  4952.4    .035       0    5052     .14       0
  7658.8     .99       0
#XS Ineff= 2 , 0
       0  4853.7   104.2    6000       0   104.8
Permanent Ineff=
       F       F
Bank Sta=4952.4,5052
XS Rating Curve= 0 ,0
Exp/Cntr=0.3,0.1

Type RM Length L Ch R = 1 ,191836.0,740.9,557.4,89.2
BEGIN DESCRIPTION:
Cross Section 191836.0
END DESCRIPTION:
XS GIS Cut Line= 6
      3083618.28     13911084.29       3083753.5     13909067.61
      3083878.23     13908273.87      3083889.57       13907877.
      3083489.45     13906583.31      3082946.53     13905228.05
#Sta/Elev= 30
  1910.1   106.7  1970.1   104.2  2128.8   103.6  2458.8   105.1  2548.8   102.7
  3128.8   102.8  3218.8   100.1  3248.8   103.7  3408.8   100.9  3448.8     103
  4201.5   100.8  4661.5   102.8  4764.9   100.7  4874.9   103.7  4910.6  102.26
  4933.7   94.25  4956.3   90.34  4984.2   91.33  5002.6   87.31  5011.4   91.27
  5042.8   92.85  5077.3  104.15    5932   100.8  7276.1   104.5  7636.1   104.2
  7675.6  102.05  7896.1   102.5  7906.1   103.3  7936.1   115.8  7946.1   117.8
#Mann= 4 , 1 , 0
  1910.1      .1       0  4910.6    .035       0  5077.3     .14       0
  7675.6      .1       0
#XS Ineff= 2 , 0
       0  3248.8   104.5  7276.1       0   104.5
Permanent Ineff=
       F       F
Bank Sta=4910.6,5077.3
XS Rating Curve= 0 ,0
Exp/Cntr=0.3,0.1

Type RM Length L Ch R = 1 ,191278.6,1675.4,418.5,134.6
BEGIN DESCRIPTION:
Cross Section 191278.6-Interpolated
END DESCRIPTION:
XS GIS Cut Line= 6
      3084470.12     13912514.34      3084445.81     13910934.08
      3084496.42     13908369.79      3084395.19     13907745.59
      3083787.86     13907256.35      3083148.93     13905238.66
#Sta/Elev= 30
   468.3   105.7  1048.3     103  1188.3   104.6  2089.9  103.99  3111.7   102.3
  3151.7   100.1  3201.7   102.9  3991.7   102.6  4051.7   100.4  4111.7   101.9
  4936.5   102.2  4956.5    99.5 4979.45      94 4994.15   88.27 5005.45   86.18
 5005.75   88.46  5006.5    89.4  5046.5    90.3  5086.5    94.3  5126.5   103.6
  6158.7   101.2  6508.7   103.2  7248.7   102.3  7278.7   104.1  7838.7     104
  7888.4  102.13  8048.7     101  8096.2  102.95  8128.7   112.5  8142.2     113
#Mann= 6 , 1 , 0
   468.3      .2       0  2089.9      .1       0  4936.5    .035       0
  5126.5     .14       0  7888.4      .1       0  8096.2      .2       0
#XS Ineff= 2 , 0
       0  2121.7   104.4  7278.7       0   104.1
Permanent Ineff=
       F       F
Bank Sta=4936.5,5126.5
XS Rating Curve= 0 ,0
Exp/Cntr=0.5,0.3