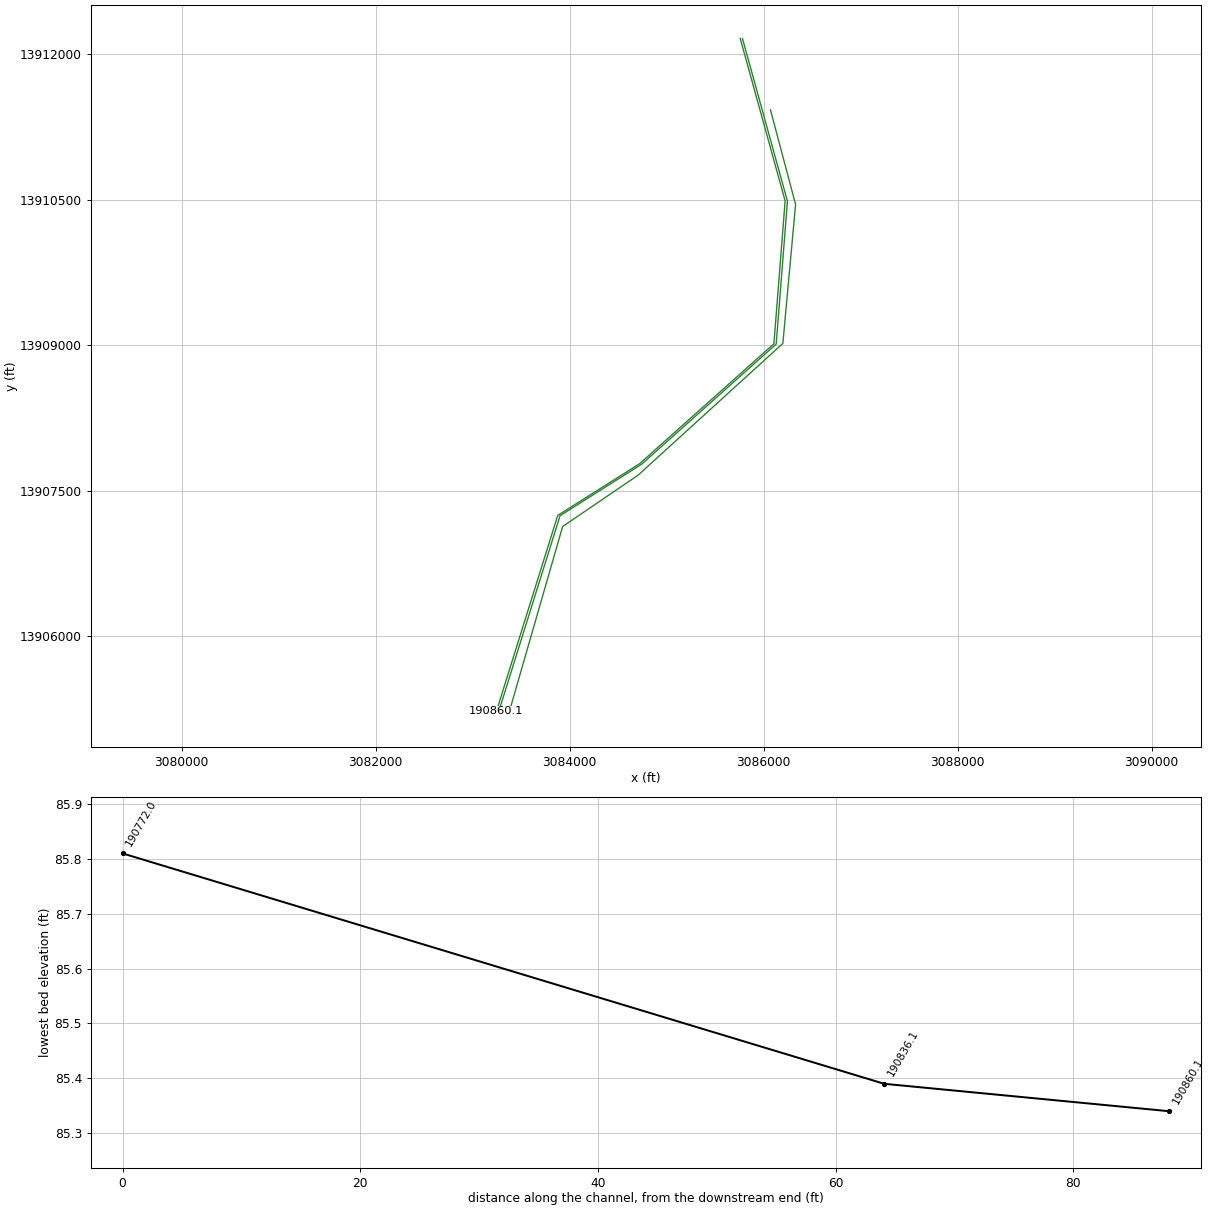
HEC-RAS study P100-00-00.prj: P100-00-00

--- P100-00-00.g01 (geometry) --- (continued)

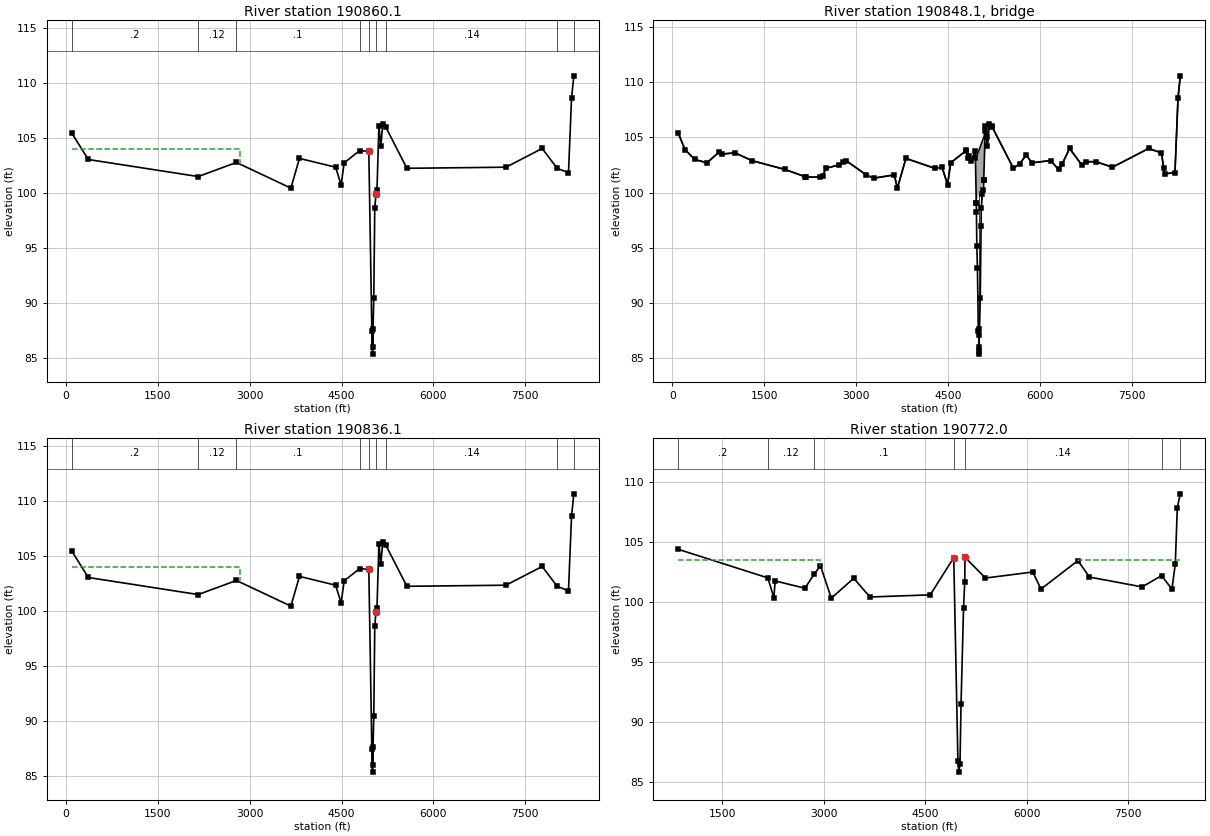
Type RM Length L Ch R = 1 ,190860.1,24,24,24
BEGIN DESCRIPTION:
Upstream Section of Bridge/Culvert/Weir
END DESCRIPTION:
XS GIS Cut Line= 6
      3085759.53     13912163.63       3086222.8     13910487.65
        3086107.     13909014.68      3084720.55     13907776.78
      3083878.78     13907245.61      3083246.17     13905224.96
#Sta/Elev= 30
      96  105.42     366  103.02  2160.2  101.47  2783.1  102.75  3672.4  100.42
  3812.4  103.12  4402.4  102.32  4492.4  100.72  4542.4  102.72    4796  103.83
 4944.25  103.76 4994.15   87.43 5005.45   85.34 5005.75   87.62 5006.45   86.02
 5025.45   90.43 5041.65   98.63 5061.35   99.87 5077.45  100.22 5109.35   106.1
 5140.45  104.21  5171.3  106.22  5218.9  105.99  5566.2  102.22  7183.6  102.32
  7773.6  104.02  8020.6  102.21  8203.6  101.82  8253.6  108.62    8291  110.62
#Mann= 9 , 1 , 0
      96      .2       0  2160.2     .12       0  2783.1      .1       0
    4796     .08       0 4944.25    .035       0 5061.35     .08       0
  5218.9     .14       0  8020.6      .1       0    8291      .2       0
#XS Ineff= 2 , 0
       0  2834.8     104  7773.6       0     104
Permanent Ineff=
       F       F
Bank Sta=4944.25,5061.35
XS Rating Curve= 0 ,0
Exp/Cntr=0.5,0.3

Type RM Length L Ch R = 3 ,190848.1,,,
BEGIN DESCRIPTION:
24" PIPELINE     Skewed 35 Degrees
Structure ID: PL1_P00-75
END DESCRIPTION:
Bridge Culvert--1,0,-1,-1, 0
Deck Dist Width WeirC Skew NumUp NumDn MinLoCord MaxHiCord MaxSubmerge Is_Ogee
10,4,2.6,0, 58, 58, , , 0.95, 0, 1,1,,
      96     206     366     566     766     816    1026    1296  1834.8  2184.8
  2404.8  2454.8  2504.8  2714.8  2834.8  3164.8  3284.8  3622.4  3672.4  3812.4
  4282.4  4402.4  4492.4  4542.4 4799.95 4829.95 4840.45 4876.75 4944.25 4946.45
 4960.36 4960.45 5077.45 5082.34 5106.45 5109.35 5133.75 5140.45  5171.3  5216.2
  5566.2  5666.2    5777    5867  6173.6  6303.6  6363.6  6483.6  6683.6  6753.6
  6913.6  7183.6  7773.6  7983.6  8033.6  8203.6  8253.6    8291
   105.4   103.9     103   102.7   103.7   103.5   103.6   102.9   102.1   101.4
   101.4   101.5   102.2   102.5   102.9   101.6   101.3   101.6   100.4   103.1
   102.2   102.3   100.7   102.7  103.83  103.17  103.29  102.82  103.74  103.12
   103.2   103.2  104.95  105.02  105.56  106.08  105.01  104.19   106.2     106
   102.2   102.6   103.4   102.7   102.9   102.1   102.6     104   102.5   102.8
   102.8   102.3     104   103.6   101.7   101.8   108.6   110.6
   105.4   103.9     103   102.7   103.7   103.5   103.6   102.9   102.1   101.4
   101.4   101.5   102.2   102.5   102.9   101.6   101.3   101.6   100.4   103.1
   102.2   102.3   100.7   102.7  103.83  103.17  103.29  102.82  103.74  103.11
   99.09    99.2  100.95   101.1  105.55  106.08  105.01  104.19   106.2     106
   102.2   102.6   103.4   102.7   102.9   102.1   102.6     104   102.5   102.8
   102.8   102.3     104   103.6   101.7   101.8   108.6   110.6
      96     206     366     566     766     816    1026    1296  1834.8  2184.8
  2404.8  2454.8  2504.8  2714.8  2834.8  3164.8  3284.8  3622.4  3672.4  3812.4
  4282.4  4402.4  4492.4  4542.4 4799.95 4829.95 4840.45 4876.75 4944.25 4946.45
 4960.36 4960.45 5077.45 5082.34 5106.45 5109.35 5133.75 5140.45  5171.3  5216.2
  5566.2  5666.2    5777    5867  6173.6  6303.6  6363.6  6483.6  6683.6  6753.6
  6913.6  7183.6  7773.6  7983.6  8033.6  8203.6  8253.6    8291
   105.4   103.9     103   102.7   103.7   103.5   103.6   102.9   102.1   101.4
   101.4   101.5   102.2   102.5   102.9   101.6   101.3   101.6   100.4   103.1
   102.2   102.3   100.7   102.7  103.83  103.17  103.29  102.82  103.74  103.12
   103.2   103.2  104.95  105.02  105.56  106.08  105.01  104.19   106.2     106
   102.2   102.6   103.4   102.7   102.9   102.1   102.6     104   102.5   102.8
   102.8   102.3     104   103.6   101.7   101.8   108.6   110.6
   105.4   103.9     103   102.7   103.7   103.5   103.6   102.9   102.1   101.4
   101.4   101.5   102.2   102.5   102.9   101.6   101.3   101.6   100.4   103.1
   102.2   102.3   100.7   102.7  103.83  103.17  103.29  102.82  103.74  103.11
   99.09    99.2  100.95   101.1  105.55  106.08  105.01  104.19   106.2     106
   102.2   102.6   103.4   102.7   102.9   102.1   102.6     104   102.5   102.8
   102.8   102.3     104   103.6   101.7   101.8   108.6   110.6
Pier Skew, UpSta & Num, DnSta & Num=  ,4963.5, 2 ,4963.5, 2 , 0 , 0 , 0 ,,
     1.4     1.4
   96.84  100.25
     1.4     1.4
   96.84  100.25
Pier Skew, UpSta & Num, DnSta & Num=  ,5002.5, 2 ,5002.5, 2 , 0 , 0 , 0 ,,
     1.4     1.4
   84.61  100.83
     1.4     1.4
   84.61  100.83
Pier Skew, UpSta & Num, DnSta & Num=  ,5039.3, 2 ,5039.3, 2 , 0 , 0 , 0 ,,
     1.4     1.4
   95.65  101.39
     1.4     1.4
   95.65  101.39
Pier Skew, UpSta & Num, DnSta & Num=  ,5077.5, 2 ,5077.5, 2 , 0 , 0 , 0 ,,
     1.4     1.4
   99.18  101.97
     1.4     1.4
   99.18  101.97
BR Coef= 1 , 1 , 0 ,1.25, 0 ,,,0.8,-1,2,0,
WSPro=,,,, 1 ,,,, 0 ,,,, 0 ,,,,-1 ,-1 ,-1 , 0 , 0 , 0 , 0 , 0
BR U #Sta/Elev= 77
      96   105.4     206   103.9     366     103     566   102.7     766   103.7
     816   103.5    1026   103.6    1296   102.9  1834.8   102.1  2160.2  101.45
  2184.8   101.4  2404.8   101.4  2454.8   101.5  2504.8   102.2  2714.8   102.5
  2783.1  102.73  2834.8   102.9  3164.8   101.6  3284.8   101.3  3622.4   101.6
  3672.4   100.4  3812.4   103.1  4282.4   102.2  4402.4   102.3  4492.4   100.7
  4542.4   102.7    4796  103.81 4799.95  103.83 4829.95  103.17 4840.45  103.29
 4876.75  102.82 4944.25  103.74 4946.45  103.11 4960.36   99.09 4960.45   99.07
 4963.45    98.2 4969.35   95.16 4979.45   93.14 4994.15   87.41 5002.45   87.06
 5002.95   85.63 5005.45   85.32 5005.75    87.6 5006.45      86 5025.45   90.41
 5039.25   96.98 5041.65   98.61 5061.35   99.85 5077.45   100.2 5082.34   101.1
 5082.45  101.12 5106.45  105.55 5109.35  106.08 5133.75  105.01 5140.45  104.19
  5171.3   106.2  5216.2     106  5218.9  105.97  5566.2   102.2  5666.2   102.6
    5777   103.4    5867   102.7  6173.6   102.9  6303.6   102.1  6363.6   102.6
  6483.6     104  6683.6   102.5  6753.6   102.8  6913.6   102.8  7183.6   102.3
  7773.6     104  7983.6   103.6  8020.6  102.19  8033.6   101.7  8203.6   101.8
  8253.6   108.6    8291   110.6
BR U #Mann= 9
      96      .2  2160.2     .12  2783.1      .1    4796     .08 4944.25    .035
 5061.35     .08  5218.9     .14  8020.6      .1    8291      .2
BR U Banks=4944.25,5061.35
BR D #Sta/Elev= 77
      96   105.4     206   103.9     366     103     566   102.7     766   103.7
     816   103.5    1026   103.6    1296   102.9  1834.8   102.1  2160.2  101.45
  2184.8   101.4  2404.8   101.4  2454.8   101.5  2504.8   102.2  2714.8   102.5
  2783.1  102.73  2834.8   102.9  3164.8   101.6  3284.8   101.3  3622.4   101.6
  3672.4   100.4  3812.4   103.1  4282.4   102.2  4402.4   102.3  4492.4   100.7
  4542.4   102.7    4796  103.81 4799.95  103.83 4829.95  103.17 4840.45  103.29
 4876.75  102.82 4944.25  103.74 4946.45  103.11 4960.36   99.09 4960.45   99.07
 4963.45    98.2 4969.35   95.16 4979.45   93.14 4994.15   87.41 5002.45   87.06
 5002.95   85.63 5005.45   85.32 5005.75    87.6 5006.45      86 5025.45   90.41
 5039.25   96.98 5041.65   98.61 5061.35   99.85 5077.45   100.2 5082.34   101.1
 5082.45  101.12 5106.45  105.55 5109.35  106.08 5133.75  105.01 5140.45  104.19
  5171.3   106.2  5216.2     106  5218.9  105.97  5566.2   102.2  5666.2   102.6
    5777   103.4    5867   102.7  6173.6   102.9  6303.6   102.1  6363.6   102.6
  6483.6     104  6683.6   102.5  6753.6   102.8  6913.6   102.8  7183.6   102.3
  7773.6     104  7983.6   103.6  8020.6  102.19  8033.6   101.7  8203.6   101.8
  8253.6   108.6    8291   110.6
BR D #Mann= 9
      96      .2  2160.2     .12  2783.1      .1    4796     .08 4944.25    .035
 5061.35     .08  5218.9     .14  8020.6      .1    8291      .2
BR D Banks=4944.25,5061.35
BC Design=,, 0 ,, 0 ,,,,,,
BC HTab HWMax=110.62
BC Use User HTab Curves=0
BC User HTab FreeFlow(D)= 0

Type RM Length L Ch R = 1 ,190836.1,64.1,64.1,64.1
BEGIN DESCRIPTION:
Downstream Section of Bridge/Culvert/Weir
END DESCRIPTION:
XS GIS Cut Line= 6
      3085783.32     13912160.51       3086246.6     13910484.53
       3086130.8     13909011.56      3084744.35     13907773.66
      3083902.58     13907242.49      3083269.97     13905221.84
#Sta/Elev= 30
      96  105.47     366  103.07  2160.2  101.52  2783.1   102.8  3672.4  100.47
  3812.4  103.17  4402.4  102.37  4492.4  100.77  4542.4  102.77    4796  103.88
 4944.25  103.81 4994.15   87.48 5005.45   85.39 5005.75   87.67 5006.45   86.07
 5025.45   90.48 5041.65   98.68 5061.35   99.92 5077.45  100.27 5109.35  106.15
 5140.45  104.26  5171.3  106.27  5218.9  106.04  5566.2  102.27  7183.6  102.37
  7773.6  104.07  8020.6  102.26  8203.6  101.87  8253.6  108.67    8291  110.67
#Mann= 9 , 1 , 0
      96      .2       0  2160.2     .12       0  2783.1      .1       0
    4796     .08       0 4944.25    .035       0 5061.35     .08       0
  5218.9     .14       0  8020.6      .1       0    8291      .2       0
#XS Ineff= 2 , 0
       0  2834.8     104  7773.6       0     104
Permanent Ineff=
       F       F
Bank Sta=4944.25,5061.35
XS Rating Curve= 0 ,0
Exp/Cntr=0.5,0.3

Type RM Length L Ch R = 1 ,190772.0,65,65,65
BEGIN DESCRIPTION:
Upstream Section of Bridge/Culvert/Weir
END DESCRIPTION:
XS GIS Cut Line= 6
       3086071.6     13911426.54      3086330.58     13910451.01
      3086199.41     13909018.21      3084707.49     13907660.54
      3083929.05     13907130.66      3083374.22     13905204.46
#Sta/Elev= 30
   848.1  104.36  2173.5  101.98    2262  100.34    2282  101.73    2722  101.12
  2861.8  102.32    2952  102.99    3112  100.29  3444.1  101.95  3683.3  100.39
  4575.9  100.57 4923.41  103.67 4985.16    86.7 4999.34   85.81 5015.83    86.5
    5031   91.47 5068.22   99.47  5086.1  101.67 5089.54   103.7  5392.6  101.97
  6093.1  102.47  6213.1  101.05  6760.3  103.42  6930.3  102.05  7710.3  101.23
  7997.2  102.17  8150.3  101.05  8200.3  103.12  8230.3  107.84  8274.6  108.98
#Mann= 7 , 1 , 0
   848.1      .2       0  2173.5     .12       0  2861.8      .1       0
 4923.41    .035       0 5089.54     .14       0  7997.2      .1       0
  8274.6      .2       0
#XS Ineff= 2 , 0
       0    2952   103.5  6760.3       0   103.5
Permanent Ineff=
       F       F
Bank Sta=4923.41,5089.54
XS Rating Curve= 0 ,0
Exp/Cntr=0.5,0.3