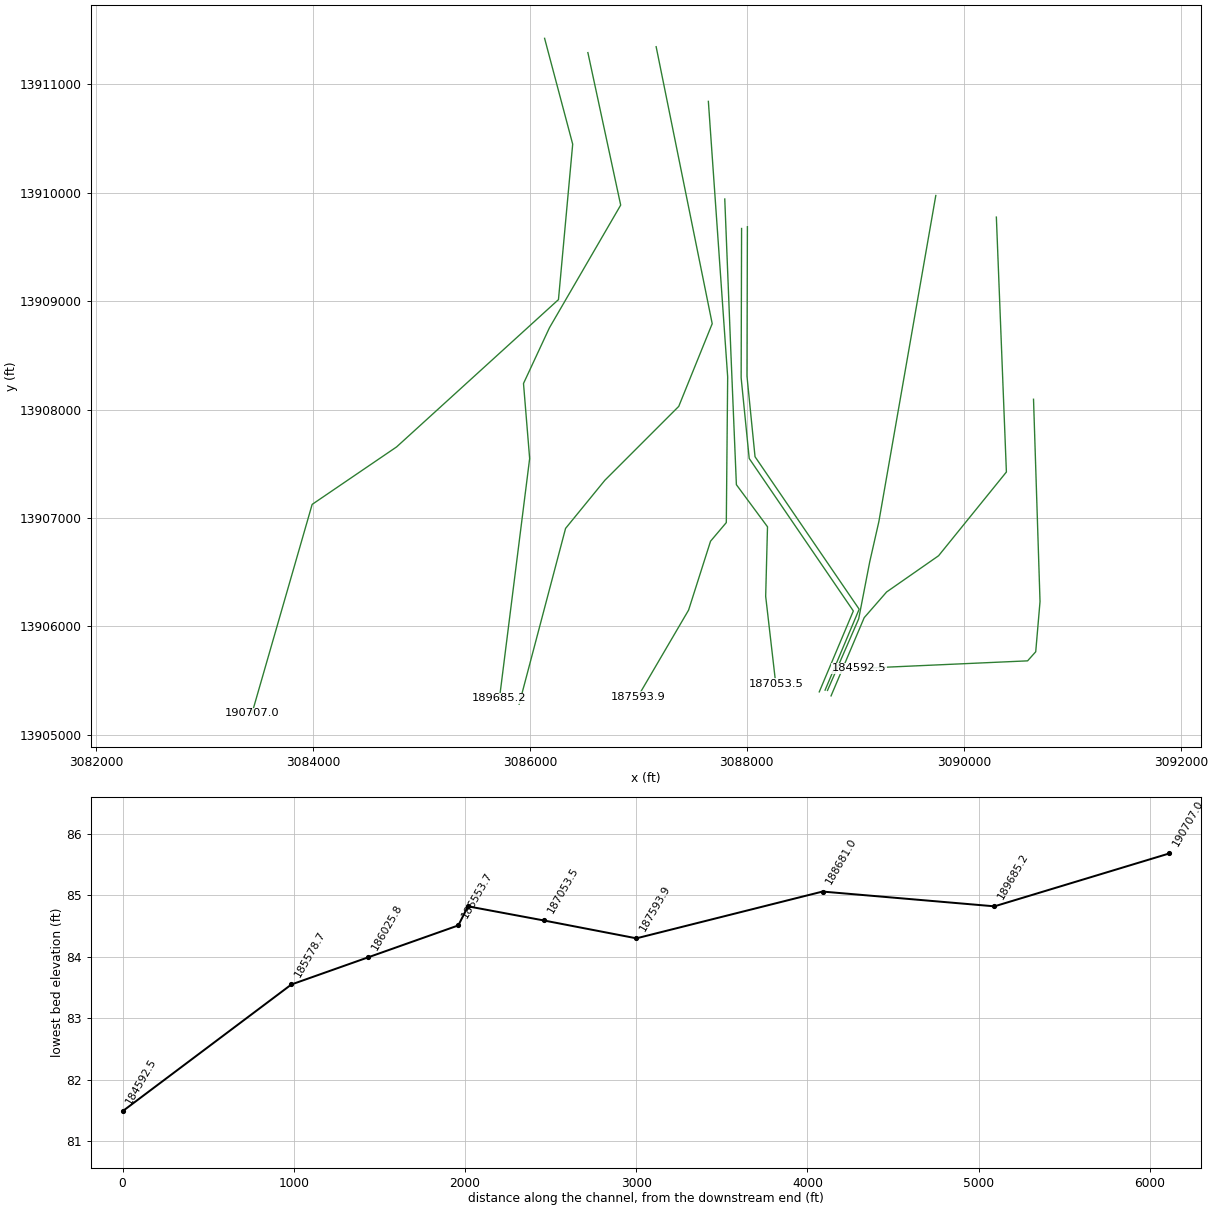
HEC-RAS study P100-00-00.prj: P100-00-00

--- P100-00-00.g01 (geometry) --- (continued)

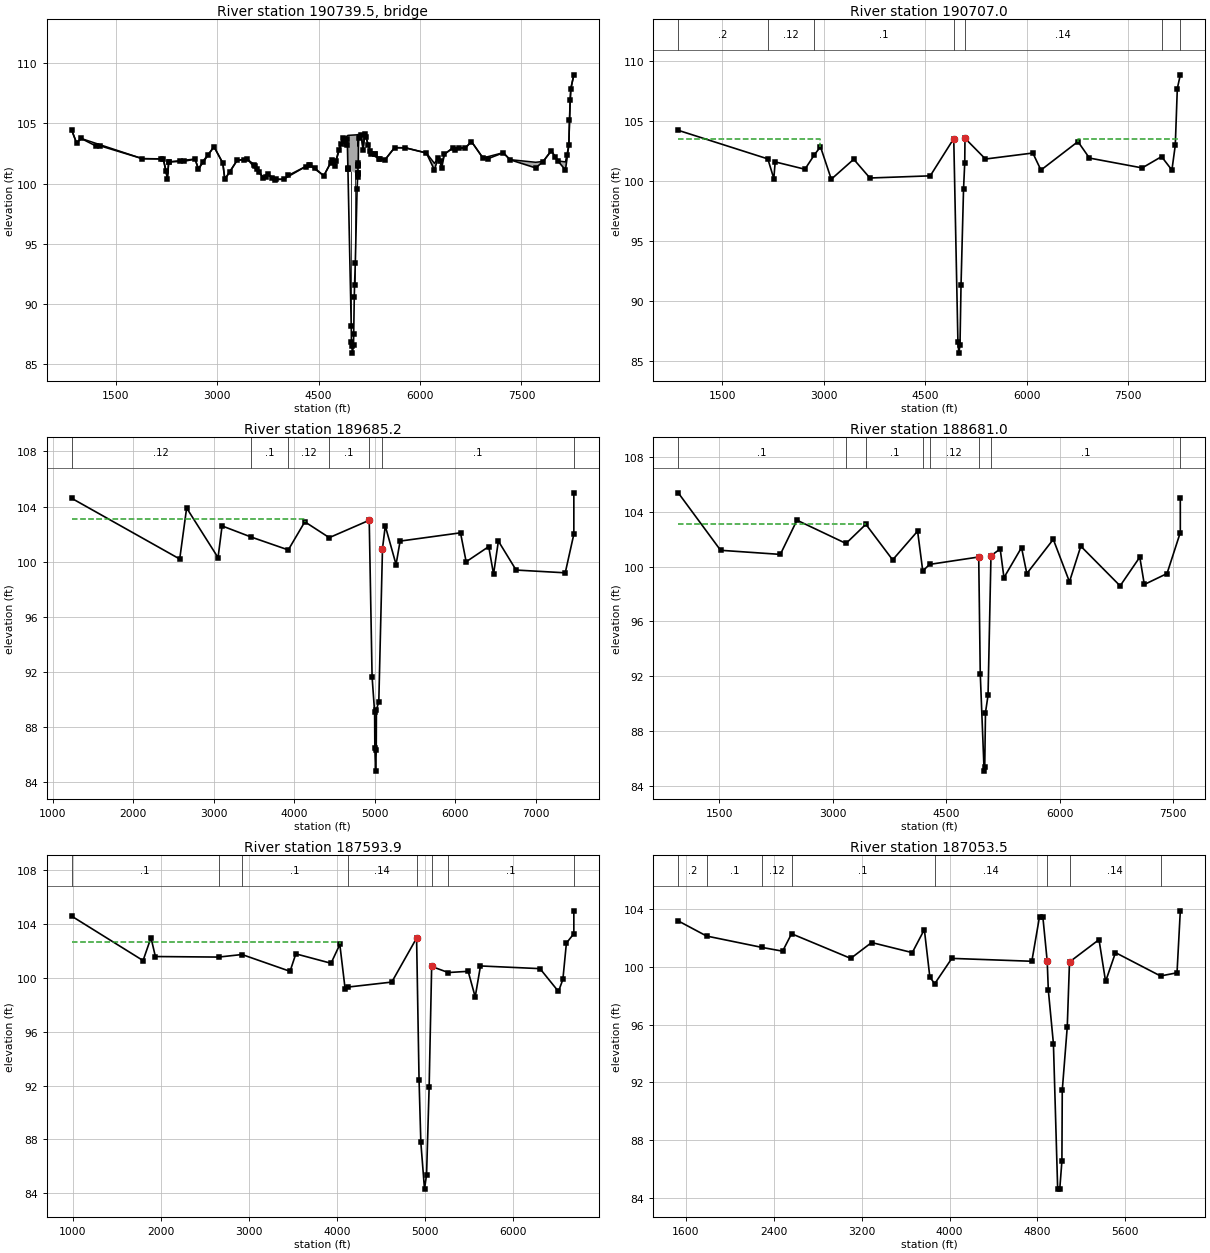
Type RM Length L Ch R = 3 ,190739.5,,,
BEGIN DESCRIPTION:
WEST GREENS ROAD - 35 degree skew
Structure ID: P00-74
END DESCRIPTION:
Bridge Culvert--1,0,-1,-1, 0
Deck Dist Width WeirC Skew NumUp NumDn MinLoCord MaxHiCord MaxSubmerge Is_Ogee
10,45,2.6,0, 60, 60, , , 0.95, 0, 1,1,,
   848.1   918.1   988.1    1892    2202    2262    2282    2672    2722    2952
    3082    3112  3294.1  3444.1  3683.3  3743.3  3853.3  3983.3  4355.9  4575.9
  4695.9  4736.7 4858.63 4881.19 4913.82 4923.41 4932.84  5076.2  5084.2 5084.31
  5086.1 5089.54 5129.89 5157.11 5182.04 5277.65  5392.6  5482.2  5622.2  5782.2
  6093.1  6213.1  6263.1  6320.3  6360.3  6490.3  6670.3  6760.3  6930.3  7230.3
  7330.3  7710.3  7820.3  7940.3  8040.3  8150.3  8200.3  8220.3  8230.3  8274.6
  104.43  103.39  103.75  102.07  102.05  100.41   101.8  102.04   101.2  103.07
  101.71  100.37  101.94  102.03  100.47  100.84  100.33  100.36  101.57  100.65
  101.93  101.51  103.77  103.55  103.93  103.97  104.01  104.06  104.09  103.09
  103.08  103.78  104.01  102.84  104.15  102.44  102.05  101.99  102.99  102.98
  102.55  101.68  102.12  101.69  102.45  102.99  102.97   103.5  102.13  102.57
  101.99  101.77  101.84  102.73  101.88   101.8  103.19  106.92  107.91  109.05
  104.43  103.39  103.75  102.07  102.05  100.41   101.8  102.03  101.19  103.06
   101.7  100.36  101.93  102.02  100.46  100.83  100.32  100.35  101.56  100.64
  101.92   101.5  103.76  103.54  103.23  103.74  101.22  100.76  101.51  101.52
  101.74  103.77     104  102.83  104.14  102.43  102.04  101.98  102.98  102.97
  102.54  101.12  102.11  101.31  102.44  102.98  102.96  103.49  102.12  102.56
  101.98   101.3  101.83  102.72  101.87  101.12  103.19  106.92  107.91  109.05
   848.1   918.1   988.1    1892    2202    2262    2282    2672    2722    2952
    3082    3112  3294.1  3444.1  3683.3  3743.3  3853.3  3983.3  4355.9  4575.9
  4695.9  4736.7 4858.63 4881.19 4913.82 4923.41 4932.84  5076.2  5084.2 5084.31
  5086.1 5089.54 5129.89 5157.11 5182.04 5277.65  5392.6  5482.2  5622.2  5782.2
  6093.1  6213.1  6263.1  6320.3  6360.3  6490.3  6670.3  6760.3  6930.3  7230.3
  7330.3  7710.3  7820.3  7940.3  8040.3  8150.3  8200.3  8220.3  8230.3  8274.6
  104.43  103.39  103.75  102.07  102.05  100.41   101.8  102.04   101.2  103.07
  101.71  100.37  101.94  102.03  100.47  100.84  100.33  100.36  101.57  100.65
  101.93  101.51  103.77  103.55  103.93  103.97  104.01  104.06  104.09  103.09
  103.08  103.78  104.01  102.84  104.15  102.44  102.05  101.99  102.99  102.98
  102.55  101.68  102.12  101.69  102.45  102.99  102.97   103.5  102.13  102.57
  101.99  101.77  101.84  102.73  101.88   101.8  103.19  106.92  107.91  109.05
  104.24   103.2  103.56  101.88  101.86  100.22  101.61  101.84     101  102.87
  101.51  100.17  101.74  101.83  100.27  100.64  100.13  100.16  101.37  100.45
  101.73  101.31  103.57  103.35  103.04  103.55  101.03  100.57  101.32  101.33
  101.55  103.58  103.81  102.64  103.95  102.24  101.85  101.79  102.79  102.78
  102.35  100.93  101.92  101.12  102.25  102.79  102.77   103.3  101.93  102.37
  101.79  101.11  101.64  102.53  101.68  100.93     103  106.73  107.72  108.86
Pier Skew, UpSta & Num, DnSta & Num=  ,4981.8, 2 ,4981.8, 2 , 0 , 0 , 0 ,,
     1.4     1.4
   86.85  101.92
     1.4     1.4
   86.66  101.73
Pier Skew, UpSta & Num, DnSta & Num=  ,5031, 2 ,5031, 2 , 0 , 0 , 0 ,,
     1.4     1.4
   90.38  101.86
     1.4     1.4
   90.19  101.67
BR Coef= 1 , 1 , 0 ,1.25, 0 ,,,0.8,0,2,0,
WSPro=,,,, 1 ,,,, 0 ,,,, 0 ,,,,-1 ,-1 ,-1 , 0 , 0 , 0 , 0 , 0
BR U #Sta/Elev= 118
   848.1  104.43   918.1  103.39   988.1  103.75  1208.1  103.12  1268.1  103.14
    1892  102.07  2173.5  102.05    2202  102.05    2242  101.06    2262  100.41
    2282   101.8  2287.4   101.8  2447.4  101.84    2502  101.85    2672  102.03
    2722  101.19    2782   101.8  2861.8  102.39    2952  103.06    3082   101.7
    3112  100.36    3182  100.93  3294.1  101.93  3396.2  101.99  3444.1  102.02
  3544.1  101.58  3564.1  101.47  3584.1  101.25  3623.3  100.97  3683.3  100.46
  3723.3  100.57  3743.3  100.83  3803.3  100.49  3853.3  100.32  3873.3  100.36
  3983.3  100.35  4053.3  100.68  4305.9  101.41  4355.9  101.56  4375.9  101.56
  4445.9  101.27  4575.9  100.64  4676.2  101.71  4695.9  101.92  4736.7   101.5
  4756.1  101.91 4799.35  102.83  4826.2  103.25 4858.63  103.76 4881.19  103.54
  4881.3  103.54 4881.41  103.54  4907.4  103.29 4913.82  103.23 4923.41  103.74
 4932.67  101.26 4932.76  101.24 4932.84  101.22  4981.8   88.13 4985.16   86.77
  4990.1   86.46 4999.34   85.88 5015.83   86.57  5018.2   87.46  5026.9   90.58
    5031   91.54 5041.98   93.37 5068.22   99.54  5076.2  100.52 5078.15  100.76
 5078.86  100.85 5078.97  100.86 5084.09  101.49  5084.2  101.51 5084.31  101.52
  5086.1  101.74 5089.54  103.77 5129.89     104 5157.11  102.83 5182.04  104.14
  5199.4  103.84 5233.29  103.24  5261.8  102.72 5277.65  102.43  5330.9  102.46
 5330.95  102.46  5392.6  102.04    5409  102.03  5482.2  101.98  5622.2  102.98
  5782.2  102.97  6093.1  102.54  6213.1  101.12  6263.1  102.11  6290.3  101.89
  6320.3  101.31  6360.3  102.44  6490.3  102.98  6520.3  102.83  6580.3  102.93
  6670.3  102.96  6760.3  103.49  6930.3  102.12  7000.3  102.06  7230.3  102.56
  7330.3  101.98  7710.3   101.3  7820.3  101.83  7940.3  102.72  7997.2  102.24
  8040.3  101.87  8150.3  101.12  8180.1  102.35  8200.3  103.19  8210.3   105.3
  8220.3  106.92  8230.3  107.91  8274.6  109.05
BR U #Mann= 7
   848.1      .2  2173.5     .12  2861.8      .1 4923.41    .035 5089.54     .14
  7997.2      .1  8274.6      .2
BR U Banks=4923.41,5089.54
BR D #Sta/Elev= 118
   848.1  104.24   918.1   103.2   988.1  103.56  1208.1  102.93  1268.1  102.95
    1892  101.88  2173.5  101.86    2202  101.86    2242  100.87    2262  100.22
    2282  101.61  2287.4  101.61  2447.4  101.65    2502  101.66    2672  101.84
    2722     101    2782  101.61  2861.8   102.2    2952  102.87    3082  101.51
    3112  100.17    3182  100.74  3294.1  101.74  3396.2   101.8  3444.1  101.83
  3544.1  101.39  3564.1  101.28  3584.1  101.06  3623.3  100.78  3683.3  100.27
  3723.3  100.38  3743.3  100.64  3803.3   100.3  3853.3  100.13  3873.3  100.17
  3983.3  100.16  4053.3  100.49  4305.9  101.22  4355.9  101.37  4375.9  101.37
  4445.9  101.08  4575.9  100.45  4676.2  101.52  4695.9  101.73  4736.7  101.31
  4756.1  101.72 4799.35  102.64  4826.2  103.06 4858.63  103.57 4881.19  103.35
  4881.3  103.35 4881.41  103.35  4907.4   103.1 4913.82  103.04 4923.41  103.55
 4932.67  101.07 4932.76  101.05 4932.84  101.03  4981.8   87.94 4985.16   86.58
  4990.1   86.27 4999.34   85.69 5015.83   86.38  5018.2   87.27  5026.9   90.39
    5031   91.35 5041.98   93.18 5068.22   99.35  5076.2  100.33 5078.15  100.57
 5078.86  100.66 5078.97  100.67 5084.09   101.3  5084.2  101.32 5084.31  101.33
  5086.1  101.55 5089.54  103.58 5129.89  103.81 5157.11  102.64 5182.04  103.95
  5199.4  103.65 5233.29  103.05  5261.8  102.53 5277.65  102.24  5330.9  102.27
 5330.95  102.27  5392.6  101.85    5409  101.84  5482.2  101.79  5622.2  102.79
  5782.2  102.78  6093.1  102.35  6213.1  100.93  6263.1  101.92  6290.3   101.7
  6320.3  101.12  6360.3  102.25  6490.3  102.79  6520.3  102.64  6580.3  102.74
  6670.3  102.77  6760.3   103.3  6930.3  101.93  7000.3  101.87  7230.3  102.37
  7330.3  101.79  7710.3  101.11  7820.3  101.64  7940.3  102.53  7997.2  102.05
  8040.3  101.68  8150.3  100.93  8180.1  102.16  8200.3     103  8210.3  105.11
  8220.3  106.73  8230.3  107.72  8274.6  108.86
BR D #Mann= 7
   848.1      .2  2173.5     .12  2861.8      .1 4923.41    .035 5089.54     .14
  7997.2      .1  8274.6      .2
BR D Banks=4923.41,5089.54
BC Design=,, 0 ,, 0 ,,,,,,
BC HTab HWMax=108.98
BC Use User HTab Curves=0
BC User HTab FreeFlow(D)= 0

Type RM Length L Ch R = 1 ,190707.0,1021.8,1021.8,1021.8
BEGIN DESCRIPTION:
Downstream Section of Bridge/Culvert/Weir
END DESCRIPTION:
XS GIS Cut Line= 6
      3086136.38     13911421.23      3086395.36     13910445.69
      3086264.19     13909012.89      3084772.27     13907655.22
      3083993.83     13907125.34        3083439.     13905199.15
#Sta/Elev= 30
   848.1  104.23  2173.5  101.85    2262  100.21    2282   101.6    2722  100.99
  2861.8  102.19    2952  102.86    3112  100.16  3444.1  101.82  3683.3  100.26
  4575.9  100.44 4923.41  103.54 4985.16   86.57 4999.34   85.68 5015.83   86.37
    5031   91.34 5068.22   99.34  5086.1  101.54 5089.54  103.57  5392.6  101.84
  6093.1  102.34  6213.1  100.92  6760.3  103.29  6930.3  101.92  7710.3   101.1
  7997.2  102.04  8150.3  100.92  8200.3  102.99  8230.3  107.71  8274.6  108.85
#Mann= 7 , 1 , 0
   848.1      .2       0  2173.5     .12       0  2861.8      .1       0
 4923.41    .035       0 5089.54     .14       0  7997.2      .1       0
  8274.6      .2       0
#XS Ineff= 2 , 0
       0    2952   103.5  6760.3       0   103.5
Permanent Ineff=
       F       F
Bank Sta=4923.41,5089.54
XS Rating Curve= 0 ,0
Exp/Cntr=0.5,0.3

Type RM Length L Ch R = 1 ,189685.2,1438,1004.2,407.2
BEGIN DESCRIPTION:
Cross Section 189685.2
END DESCRIPTION:
XS GIS Cut Line= 6
      3086535.44     13911289.54      3086837.73     13909884.02
      3086180.55     13908752.32      3085941.95     13908239.85
      3085998.64     13907548.17      3085720.63     13905338.96
#Sta/Elev= 30
  1239.2   104.6  2579.2   100.2    2665   103.9    3055   100.3    3105   102.6
  3463.2   101.8  3926.8  100.86  4132.2   102.9  4435.6  101.75  4931.6  103.01
  4967.1   91.66  4998.5    89.1  5001.5   86.51  5010.5   84.82  5018.7   86.37
  5020.8   89.27  5050.4   89.86  5096.3  100.96  5130.8   102.6  5264.8    99.8
  5314.8   101.5  6064.8   102.1  6134.8     100  6414.8   101.1  6474.8    99.1
  6534.8   101.5  6754.8    99.4  7364.8    99.2  7471.5     102  7471.6     105
#Mann= 7 , 1 , 0
  1239.2     .12       0  3463.2      .1       0  3926.8     .12       0
  4435.6      .1       0  4931.6    .035       0  5096.3      .1       0
  7471.5      .2       0
#XS Ineff= 2 , 0
       0  4132.2   103.1  6064.8       0   102.1
Permanent Ineff=
       F       F
Bank Sta=4931.6,5096.3
XS Rating Curve= 0 ,0
Exp/Cntr=0.3,0.1

Type RM Length L Ch R = 1 ,188681.0,376.7,1087.1,1318.2
BEGIN DESCRIPTION:
Cross Section 188681.0
END DESCRIPTION:
XS GIS Cut Line= 6
      3087164.54     13911344.19      3087681.36     13908790.93
      3087372.94     13908028.95      3086692.59      13907348.6
      3086329.74     13906904.11      3085901.89     13905283.91
#Sta/Elev= 30
   955.2   105.4  1515.2   101.2  2305.2   100.9  2525.2   103.4  3173.4   101.7
  3436.3   103.1  3790.3   100.5  4120.3   102.6  4188.5   99.69  4279.2  100.17
  4928.4  100.71  4948.8   92.19  4999.9   85.06    5008   85.35  5017.9   89.34
  5051.7    90.6  5090.5   100.8  5212.3   101.3  5262.3    99.2  5494.5   101.4
  5564.5    99.5  5914.5     102  6128.3    98.9  6278.3   101.5  6798.3    98.6
  7058.3   100.7  7118.3    98.7  7418.3    99.5    7594   102.5  7594.1     105
#Mann= 8 , 1 , 0
   955.2      .1       0  3173.4     .12       0  3436.3      .1       0
  4188.5     .14       0  4279.2     .12       0  4928.4    .035       0
  5090.5      .1       0    7594      .2       0
#XS Ineff= 2 , 0
       0  3435.2   103.1  5914.5       0     102
Permanent Ineff=
       F       F
Bank Sta=4928.4,5090.5
XS Rating Curve= 0 ,0
Exp/Cntr=0.3,0.1

Type RM Length L Ch R = 1 ,187593.9,57.5,540.4,696.3
BEGIN DESCRIPTION:
Cross Section 187593.9
END DESCRIPTION:
XS GIS Cut Line= 6
       3087645.9     13910840.07      3087823.88     13908300.68
      3087811.27     13906957.73      3087665.96       13906786.
      3087463.65     13906151.19      3086996.58     13905353.41
#Sta/Elev= 30
     990   104.6    1800   101.3    1890     103    1940   101.6  2658.4  101.56
  2924.2  101.75    3470   100.5  3535.6   101.8  3935.6   101.1  4035.6   102.5
  4095.6    99.2  4129.3   99.33  4625.6    99.7  4907.7  102.97  4935.8    92.4
    4956   87.77  4997.7    84.3    5021   85.38  5050.2   91.88  5078.9  100.86
  5267.6  100.41  5493.6   100.5  5573.6    98.6  5633.6   100.9  6309.8   100.7
  6519.8      99  6569.8    99.9  6609.8   102.6  6694.3   103.3  6694.4     105
#Mann= 8 , 1 , 0
     990      .1       0  2658.4     .12       0  2924.2      .1       0
  4129.3     .14       0  4907.7    .035       0  5078.9     .14       0
  5267.6      .1       0  6694.3      .2       0
#XS Ineff= 2 , 0
       0  4035.6   102.7               0
Permanent Ineff=
       F       F
Bank Sta=4907.7,5078.9
XS Rating Curve= 0 ,0
Exp/Cntr=0.3,0.1

Type RM Length L Ch R = 1 ,187053.5,67.9,443.8,660.7
BEGIN DESCRIPTION:
Cross Section 187053.5-Interpolated
END DESCRIPTION:
XS GIS Cut Line= 6
      3087797.07     13909940.39      3087853.61     13908521.62
      3087904.22     13907306.96      3088191.02     13906918.94
      3088174.15     13906277.87      3088266.99     13905473.22
#Sta/Elev= 30
  1530.7   103.2    1789  102.15  2293.6  101.36  2480.7   101.1  2562.2  102.31
  3100.6   100.6  3290.6   101.7  3660.6     101  3770.6   102.6  3820.6    99.3
  3864.8   98.84  4020.6   100.6  4748.8   100.4  4818.8   103.5  4848.8   103.5
  4888.8   100.4  4898.8    98.4  4945.3   94.68  4983.9    84.6  5002.9   84.59
  5022.5   86.54  5025.7   91.44  5071.2   95.85  5091.6  100.35  5360.1   101.9
  5420.1      99  5510.1     101  5919.9   99.38  6070.1    99.6  6100.1   103.9
#Mann= 8 , 1 , 0
  1530.7      .2       0    1789      .1       0  2293.6     .12       0
  2562.2      .1       0  3864.8     .14       0  4888.8     .04       0
  5091.6     .14       0  5919.9      .1       0
#XS Ineff= 2 , 0
       0  3770.6   102.6  5360.1       0   101.9
Permanent Ineff=
       F       F
Bank Sta=4888.8,5091.6
XS Rating Curve= 0 ,0
Exp/Cntr=0.5,0.3

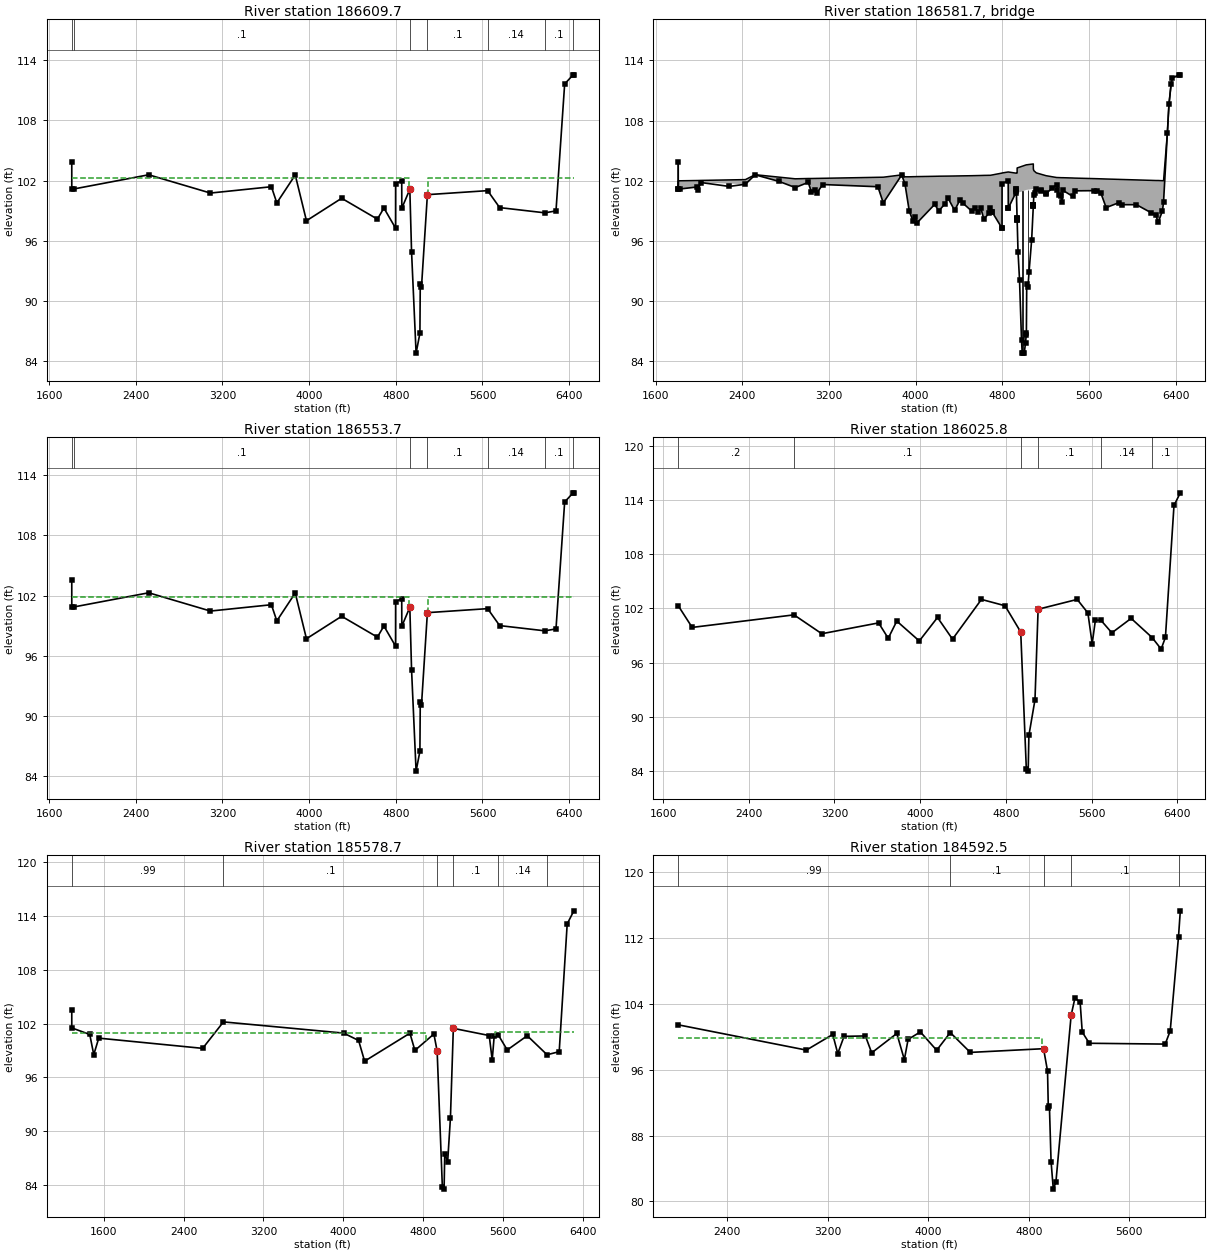
Type RM Length L Ch R = 1 ,186609.7,56,56,56
BEGIN DESCRIPTION:
Upstream Section of Bridge/Culvert/Weir
END DESCRIPTION:
XS GIS Cut Line= 5
      3087952.06     13909668.53       3087948.1     13908292.13
      3088022.45     13907548.58      3088982.16     13906143.27
      3088668.15     13905397.28
#Sta/Elev= 30
  1808.7  103.85  1808.8  101.16    1829  101.18  2518.8  102.59  3088.8  100.77
  3651.6   101.4  3701.6   99.79  3871.6  102.57  3975.2   98.01  4300.1  100.25
  4630.1   98.17  4690.1   99.28  4797.8   97.27  4798.2  101.69  4854.6  102.01
  4855.5   99.26  4929.4  101.14  4945.3   94.94  4987.2   84.82  5022.5    86.8
  5025.7    91.7  5037.1   91.42  5091.6  100.61  5647.5  101.01  5758.7   99.32
  6175.6    98.8  6278.7   98.99  6358.7  111.64  6433.7  112.51  6443.5  112.55
#Mann= 7 , 1 , 0
  1808.7      .2       0    1829      .1       0  4929.4    .035       0
  5091.6      .1       0  5647.5     .14       0  6175.6      .1       0
  6433.7      .2       0
#XS Ineff= 2 , 0
       0    4926   102.3    5097       0   102.3
Permanent Ineff=
       F       F
Bank Sta=4929.4,5091.6
XS Rating Curve= 0 ,0
Exp/Cntr=0.5,0.3

Type RM Length L Ch R = 3 ,186581.7,,,
BEGIN DESCRIPTION:
VETERANS MEMORIAL DRIVE
Structure ID: P00-73
END DESCRIPTION:
Bridge Culvert--1,0,-1,-1, 0
Deck Dist Width WeirC Skew NumUp NumDn MinLoCord MaxHiCord MaxSubmerge Is_Ogee
10,36,2.6,0, 60, 60, , , 0.95, 0, 1,1,,
  1808.7  1808.8    1811  1988.8  2018.8  2428.8  2518.8  2888.8  3008.8  3038.8
  3088.8  3141.6  3651.6  3701.6  3871.6  3901.6  3941.6  3975.2  4015.2  4175.2
  4215.2  4300.1  4360.1  4410.1  4520.1  4600.1  4630.1  4690.1  4797.8  4798.2
  4854.6  4855.5  4929.4 4936.99  4937.1  4937.2  5021.1  5086.6 5086.89    5087
  5091.6  5114.2  5204.1  5301.1  5349.7  5359.7  5449.7  5469.7  5678.7  5758.7
  6038.7  6218.7  6238.7  6278.7  6288.7  6324.1  6338.7  6358.7  6368.7  6443.5
  103.86  101.17     102  102.03  102.04  102.12  102.61   102.2  102.23  102.23
  102.24  102.25  102.35  102.36  102.59   102.4   102.4  102.41  102.42  102.45
  102.46  102.47  102.48  102.49  102.51  102.53  102.54  102.55  102.77  102.78
  102.88  102.88  102.76  102.78  102.78  103.28  103.59  103.68  103.18  103.18
  103.01  102.79  102.51  102.33  102.31  102.31  102.28  102.27  102.21  102.18
  102.09  102.03  102.03  102.01  102.01  106.79  109.62  111.65  112.27  112.56
  103.86  101.17  101.17  101.07  101.83  101.66   102.6  101.33  101.84  100.86
  100.78  101.63  101.41    99.8  102.58   101.7   98.97   98.02   97.83   99.64
   99.01  100.26   99.05  100.11   98.96   99.34   98.18   99.29   97.28   101.7
  102.02   99.27  101.15   98.19  100.78  100.78  101.09  101.18  101.18   99.61
  100.62  101.16  100.73  101.63    99.9  101.05  100.45     101  101.02   99.33
   99.62   98.55   97.85      99   99.89  106.78  109.62  111.65  112.27  112.56
  1808.7  1808.8    1811  1988.8  2018.8  2428.8  2518.8  2888.8  3008.8  3038.8
  3088.8  3141.6  3651.6  3701.6  3871.6  3901.6  3941.6  3975.2  4015.2  4175.2
  4215.2  4300.1  4360.1  4410.1  4520.1  4600.1  4630.1  4690.1  4797.8  4798.2
  4854.6  4855.5  4929.4 4936.99  4937.1  4937.2  5021.1  5086.6 5086.89    5087
  5091.6  5114.2  5204.1  5301.1  5349.7  5359.7  5449.7  5469.7  5678.7  5758.7
  6038.7  6218.7  6238.7  6278.7  6288.7  6324.1  6338.7  6358.7  6368.7  6443.5
  103.86  101.17     102  102.03  102.04  102.12  102.61   102.2  102.23  102.23
  102.24  102.25  102.35  102.36  102.59   102.4   102.4  102.41  102.42  102.45
  102.46  102.47  102.48  102.49  102.51  102.53  102.54  102.55  102.77  102.78
  102.88  102.88  102.76  102.78  102.78  103.28  103.59  103.68  103.18  103.18
  103.01  102.79  102.51  102.33  102.31  102.31  102.28  102.27  102.21  102.18
  102.09  102.03  102.03  102.01  102.01  106.79  109.62  111.65  112.27  112.56
  103.55  100.86  100.86  100.76  101.52  101.35  102.29  101.02  101.53  100.55
  100.47  101.32   101.1   99.49  102.27  101.39   98.66   97.71   97.52   99.33
    98.7   99.95   98.74    99.8   98.65   99.03   97.87   98.98   96.97  101.39
  101.71   98.96  100.84   97.88  100.47  100.47  100.78  100.87  100.87    99.3
  100.31  100.85  100.42  101.32   99.59  100.74  100.14  100.69  100.71   99.02
   99.31   98.24   97.54   98.69   99.58  106.47  109.31  111.34  111.96  112.25
Pier Skew, UpSta & Num, DnSta & Num=  ,4987.2, 2 ,4987.2, 2 , 0 , 0 , 0 ,,
     1.4     1.4
   83.83  101.96
     1.4     1.4
   83.52  101.65
Pier Skew, UpSta & Num, DnSta & Num=  ,5037.1, 2 ,5037.1, 2 , 0 , 0 , 0 ,,
     1.4     1.4
   90.45  102.11
     1.4     1.4
   90.14   101.8
BR Coef= 1 , 1 , 0 ,1.25, 0 ,,,0.8,0,2,0,
WSPro=,,,, 1 ,,,, 0 ,,,, 0 ,,,,-1 ,-1 ,-1 , 0 , 0 , 0 , 0 , 0
BR U #Sta/Elev= 112
  1808.7  103.86  1808.8  101.17    1811  101.17    1829  101.19  1978.8  101.38
  1988.8  101.07  2018.8  101.83  2278.8  101.44  2428.8  101.66  2518.8   102.6
  2738.8  101.94  2888.8  101.33  3008.8  101.84  3038.8  100.86  3068.8  101.09
  3088.8  100.78  3141.6  101.63  3651.6  101.41  3701.6    99.8  3871.6  102.58
  3901.6   101.7  3941.6   98.97  3975.2   98.02  3995.2   98.37  4015.2   97.83
  4175.2   99.64  4215.2   99.01  4270.1    99.7  4300.1  100.26  4360.1   99.05
  4410.1  100.11  4440.1   99.74  4520.1   98.96  4550.1    99.3  4580.1   98.86
  4600.1   99.34  4630.1   98.18  4680.1   98.81  4690.1   99.29  4704.7   98.92
  4705.1   98.91  4795.3   97.32  4797.8   97.28  4798.2   101.7  4854.6  102.02
  4855.5   99.27  4856.5   99.29  4924.5   100.8  4926.7  100.96  4929.3  101.14
  4929.4  101.15  4936.7    98.3 4936.81   98.26  4936.9   98.23 4936.99   98.19
  4937.1   98.15  4937.2   98.11 4937.31   98.07  4945.3   94.95  4959.2   92.14
  4977.6   86.13  4983.9   84.87  4987.2   84.83  5002.9   84.86  5014.6   85.84
  5021.1   86.64  5022.5   86.81  5025.7   91.71  5037.1   91.43  5046.9   92.89
  5071.2   96.12 5086.49   99.49  5086.6   99.52 5086.71   99.54  5086.8   99.56
 5086.89   99.58    5087   99.61  5087.1   99.63  5091.6  100.62  5097.7  100.77
  5114.2  101.16  5153.4  101.04  5160.3  101.02  5204.1  100.73  5206.1  100.75
  5261.1  101.26  5301.1  101.63  5309.7  101.11  5319.7   100.6  5339.7  100.51
  5349.7    99.9  5359.7  101.05  5449.7  100.45  5469.7     101  5647.5  101.02
  5678.7  101.02  5708.7  100.82  5758.7   99.33  5878.7   99.83  5908.7   99.62
  6038.7   99.62  6175.6   98.81  6218.7   98.55  6238.7   97.85  6278.7      99
  6288.7   99.89  6324.1  106.78  6338.7  109.62  6358.7  111.65  6368.7  112.27
  6433.7  112.52  6443.5  112.56
BR U #Mann= 7
  1808.7      .2    1829      .1  4929.4    .035  5091.6      .1  5647.5     .14
  6175.6      .1  6433.7      .2
BR U Banks=4929.4,5091.6
BR D #Sta/Elev= 112
  1808.7  103.55  1808.8  100.86    1811  100.86    1829  100.88  1978.8  101.07
  1988.8  100.76  2018.8  101.52  2278.8  101.13  2428.8  101.35  2518.8  102.29
  2738.8  101.63  2888.8  101.02  3008.8  101.53  3038.8  100.55  3068.8  100.78
  3088.8  100.47  3141.6  101.32  3651.6   101.1  3701.6   99.49  3871.6  102.27
  3901.6  101.39  3941.6   98.66  3975.2   97.71  3995.2   98.06  4015.2   97.52
  4175.2   99.33  4215.2    98.7  4270.1   99.39  4300.1   99.95  4360.1   98.74
  4410.1    99.8  4440.1   99.43  4520.1   98.65  4550.1   98.99  4580.1   98.55
  4600.1   99.03  4630.1   97.87  4680.1    98.5  4690.1   98.98  4704.7   98.61
  4705.1    98.6  4795.3   97.01  4797.8   96.97  4798.2  101.39  4854.6  101.71
  4855.5   98.96  4856.5   98.98  4924.5  100.49  4926.7  100.65  4929.3  100.83
  4929.4  100.84  4936.7   97.99 4936.81   97.95  4936.9   97.92 4936.99   97.88
  4937.1   97.84  4937.2    97.8 4937.31   97.76  4945.3   94.64  4959.2   91.83
  4977.6   85.82  4983.9   84.56  4987.2   84.52  5002.9   84.55  5014.6   85.53
  5021.1   86.33  5022.5    86.5  5025.7    91.4  5037.1   91.12  5046.9   92.58
  5071.2   95.81 5086.49   99.18  5086.6   99.21 5086.71   99.23  5086.8   99.25
 5086.89   99.27    5087    99.3  5087.1   99.32  5091.6  100.31  5097.7  100.46
  5114.2  100.85  5153.4  100.73  5160.3  100.71  5204.1  100.42  5206.1  100.44
  5261.1  100.95  5301.1  101.32  5309.7   100.8  5319.7  100.29  5339.7   100.2
  5349.7   99.59  5359.7  100.74  5449.7  100.14  5469.7  100.69  5647.5  100.71
  5678.7  100.71  5708.7  100.51  5758.7   99.02  5878.7   99.52  5908.7   99.31
  6038.7   99.31  6175.6    98.5  6218.7   98.24  6238.7   97.54  6278.7   98.69
  6288.7   99.58  6324.1  106.47  6338.7  109.31  6358.7  111.34  6368.7  111.96
  6433.7  112.21  6443.5  112.25
BR D #Mann= 7
  1808.7      .2    1829      .1  4929.4    .035  5091.6      .1  5647.5     .14
  6175.6      .1  6433.7      .2
BR D Banks=4929.4,5091.6
BC Design=,, 0 ,, 0 ,,,,,,
BC HTab HWMax=112.55
BC Use User HTab Curves=0
BC User HTab FreeFlow(D)= 0

Type RM Length L Ch R = 1 ,186553.7,527.9,527.9,527.9
BEGIN DESCRIPTION:
Downstream Section of Bridge/Culvert/Weir
END DESCRIPTION:
XS GIS Cut Line= 5
       3088005.7     13909684.63      3088001.74     13908308.23
      3088076.09     13907564.68       3089035.8     13906159.37
      3088721.78     13905413.38
#Sta/Elev= 30
  1808.7  103.54  1808.8  100.85    1829  100.87  2518.8  102.28  3088.8  100.46
  3651.6  101.09  3701.6   99.48  3871.6  102.26  3975.2    97.7  4300.1   99.94
  4630.1   97.86  4690.1   98.97  4797.8   96.96  4798.2  101.38  4854.6   101.7
  4855.5   98.95  4929.4  100.83  4945.3   94.63  4987.2   84.51  5022.5   86.49
  5025.7   91.39  5037.1   91.11  5091.6   100.3  5647.5   100.7  5758.7   99.01
  6175.6   98.49  6278.7   98.68  6358.7  111.33  6433.7   112.2  6443.5  112.24
#Mann= 7 , 1 , 0
  1808.7      .2       0    1829      .1       0  4929.4    .035       0
  5091.6      .1       0  5647.5     .14       0  6175.6      .1       0
  6433.7      .2       0
#XS Ineff= 2 , 0
       0    4926   101.9    5097       0   101.9
Permanent Ineff=
       F       F
Bank Sta=4929.4,5091.6
XS Rating Curve= 0 ,0
Exp/Cntr=0.5,0.3

Type RM Length L Ch R = 1 ,186025.8,1147,447.1,158.4
BEGIN DESCRIPTION:
Cross Section 186025.8-Interpolated
END DESCRIPTION:
XS GIS Cut Line= 5
      3089742.27     13909972.52      3089217.26     13906965.63
      3089132.76     13906593.84      3089031.36     13906069.95
      3088744.07     13905410.87
#Sta/Elev= 30
  1741.9   102.3  1871.9    99.9  2822.3  101.29  3081.9    99.2  3611.9   100.4
  3701.9    98.7  3781.9   100.6  3991.9    98.4  4161.9     101  4301.9    98.6
  4571.9     103  4791.9   102.3  4938.6   99.39    4991   84.19  5008.2   83.99
  5014.8   87.94  5071.6   91.89  5100.8  101.91  5465.5     103  5565.5   101.5
  5605.5    98.1  5635.5   100.7  5686.6   100.7  5789.1    99.3  5969.1   100.9
  6164.8   98.78  6249.1    97.5  6289.1    98.8  6369.1   113.4  6428.1   114.8
#Mann= 6 , 1 , 0
  1741.9      .2       0  2822.3      .1       0  4938.6     .04       0
  5100.8      .1       0  5686.6     .14       0  6164.8      .1       0
#XS Ineff= 2 , 0
       0  4791.9   102.3  5635.5       0   100.7
Permanent Ineff=
       F       F
Bank Sta=4938.6,5100.8
XS Rating Curve= 0 ,0
Exp/Cntr=0.3,0.1

Type RM Length L Ch R = 1 ,185578.7,1291.7,986.2,619.6
BEGIN DESCRIPTION:
Cross Section 185578.7
END DESCRIPTION:
XS GIS Cut Line= 6
      3090300.46     13909773.52      3090392.93     13907423.96
      3089767.75     13906651.93      3089288.79      13906318.1
      3089082.19     13906081.13      3088776.75     13905360.38
#Sta/Elev= 30
  1281.3  103.52  1281.4  101.52  1461.4  100.79  1501.4   98.54  1551.4  100.38
  2591.4   99.24  2799.4  102.19  4002.6  100.94  4152.6  100.12  4212.6   97.81
  4666.1  100.93  4716.1   99.01  4906.1  100.84  4938.6   98.95    4991   83.75
  5008.2   83.55  5014.8    87.5  5043.9   86.62  5071.6   91.45  5100.8  101.47
  5459.9  100.67  5489.9   97.94  5509.9  100.63  5551.7  100.72  5640.5   99.06
  5840.5  100.65    6039   98.53  6160.5   98.87  6240.5  113.11  6307.1  114.57
#Mann= 6 , 1 , 0
  1281.3     .99       0  2799.4      .1       0  4938.6    .035       0
  5100.8      .1       0  5551.7     .14       0    6039      .1       0
#XS Ineff= 2 , 0
       0  4826.1  100.94  5520.5       0  101.04
Permanent Ineff=
       F       F
Bank Sta=4938.6,5100.8
XS Rating Curve= 0 ,0
Exp/Cntr=0.5,0.3

Type RM Length L Ch R = 1 ,184592.5,70,70,70
BEGIN DESCRIPTION:
Upstream Section of Bridge/Culvert/Weir
END DESCRIPTION:
XS GIS Cut Line= 5
      3090642.99     13908094.41      3090702.94     13906229.76
      3090663.29     13905767.09      3090588.18     13905683.27
      3089035.37      13905613.6
#Sta/Elev= 30
  2008.9  101.45  3028.9   98.38  3238.9  100.28  3278.9   97.96  3328.9  100.05
  3498.9   100.1  3548.9   98.05  3748.9   100.4  3808.9   97.22  3838.9   99.68
  3936.2  100.59  4066.2   98.36  4174.5  100.51    4334    98.1 4917.15   98.55
  4948.8   95.83 4954.96    91.3 4963.73   91.55 4976.98   84.83 4994.69   81.49
 5015.32   82.33 5136.68  102.61 5167.32  104.73 5208.44  104.17 5225.07  100.57
 5281.51   99.21  5885.4   99.11  5925.4  100.71  5991.5  112.18  6005.8   115.3
#Mann= 5 , 1 , 0
  2008.9     .99       0  4174.5      .1       0 4917.15    .035       0
 5136.68      .1       0  5991.5      .2       0
#XS Ineff= 2 , 0
       0    4903    99.9    5131       0    99.6
Permanent Ineff=
       F       F
Bank Sta=4917.15,5136.68
XS Rating Curve= 0 ,0
Exp/Cntr=0.5,0.3