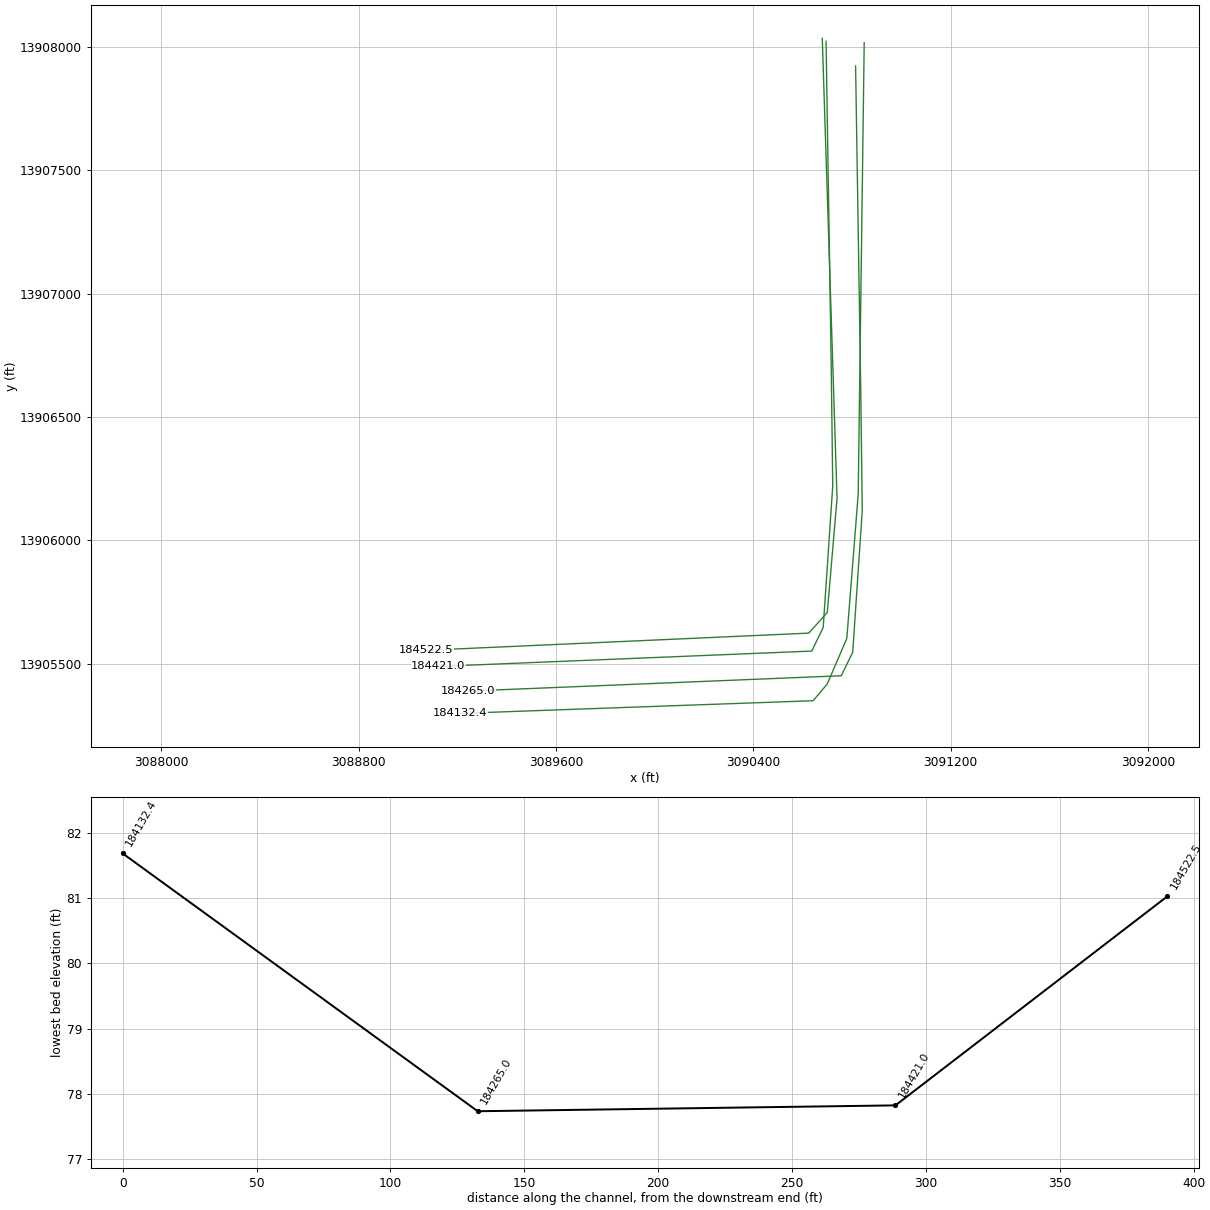
HEC-RAS study P100-00-00.prj: P100-00-00

--- P100-00-00.g01 (geometry) --- (continued)

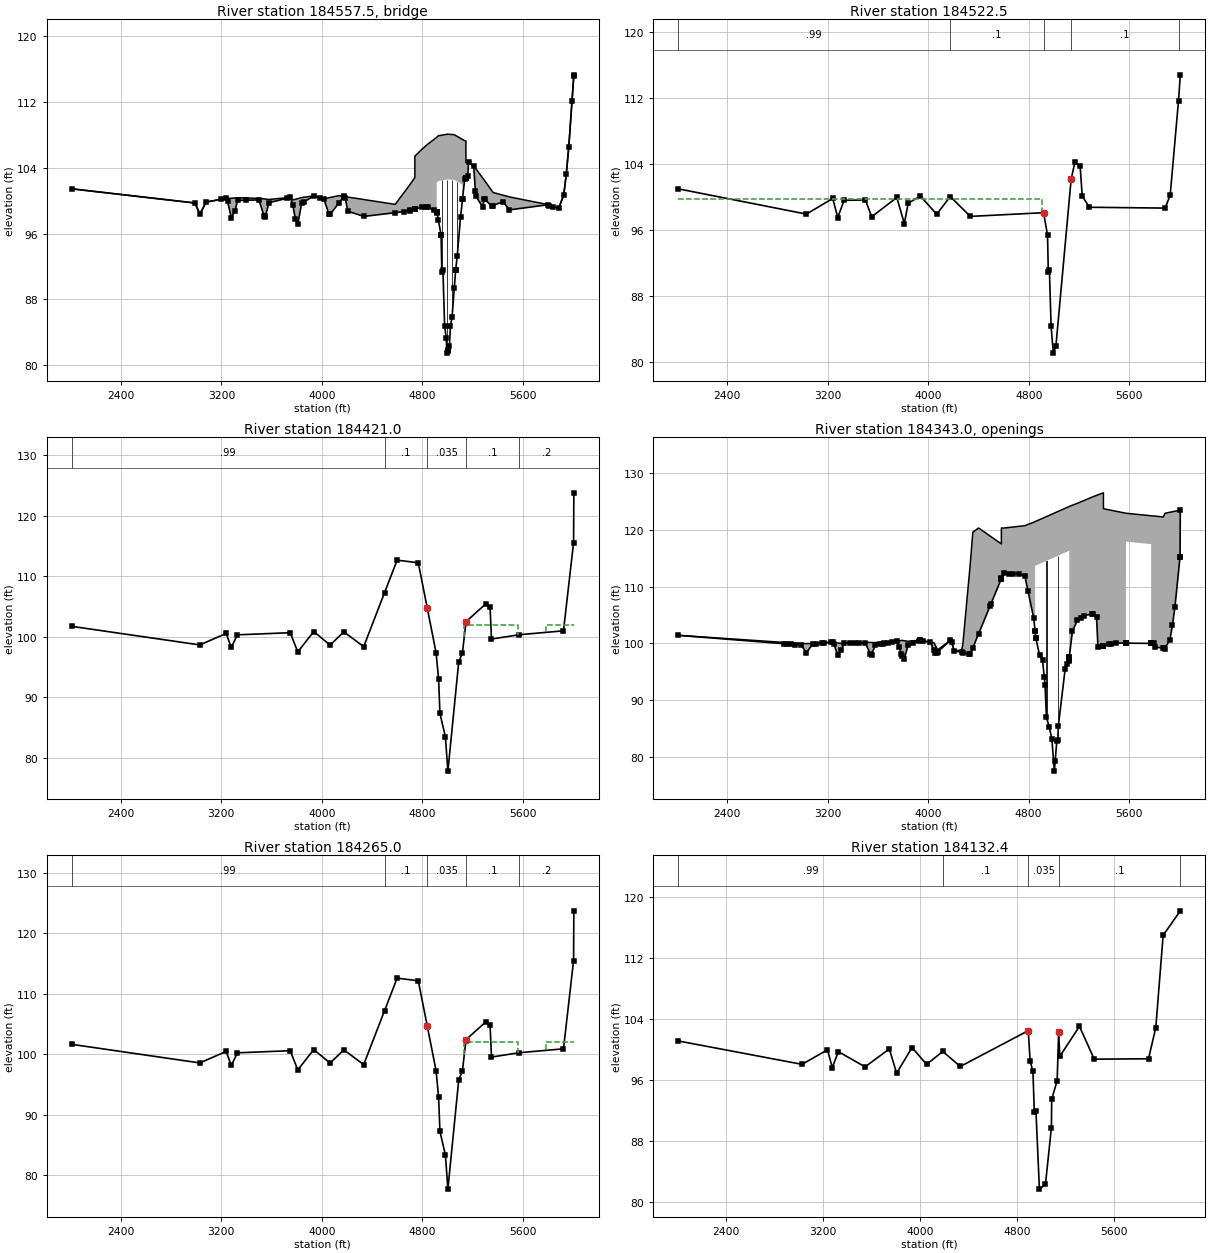
Type RM Length L Ch R = 3 ,184557.5,,,
BEGIN DESCRIPTION:
SAM HOUSTON PARKWAY (HWY 8 WESTBOUND) - 40 degree skew
Structure ID: P00-72
END DESCRIPTION:
Bridge Culvert--1,0,-1,-1, 0
Deck Dist Width WeirC Skew NumUp NumDn MinLoCord MaxHiCord MaxSubmerge Is_Ogee
10,50,2.6,0, 60, 60, , , 0.95, 0, 1,1,,
  2008.9  2988.9  3028.9  3078.9  3238.9  3248.9  3278.9  3308.9  3328.9  3498.9
  3538.9  3548.9  3578.9  3748.9  3768.9  3788.9  3808.9  3838.9  3936.2  4016.2
  4056.2  4066.2  4134.7  4176.2  4186.2  4206.2    4334  4583.7 4702.63 4703.17
 4739.99  4740.1 4794.56 4841.38 4914.21  4914.3  4927.5  5000.3  5054.2 5119.32
 5119.43 5136.68  5146.6 5146.71 5161.24 5167.32 5208.44 5225.07 5281.51  5291.9
  5351.9  5363.5  5441.9  5491.9  5801.9  5885.4  5925.4  5945.4  5965.4  6005.8
  101.43   99.71   98.36   99.83  100.27  100.26  100.29  100.32  100.35  100.27
  100.21  100.19  100.14  100.39  100.08  100.16  100.24  100.37  100.58  100.22
  100.35  100.38   100.6  100.53  100.48  100.43  100.13   99.54  101.98  101.99
   102.8   105.4  106.21  106.84  107.69  107.69  107.88  108.07  108.01  107.43
  107.43  107.28  107.25  104.65  104.47  104.72  104.16  103.89  102.72   102.5
  101.23  100.98  100.66  100.45   99.51   99.09  100.69  103.18   106.5  115.28
  101.43   99.71   98.36   99.83  100.26    99.9   97.94   98.76  100.03  100.08
   98.16   98.03   99.75  100.38   99.46   97.76    97.2   99.66  100.57  100.19
   98.35   98.34    99.7  100.52  100.32   98.71   98.08   98.53   98.75   98.89
   98.96   98.96   99.23   99.26   98.56  102.19  102.38  102.57  102.51  101.93
  100.19  102.59  102.74  102.74  102.95  104.71  104.15  100.55   99.19  100.23
   99.33    99.4   99.88   98.87    99.5   99.09  100.69  103.18   106.5  115.28
  2008.9  2988.9  3028.9  3078.9  3238.9  3248.9  3278.9  3308.9  3328.9  3498.9
  3538.9  3548.9  3578.9  3748.9  3768.9  3788.9  3808.9  3838.9  3936.2  4016.2
  4056.2  4066.2  4134.7  4176.2  4186.2  4206.2    4334  4583.7 4702.63 4703.17
 4739.99  4740.1 4794.56 4841.38 4914.21  4914.3  4927.5  5000.3  5054.2 5119.32
 5119.43 5136.68  5146.6 5146.71 5161.24 5167.32 5208.44 5225.07 5281.51  5291.9
  5351.9  5363.5  5441.9  5491.9  5801.9  5885.4  5925.4  5945.4  5965.4  6005.8
  101.43   99.71   98.36   99.83  100.27  100.26  100.29  100.32  100.35  100.27
  100.21  100.19  100.14  100.39  100.08  100.16  100.24  100.37  100.58  100.22
  100.35  100.38   100.6  100.53  100.48  100.43  100.13   99.54  101.98  101.99
   102.8   105.4  106.21  106.84  107.69  107.69  107.88  108.07  108.01  107.43
  107.43  107.28  107.25  104.65  104.47  104.72  104.16  103.89  102.72   102.5
  101.23  100.98  100.66  100.45   99.51   99.09  100.69  103.18   106.5  115.28
  101.31   99.59   98.24   99.71  100.14   99.78   97.82   98.64   99.91   99.96
   98.04   97.91   99.63  100.26   99.34   97.64   97.08   99.54  100.45  100.07
   98.23   98.22   99.58   100.4   100.2   98.59   97.96   98.41   98.63   98.77
   98.84   98.84   99.11   99.14   98.44  102.07  102.26  102.45  102.39  101.81
  100.07  102.47  102.62  102.62  102.83  104.59  104.03  100.43   99.07  100.11
   99.21   99.28   99.76   98.75   99.38   98.97  100.57  103.06  106.38  115.16
Pier Skew, UpSta & Num, DnSta & Num=  ,4955, 2 ,4955, 2 , 0 , 0 , 0 ,,
       2       2
   90.31  103.45
       2       2
   90.19  103.33
Pier Skew, UpSta & Num, DnSta & Num=  ,4994.6, 2 ,4994.6, 2 , 0 , 0 , 0 ,,
       2       2
   80.52  103.56
       2       2
    80.4  103.44
Pier Skew, UpSta & Num, DnSta & Num=  ,5036.2, 2 ,5036.2, 2 , 0 , 0 , 0 ,,
       2       2
   84.74  103.53
       2       2
   84.62  103.41
Pier Skew, UpSta & Num, DnSta & Num=  ,5077.8, 2 ,5077.8, 2 , 0 , 0 , 0 ,,
       2       2
   92.18  103.31
       2       2
   92.06  103.19
Abutment Skew #Up #Dn= , 2 , 2
  4914.1  4948.8
  102.19   95.81
  4914.1  4948.8
  102.07   95.69
Abutment Skew #Up #Dn= , 2 , 2
 5064.76 5119.52
   91.53  101.93
 5064.76 5119.52
   91.41  101.81
BR Coef= 1 , 1 , 0 ,1.25, 0 ,,,0.8,0,2,0,
WSPro=,,,, 1 ,,,, 0 ,,,, 0 ,,,,-1 ,-1 ,-1 , 0 , 0 , 0 , 0 , 0
BR U #Sta/Elev= 98
  2008.9  101.43  2988.9   99.71  3028.9   98.36  3078.9   99.83  3199.7  100.15
  3238.9  100.26  3248.9    99.9  3278.9   97.94  3308.9   98.76  3328.9  100.03
  3399.7  100.05  3498.9  100.08  3538.9   98.16  3548.9   98.03  3549.7   98.08
  3578.9   99.75  3719.7  100.27  3748.9  100.38  3768.9   99.46  3788.9   97.76
  3808.9    97.2  3838.9   99.66  3854.7   99.81  3936.2  100.57  3984.7  100.34
  4016.2  100.19  4056.2   98.35  4066.2   98.34  4134.7    99.7  4174.5  100.49
  4176.2  100.52  4186.2  100.32  4206.2   98.71    4334   98.08  4583.7   98.53
  4656.5   98.67 4702.63   98.75 4703.17   98.89  4739.6   98.96 4739.99   98.96
  4740.1   98.96 4740.21   98.96 4744.05   98.97 4794.56   99.23    4830   99.25
 4841.38   99.26  4888.7    98.8 4914.21   98.56  4914.3   98.56 4917.15   98.53
  4927.5   97.64  4948.7   95.82  4948.8   95.81 4954.96   91.28 4963.73   91.53
 4976.98   84.81 4990.22   83.27 4994.69   81.47  5000.3   81.76  5002.7   81.89
 5015.32   82.31 5023.02   84.71 5036.19   85.82  5054.2   89.43 5064.66   91.52
 5064.76   91.53 5077.85   93.32 5103.49   97.97 5119.32  100.17 5119.43  100.19
 5136.68  102.59  5146.4  102.73 5146.49  102.73  5146.6  102.74 5146.71  102.74
  5150.5  102.79 5161.24  102.95 5167.32  104.71 5208.44  104.15  5222.4  101.13
 5225.07  100.55 5281.51   99.19  5291.9  100.23  5297.7  100.14  5351.9   99.33
  5363.5    99.4  5441.9   99.88  5491.9   98.87  5801.9    99.5  5805.4   99.39
  5843.1   99.25  5885.4   99.09  5925.4  100.69  5945.4  103.18  5965.4   106.5
  5991.5  112.16  6005.4  115.17  6005.8  115.28
BR U #Mann= 5
  2008.9     .99  4174.5      .1 4917.15    .035 5136.68      .1  5991.5      .2
BR U Banks=4917.15,5136.68
BR D #Sta/Elev= 98
  2008.9  101.31  2988.9   99.59  3028.9   98.24  3078.9   99.71  3199.7  100.03
  3238.9  100.14  3248.9   99.78  3278.9   97.82  3308.9   98.64  3328.9   99.91
  3399.7   99.93  3498.9   99.96  3538.9   98.04  3548.9   97.91  3549.7   97.96
  3578.9   99.63  3719.7  100.15  3748.9  100.26  3768.9   99.34  3788.9   97.64
  3808.9   97.08  3838.9   99.54  3854.7   99.69  3936.2  100.45  3984.7  100.22
  4016.2  100.07  4056.2   98.23  4066.2   98.22  4134.7   99.58  4174.5  100.37
  4176.2   100.4  4186.2   100.2  4206.2   98.59    4334   97.96  4583.7   98.41
  4656.5   98.55 4702.63   98.63 4703.17   98.77  4739.6   98.84 4739.99   98.84
  4740.1   98.84 4740.21   98.84 4744.05   98.85 4794.56   99.11    4830   99.13
 4841.38   99.14  4888.7   98.68 4914.21   98.44  4914.3   98.44 4917.15   98.41
  4927.5   97.52  4948.7    95.7  4948.8   95.69 4954.96   91.16 4963.73   91.41
 4976.98   84.69 4990.22   83.15 4994.69   81.35  5000.3   81.64  5002.7   81.77
 5015.32   82.19 5023.02   84.59 5036.19    85.7  5054.2   89.31 5064.66    91.4
 5064.76   91.41 5077.85    93.2 5103.49   97.85 5119.32  100.05 5119.43  100.07
 5136.68  102.47  5146.4  102.61 5146.49  102.61  5146.6  102.62 5146.71  102.62
  5150.5  102.67 5161.24  102.83 5167.32  104.59 5208.44  104.03  5222.4  101.01
 5225.07  100.43 5281.51   99.07  5291.9  100.11  5297.7  100.02  5351.9   99.21
  5363.5   99.28  5441.9   99.76  5491.9   98.75  5801.9   99.38  5805.4   99.27
  5843.1   99.13  5885.4   98.97  5925.4  100.57  5945.4  103.06  5965.4  106.38
  5991.5  112.04  6005.4  115.05  6005.8  115.16
BR D #Mann= 5
  2008.9     .99  4174.5      .1 4917.15    .035 5136.68      .1  5991.5      .2
BR D Banks=4917.15,5136.68
BC Design=,, 0 ,, 0 ,,,,,,
BC HTab HWMax=115.3
BC Use User HTab Curves=0
BC User HTab FreeFlow(D)= 0

Type RM Length L Ch R = 1 ,184522.5,101.5,101.5,101.5
BEGIN DESCRIPTION:
Downstream Section of Bridge/Culvert/Weir
END DESCRIPTION:
XS GIS Cut Line= 5
      3090679.88     13908034.92      3090739.84     13906170.28
      3090700.19     13905707.61      3090625.08     13905623.79
      3089072.26     13905554.12
#Sta/Elev= 30
  2008.9  100.99  3028.9   97.92  3238.9   99.82  3278.9    97.5  3328.9   99.59
  3498.9   99.64  3548.9   97.59  3748.9   99.94  3808.9   96.76  3838.9   99.22
  3936.2  100.13  4066.2    97.9  4174.5  100.05    4334   97.64 4917.15   98.09
  4948.8   95.37 4954.96   90.84 4963.73   91.09 4976.98   84.37 4994.69   81.03
 5015.32   81.87 5136.68  102.15 5167.32  104.27 5208.44  103.71 5225.07  100.11
 5281.51   98.75  5885.4   98.65  5925.4  100.25  5991.5  111.72  6005.8  114.84
#Mann= 5 , 1 , 0
  2008.9     .99       0  4174.5      .1       0 4917.15    .035       0
 5136.68      .1       0  5991.5      .2       0
#XS Ineff= 2 , 0
       0    4903    99.7    5131       0    99.5
Permanent Ineff=
       F       F
Bank Sta=4917.15,5136.68
XS Rating Curve= 0 ,0
Exp/Cntr=0.5,0.3

Type RM Length L Ch R = 1 ,184421.0,156,156,156
BEGIN DESCRIPTION:
Upstream Section of Bridge/Culvert/Weir
END DESCRIPTION:
XS GIS Cut Line= 6
      3090695.25     13908023.03      3090716.22     13906704.38
      3090722.27     13906219.71      3090683.58     13905646.36
       3090637.3     13905551.09      3089123.68     13905488.84
#Sta/Elev= 30
  2008.9  101.75  3028.9   98.68  3238.9  100.58  3278.9   98.26  3328.9  100.35
  3748.9   100.7  3808.9   97.52  3936.2  100.89  4066.2   98.66  4176.2  100.84
    4334    98.4    4500  107.31 4600.37  112.69 4768.92  112.26 4840.46  104.76
 4910.37   97.42  4930.7   93.03 4941.33   87.35 4984.83   83.48  5004.7   77.82
 5090.78   95.82 5120.66   97.42    5149  102.53 5307.62  105.48 5340.65  104.93
  5351.9   99.65  5574.8  100.37  5925.4  101.01  6005.8   115.6  6007.9  123.82
#Mann= 5 , 1 , 0
  2008.9     .99       0    4500      .1       0 4840.46    .035       0
    5149      .1       0  5574.8      .2       0
#XS Ineff= 3 ,-1
    2008    4840   100.2    5135    5564     102    5785    6010     102
Permanent Ineff=
       F       F       F
Bank Sta=4840.46,5149
XS Rating Curve= 0 ,0
Exp/Cntr=0.5,0.3

Type RM Length L Ch R = 4 ,184343.0,,,
BEGIN DESCRIPTION:
HIGHWAY 8 - 40 degree skew
Structure ID: P00-71
END DESCRIPTION:
Bridge Culvert--1,0,-1,-1, 0
Deck Dist Width WeirC Skew NumUp NumDn MinLoCord MaxHiCord MaxSubmerge Is_Ogee
6.58,142.84,2.6,0, 60, 60, , , 0.95, 0, 1,1,,
  2008.9  2988.9  3028.9  3078.9  3238.9  3278.9  3308.9  3328.9  3498.9  3548.9
  3578.9  3748.9  3768.9  3788.9  3808.9  3838.9  3936.2  4016.2  4045.4  4066.2
  4075.4  4176.2  4186.2  4206.2  4265.4  4275.4    4334  4355.4  4401.6 4582.69
  4582.8 4600.37 4768.92 4840.46  4851.3 4851.39  5123.4 5123.51    5149 5188.34
 5240.86 5307.62 5340.65  5351.9  5395.5 5395.61 5574.91    5575  5575.5 5775.39
  5775.5  5801.9  5805.4    5873  5885.4  5925.4  5945.4  5965.4  6005.8  6007.9
  101.43   99.98   99.98   99.97  100.27  100.08     100  100.04   100.2  100.17
  100.15  100.39  100.42  100.55  100.48  100.38  100.58   100.2  100.12   99.26
   98.88  100.53  100.33   98.78   98.74   99.76   113.8  119.61  120.34  117.54
  120.34  120.33  120.75  121.36  121.47  121.47  124.13  124.13  124.36   124.7
  125.18  125.81  126.09  126.18  126.54  123.74  122.94  122.94  122.94   122.5
   122.5  122.45  122.44  122.29  122.93  123.12  123.21   123.3  123.49   123.5
  101.43   99.71   98.36   99.83  100.26   97.94   98.76  100.03  100.08   98.03
   99.75  100.38   99.46   97.76    97.2   99.66  100.57  100.19   98.85   98.34
   98.52  100.52  100.32   98.71   98.42   98.37   98.08   99.23  101.71  111.42
  111.43  112.37  111.94  104.44  102.14  113.67  116.33   97.61  102.21  104.06
  104.92  105.16  104.61   99.33    99.6    99.6  100.05  117.94  117.94   117.5
  100.01     100   99.39   99.14   99.09  100.69  103.18   106.5  115.28   123.5
  2008.9  2988.9  3028.9  3078.9  3238.9  3278.9  3308.9  3328.9  3498.9  3548.9
  3578.9  3748.9  3768.9  3788.9  3808.9  3838.9  3936.2  4016.2  4045.4  4066.2
  4075.4  4176.2  4186.2  4206.2  4265.4  4275.4    4334  4355.4  4401.6 4582.69
  4582.8 4600.37 4768.92 4840.46  4851.3 4851.39  5123.4 5123.51    5149 5188.34
 5240.86 5307.62 5340.65  5351.9  5395.5 5395.61 5574.91    5575  5575.5 5775.39
  5775.5  5801.9  5805.4    5873  5885.4  5925.4  5945.4  5965.4  6005.8  6007.9
  101.43   99.98   99.98   99.97  100.27  100.08     100  100.04   100.2  100.17
  100.15  100.39  100.42  100.55  100.48  100.38  100.58   100.2  100.12   99.26
   98.88  100.53  100.33   98.78   98.74   99.76   113.8  119.61  120.34  117.54
  120.34  120.33  120.75  121.36  121.47  121.47  124.13  124.13  124.36   124.7
  125.18  125.81  126.09  126.18  126.54  123.74  122.94  122.94  122.94   122.5
   122.5  122.45  122.44  122.29  122.93  123.12  123.21   123.3  123.49   123.5
  101.36   99.64   98.29   99.76  100.19   97.87   98.69   99.96  100.01   97.96
   99.68  100.31   99.39   97.69   97.13   99.59   100.5  100.12   98.78   98.27
   98.45  100.45  100.25   98.64   98.35    98.3   98.01   99.16  101.64  111.35
  111.36   112.3  111.87  104.37  102.07   113.6  116.26   97.54  102.14  103.99
  104.85  105.09  104.54   99.26   99.53   99.53   99.98  117.87  117.87  117.43
   99.94   99.93   99.32   99.07   99.02  100.62  103.11  106.43  115.21  123.43
Pier Skew, UpSta & Num, DnSta & Num=  ,4941.3, 2 ,4941.3, 2 , 0 , 0 , 0 ,,
     3.5     3.5
   85.91  115.61
     3.5     3.5
   85.84  115.54
Pier Skew, UpSta & Num, DnSta & Num=  ,5032.1, 2 ,5032.1, 2 , 0 , 0 , 0 ,,
     3.5     3.5
   81.93  116.51
     3.5     3.5
   81.86  116.44
Abutment Skew #Up #Dn= , 2 , 2
 4851.19  4856.7
  113.67  100.99
 4851.19  4856.7
   113.6  100.92
Abutment Skew #Up #Dn= , 2 , 2
  5118.2  5123.6
   96.97  116.33
  5118.2  5123.6
    96.9  116.26
BR Coef= 1 , 1 , 0 ,0.9, 0 ,,,0.8,0,1.2,0,
WSPro=,,,, 1 ,,,, 0 ,,,, 0 ,,,,-1 ,-1 ,-1 , 0 , 0 , 0 , 0 , 0
BR Coef= 1 , 1 , 0 ,1.25, 0 ,,,0.8,0,2,0,
WSPro=,,,, 1 ,,,, 0 ,,,, 0 ,,,,-1 ,-1 ,-1 , 0 , 0 , 0 , 0 , 0
BC Mult= 3 ,1008.9,5424.5,1008.9,5424.5
BC Mult= 3 ,5274.01,7007.9,5274.01,7007.9
BR U #Sta/Elev= 122
  2008.9  101.43  2847.9   99.96  2877.9    99.9  2907.9   99.85  2937.9    99.8
  2988.9   99.71  3028.9   98.36  3078.9   99.83  3107.9   99.91  3157.9  100.04
  3167.9  100.07  3227.9  100.23  3238.9  100.26  3248.9    99.9  3278.9   97.94
  3308.9   98.76  3328.9  100.03  3377.9  100.04  3417.9  100.06  3447.9  100.07
  3498.9  100.08  3538.9   98.16  3548.9   98.03  3578.9   99.75  3617.9   99.89
  3637.9   99.97  3647.9  100.01  3677.9  100.12  3707.9  100.23  3748.9  100.38
  3768.9   99.46  3785.4   98.06  3788.9   97.76  3808.9    97.2  3838.9   99.66
  3875.4     100  3925.4  100.47  3935.4  100.56  3936.2  100.57  3955.4  100.48
  4016.2  100.19  4045.4   98.85  4056.2   98.35  4066.2   98.34  4075.4   98.52
  4176.2  100.52  4186.2  100.32  4206.2   98.71  4265.4   98.42  4275.4   98.37
  4325.4   98.12    4334   98.08  4355.4   99.23  4401.6  101.71    4493  106.61
    4500  106.99 4582.69  111.42  4582.8  111.43 4582.91  111.43  4583.6  111.47
 4600.37  112.37 4645.18  112.32    4677  112.26 4724.26  112.16 4768.92  111.94
  4794.9  109.22 4840.46  104.44  4851.3  102.14 4851.39  102.12  4856.6  101.01
  4856.7  100.99  4886.5   97.96 4910.37    97.1  4924.3   94.09  4930.7   92.71
 4941.33   87.03 4963.43   85.32 4984.83   83.16  5004.7    77.5  5011.6   79.37
 5024.41   82.85 5032.11   82.95  5036.5   85.51 5090.78    95.5  5106.1   96.32
  5118.2   96.97 5120.66    97.1  5123.4   97.59 5123.51   97.61    5149  102.21
 5188.34  104.06  5216.9  104.53 5240.86  104.92 5307.62  105.16  5309.4  105.13
 5340.65  104.61  5351.9   99.33  5395.3    99.6 5395.39    99.6  5395.5    99.6
 5395.61    99.6  5441.9   99.88    5453   99.92  5491.9  100.07  5574.8  100.05
 5574.91  100.05    5575  100.05  5575.5  100.05    5775  100.01 5775.39  100.01
  5775.5  100.01  5801.9     100  5805.4   99.39    5873   99.14  5878.8   99.11
  5885.4   99.09  5925.4  100.69  5945.4  103.18  5965.4   106.5  6005.4  115.17
  6005.8  115.28  6007.9   123.5
BR U #Mann= 5
  2008.9     .99    4500      .1 4840.46    .035    5149      .1  5574.8      .2
BR U Banks=4840.46,5149
BR D #Sta/Elev= 122
  2008.9  101.36  2847.9   99.89  2877.9   99.83  2907.9   99.78  2937.9   99.73
  2988.9   99.64  3028.9   98.29  3078.9   99.76  3107.9   99.84  3157.9   99.97
  3167.9     100  3227.9  100.16  3238.9  100.19  3248.9   99.83  3278.9   97.87
  3308.9   98.69  3328.9   99.96  3377.9   99.97  3417.9   99.99  3447.9     100
  3498.9  100.01  3538.9   98.09  3548.9   97.96  3578.9   99.68  3617.9   99.82
  3637.9    99.9  3647.9   99.94  3677.9  100.05  3707.9  100.16  3748.9  100.31
  3768.9   99.39  3785.4   97.99  3788.9   97.69  3808.9   97.13  3838.9   99.59
  3875.4   99.93  3925.4   100.4  3935.4  100.49  3936.2   100.5  3955.4  100.41
  4016.2  100.12  4045.4   98.78  4056.2   98.28  4066.2   98.27  4075.4   98.45
  4176.2  100.45  4186.2  100.25  4206.2   98.64  4265.4   98.35  4275.4    98.3
  4325.4   98.05    4334   98.01  4355.4   99.16  4401.6  101.64    4493  106.54
    4500  106.92 4582.69  111.35  4582.8  111.36 4582.91  111.36  4583.6   111.4
 4600.37   112.3 4645.18  112.25    4677  112.19 4724.26  112.09 4768.92  111.87
  4794.9  109.15 4840.46  104.37  4851.3  102.07 4851.39  102.05  4856.6  100.94
  4856.7  100.92  4886.5   97.89 4910.37   97.03  4924.3   94.02  4930.7   92.64
 4941.33   86.96 4963.43   85.25 4984.83   83.09  5004.7   77.43  5011.6    79.3
 5024.41   82.78 5032.11   82.88  5036.5   85.44 5090.78   95.43  5106.1   96.25
  5118.2    96.9 5120.66   97.03  5123.4   97.52 5123.51   97.54    5149  102.14
 5188.34  103.99  5216.9  104.46 5240.86  104.85 5307.62  105.09  5309.4  105.06
 5340.65  104.54  5351.9   99.26  5395.3   99.53 5395.39   99.53  5395.5   99.53
 5395.61   99.53  5441.9   99.81    5453   99.85  5491.9     100  5574.8   99.98
 5574.91   99.98    5575   99.98  5575.5   99.98    5775   99.94 5775.39   99.94
  5775.5   99.94  5801.9   99.93  5805.4   99.32    5873   99.07  5878.8   99.04
  5885.4   99.02  5925.4  100.62  5945.4  103.11  5965.4  106.43  6005.4   115.1
  6005.8  115.21  6007.9  123.43
BR D #Mann= 5
  2008.9     .99    4500      .1 4840.46    .035    5149      .1  5574.8      .2
BR D Banks=4840.46,5149
BC Design=,, 0 ,, 0 ,,,,,,
BC HTab HWMax=123.82
BC Use User HTab Curves=0
BC User HTab FreeFlow(D)= 0

Type RM Length L Ch R = 1 ,184265.0,132.6,132.6,132.6
BEGIN DESCRIPTION:
Downstream Section of Bridge/Culvert/Weir
END DESCRIPTION:
XS GIS Cut Line= 6
      3090814.96       13907923.      3090835.92     13906604.34
      3090841.97     13906119.67      3090803.28     13905546.32
        3090757.     13905451.05      3089243.38     13905388.81
#Sta/Elev= 30
  2008.9  101.66  3028.9   98.59  3238.9  100.49  3278.9   98.17  3328.9  100.26
  3748.9  100.61  3808.9   97.43  3936.2   100.8  4066.2   98.57  4176.2  100.75
    4334   98.31    4500  107.22 4600.37   112.6 4768.92  112.17 4840.46  104.67
 4910.37   97.33  4930.7   92.94 4941.33   87.26 4984.83   83.39  5004.7   77.73
 5090.78   95.73 5120.66   97.33    5149  102.44 5307.62  105.39 5340.65  104.84
  5351.9   99.56  5574.8  100.28  5925.4  100.92  6005.8  115.51  6007.9  123.73
#Mann= 5 , 1 , 0
  2008.9     .99       0    4500      .1       0 4840.46    .035       0
    5149      .1       0  5574.8      .2       0
#XS Ineff= 3 ,-1
    2008    4840     100    5135    5564     102    5785    6010     102
Permanent Ineff=
       F       F       F
Bank Sta=4840.46,5149
XS Rating Curve= 0 ,0
Exp/Cntr=0.5,0.3

Type RM Length L Ch R = 1 ,184132.4,70,70,70
BEGIN DESCRIPTION:
Upstream Section of Bridge/Culvert/Weir
END DESCRIPTION:
XS GIS Cut Line= 6
      3090849.88     13908017.46      3090825.64      13906188.5
       3090779.4     13905602.46      3090700.08     13905417.39
      3090642.65     13905349.82      3089212.24     13905298.51
#Sta/Elev= 30
  2008.9  101.13  3028.9   98.06  3238.9   99.96  3278.9   97.64  3328.9   99.73
  3548.9   97.73  3748.9  100.08  3808.9    96.9  3936.2  100.27  4056.2   98.05
  4189.6   99.75    4334   97.78 4894.43  102.48 4909.43   98.48 4932.63   97.16
 4943.94   91.83 4957.57    91.9 4985.99   81.69 5035.81   82.31 5085.01   89.77
 5087.32   93.47 5132.34   95.92 5144.76   102.3  5153.9   99.11 5316.24  103.04
 5437.82   98.74  5885.4   98.79  5945.4  102.88  6005.8  114.98  6147.5   118.2
#Mann= 5 , 1 , 0
  2008.9     .99       0  4189.6      .1       0 4894.43    .035       0
 5144.76      .1       0  6147.5      .2       0
#XS Ineff= 2 , 0
       0    4887     100    5153       0    99.2
Permanent Ineff=
       F       F
Bank Sta=4894.43,5144.76
XS Rating Curve= 0 ,0
Exp/Cntr=0.5,0.3