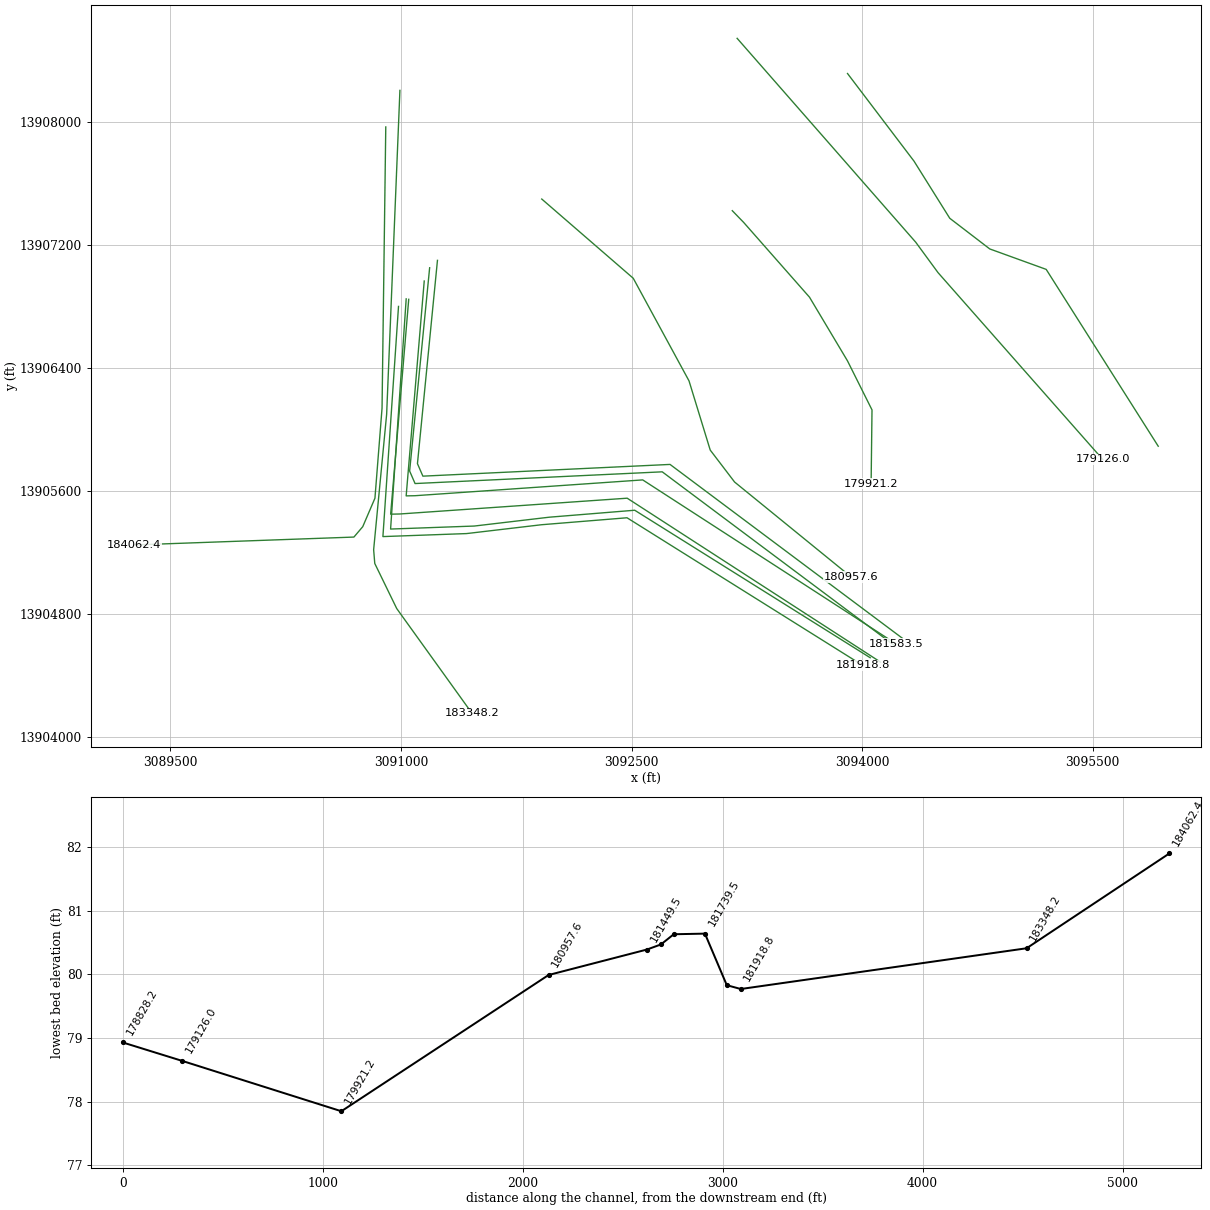
HEC-RAS study P100-00-00.prj: P100-00-00

--- P100-00-00.g01 (geometry) --- (continued)

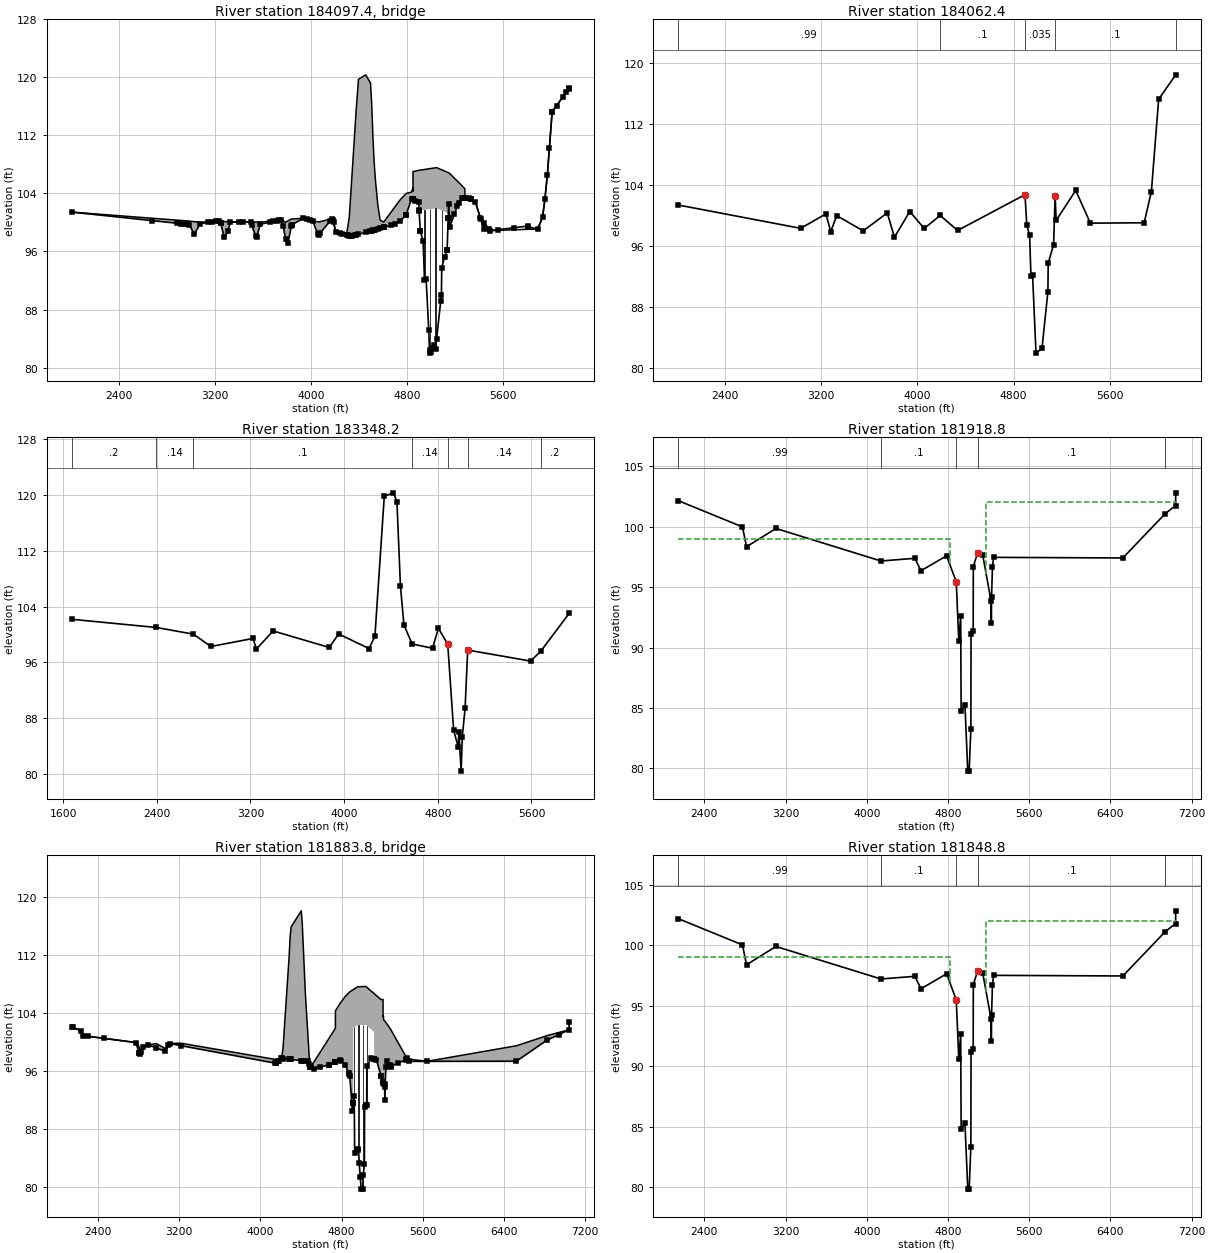
Type RM Length L Ch R = 3 ,184097.4,,,
BEGIN DESCRIPTION:
SAM HOUSTON PARKWAY (HWY 8 EASTBOUND) - 40 degree skew
Structure ID: P00-70
END DESCRIPTION:
Bridge Culvert--1,0,-1,-1, 0
Deck Dist Width WeirC Skew NumUp NumDn MinLoCord MaxHiCord MaxSubmerge Is_Ogee
10,50,2.6,0, 60, 60, , , 0.95, 0, 1,1,,
  2008.9  2988.9  3028.9  3078.9  3238.9  3278.9  3328.9  3498.9  3548.9  3578.9
  3748.9  3788.9  3808.9  3838.9  3936.2  4016.2  4066.2  4176.2  4206.2  4258.2
  4298.2  4318.2    4375    4395    4455    4495    4505    4515    4525    4535
    4555    4575  4605.1 4741.43 4791.87 4837.07  4847.7 4848.39  4848.5 4894.43
 4898.75  5044.6  5140.8 5140.91 5144.76  5153.9  5252.1    5280 5280.11 5316.24
 5366.91 5437.82  5441.9  5491.9  5885.4  5925.4  5945.4  5965.4  6005.8  6147.5
  101.43  100.19  100.11  100.01  100.27  100.12  100.11  100.09  100.06  100.02
  100.39  100.03  100.23  100.48  100.58   100.2  100.07  100.53   98.72   98.46
   98.57  100.65  115.26  119.74  120.35  119.23  116.38  111.87  108.43  106.04
  102.53  100.32  100.05  103.12     104   104.2  104.79  104.31  107.01  107.18
  107.19  107.56  106.88  106.88  106.84  106.74  105.13  104.62  103.35  103.35
  102.85   99.14   99.89   98.88    99.1   100.7  103.19  106.51  115.29   118.5
  101.43   99.71   98.36   99.83  100.26   97.94  100.03  100.08   98.03   99.75
  100.38   97.76    97.2   99.66  100.57  100.19   98.34  100.52   98.71   98.45
   98.26   98.16   98.27   98.36   98.64   98.83   98.88   98.93   98.97   99.02
   99.11   99.21   99.35  100.15  101.09  103.29   103.2  103.19  103.19  102.78
  101.63  101.96  101.28  100.62   102.6   99.41  103.34  103.34  103.34  103.34
  102.84   99.04   99.88   98.87   99.09  100.69  103.18   106.5  115.28   118.5
  2008.9  2988.9  3028.9  3078.9  3238.9  3278.9  3328.9  3498.9  3548.9  3578.9
  3748.9  3788.9  3808.9  3838.9  3936.2  4016.2  4066.2  4176.2  4206.2  4258.2
  4298.2  4318.2    4375    4395    4455    4495    4505    4515    4525    4535
    4555    4575  4605.1 4741.43 4791.87 4837.07  4847.7 4848.39  4848.5 4894.43
 4898.75  5044.6  5140.8 5140.91 5144.76  5153.9  5252.1    5280 5280.11 5316.24
 5366.91 5437.82  5441.9  5491.9  5885.4  5925.4  5945.4  5965.4  6005.8  6147.5
  101.43  100.19  100.11  100.01  100.27  100.12  100.11  100.09  100.06  100.02
  100.39  100.03  100.23  100.48  100.58   100.2  100.07  100.53   98.72   98.46
   98.57  100.65  115.26  119.74  120.35  119.23  116.38  111.87  108.43  106.04
  102.53  100.32  100.05  103.12     104   104.2  104.79  104.31  107.01  107.18
  107.19  107.56  106.88  106.88  106.84  106.74  105.13  104.62  103.35  103.35
  102.85   99.14   99.89   98.88    99.1   100.7  103.19  106.51  115.29   118.5
  101.36   99.64   98.29   99.76  100.19   97.87   99.96  100.01   97.96   99.68
  100.31   97.69   97.13   99.59   100.5  100.12   98.27  100.45   98.64   98.38
   98.19   98.09    98.2   98.29   98.57   98.76   98.81   98.86    98.9   98.95
   99.04   99.14   99.28  100.08  101.02  103.22  103.13  103.12  103.12  102.71
  101.56  101.89  101.21  100.55  102.53   99.34  103.27  103.27  103.27  103.27
  102.77   98.97   99.81    98.8   99.02  100.62  103.11  106.43  115.21  118.43
Pier Skew, UpSta & Num, DnSta & Num=  ,4943.9, 2 ,4943.9, 2 , 0 , 0 , 0 ,,
       2       2
   91.14   102.7
       2       2
   91.07  102.63
Pier Skew, UpSta & Num, DnSta & Num=  ,4988.1, 2 ,4988.1, 2 , 0 , 0 , 0 ,,
       2       2
   81.21  102.82
       2       2
   81.14  102.75
Pier Skew, UpSta & Num, DnSta & Num=  ,5035.8, 2 ,5035.8, 2 , 0 , 0 , 0 ,,
       2       2
   81.64  102.94
       2       2
   81.57  102.87
Pier Skew, UpSta & Num, DnSta & Num=  ,5087.3, 2 ,5087.3, 2 , 0 , 0 , 0 ,,
       2       2
   91.17  102.78
       2       2
    91.1  102.71
Abutment Skew #Up #Dn= , 2 , 2
 4898.55 4909.53
  101.63   98.77
 4898.55 4909.53
  101.56    98.7
Abutment Skew #Up #Dn= , 2 , 2
 5132.44    5141
   96.27  101.28
 5132.44    5141
    96.2  101.21
BR Coef= 1 , 1 , 0 ,1.25, 0 ,,,0.8,0,2,0,
WSPro=,,,, 1 ,,,, 0 ,,,, 0 ,,,,-1 ,-1 ,-1 , 0 , 0 , 0 , 0 , 0
BR U #Sta/Elev= 143
  2008.9  101.43  2677.6  100.26  2887.6   99.89  2917.6   99.84  2947.6   99.78
  2977.6   99.73  2988.9   99.71  3028.9   98.36  3078.9   99.83  3147.6  100.01
  3177.6   100.1  3207.6  100.18  3238.9  100.26  3247.6   99.95  3248.9    99.9
  3278.9   97.94  3308.9   98.76  3328.9  100.03  3397.6  100.05  3437.6  100.06
  3498.9  100.08  3507.6   99.66  3538.9   98.16  3548.9   98.03  3578.9   99.75
  3657.6  100.04  3687.6  100.15  3717.6  100.26  3737.6  100.34  3748.9  100.38
  3768.9   99.46  3788.9   97.76  3808.9    97.2  3837.6   99.55  3838.2    99.6
  3838.9   99.66  3936.2  100.57  3968.2  100.42  3988.2  100.32  4016.2  100.19
  4056.2   98.35  4066.2   98.34  4078.2   98.58  4158.2  100.16  4176.2  100.52
  4186.2  100.32  4189.6  100.05  4206.2   98.71  4238.2   98.55  4258.2   98.45
  4298.2   98.26  4308.2   98.21  4318.2   98.16    4334   98.08    4345   98.13
    4365   98.22    4375   98.27    4395   98.36    4455   98.64    4495   98.83
    4505   98.88    4515   98.93    4525   98.97    4535   99.02    4555   99.11
    4575   99.21  4605.1   99.35    4610   99.37  4665.2   99.63 4700.24   99.79
 4741.43  100.15  4788.4  101.03 4791.87  101.09 4837.07  103.29  4847.1   103.2
  4847.7   103.2 4848.39  103.19  4848.5  103.19 4848.61  103.19  4848.8  103.19
  4868.5  103.01 4894.43  102.78 4898.66  101.65 4898.75  101.63 4909.43   98.78
 4909.53   98.77 4932.63   97.46 4943.94   92.13 4957.57    92.2 4979.52   85.22
 4985.99   81.99 4988.07   82.41 4995.23   82.11  5009.7   82.69 5020.56   83.08
 5035.81   82.61  5044.6   83.94  5078.7   89.11 5085.01   90.07 5087.32   93.77
 5111.57   95.27 5132.34   96.22 5132.44   96.27  5140.8  100.57 5140.91  100.62
 5144.76   102.6  5150.3  100.67  5153.9   99.41    5192  101.12 5217.45  102.27
  5232.2  102.73  5252.1  103.34 5279.89  103.34    5280  103.34 5280.11  103.34
  5280.3  103.34  5280.8  103.34 5316.24  103.34  5330.1   103.2  5330.4   103.2
 5366.91  102.84  5408.6  100.61  5410.2  100.52 5437.82   99.04  5441.9   99.88
  5478.7   99.14  5491.9   98.87  5555.5      99  5688.5   99.27  5801.9    99.5
  5805.4   99.39  5885.4   99.09  5925.4  100.69  5945.4  103.18  5965.4   106.5
  5982.6  110.23  6005.4  115.17  6005.8  115.28  6042.6  116.12  6092.6  117.25
  6122.6  117.93  6142.6  118.39  6147.5   118.5
BR U #Mann= 5
  2008.9     .99  4189.6      .1 4894.43    .035 5144.76      .1  6147.5      .2
BR U Banks=4894.43,5144.76
BR D #Sta/Elev= 143
  2008.9  101.36  2677.6  100.19  2887.6   99.82  2917.6   99.77  2947.6   99.71
  2977.6   99.66  2988.9   99.64  3028.9   98.29  3078.9   99.76  3147.6   99.94
  3177.6  100.03  3207.6  100.11  3238.9  100.19  3247.6   99.88  3248.9   99.83
  3278.9   97.87  3308.9   98.69  3328.9   99.96  3397.6   99.98  3437.6   99.99
  3498.9  100.01  3507.6   99.59  3538.9   98.09  3548.9   97.96  3578.9   99.68
  3657.6   99.97  3687.6  100.08  3717.6  100.19  3737.6  100.27  3748.9  100.31
  3768.9   99.39  3788.9   97.69  3808.9   97.13  3837.6   99.48  3838.2   99.53
  3838.9   99.59  3936.2   100.5  3968.2  100.35  3988.2  100.25  4016.2  100.12
  4056.2   98.28  4066.2   98.27  4078.2   98.51  4158.2  100.09  4176.2  100.45
  4186.2  100.25  4189.6   99.98  4206.2   98.64  4238.2   98.48  4258.2   98.38
  4298.2   98.19  4308.2   98.14  4318.2   98.09    4334   98.01    4345   98.06
    4365   98.15    4375    98.2    4395   98.29    4455   98.57    4495   98.76
    4505   98.81    4515   98.86    4525    98.9    4535   98.95    4555   99.04
    4575   99.14  4605.1   99.28    4610    99.3  4665.2   99.56 4700.24   99.72
 4741.43  100.08  4788.4  100.96 4791.87  101.02 4837.07  103.22  4847.1  103.13
  4847.7  103.13 4848.39  103.12  4848.5  103.12 4848.61  103.12  4848.8  103.12
  4868.5  102.94 4894.43  102.71 4898.66  101.58 4898.75  101.56 4909.43   98.71
 4909.53    98.7 4932.63   97.39 4943.94   92.06 4957.57   92.13 4979.52   85.15
 4985.99   81.92 4988.07   82.34 4995.23   82.04  5009.7   82.62 5020.56   83.01
 5035.81   82.54  5044.6   83.87  5078.7   89.04 5085.01      90 5087.32    93.7
 5111.57    95.2 5132.34   96.15 5132.44    96.2  5140.8   100.5 5140.91  100.55
 5144.76  102.53  5150.3   100.6  5153.9   99.34    5192  101.05 5217.45   102.2
  5232.2  102.66  5252.1  103.27 5279.89  103.27    5280  103.27 5280.11  103.27
  5280.3  103.27  5280.8  103.27 5316.24  103.27  5330.1  103.13  5330.4  103.13
 5366.91  102.77  5408.6  100.54  5410.2  100.45 5437.82   98.97  5441.9   99.81
  5478.7   99.07  5491.9    98.8  5555.5   98.93  5688.5    99.2  5801.9   99.43
  5805.4   99.32  5885.4   99.02  5925.4  100.62  5945.4  103.11  5965.4  106.43
  5982.6  110.16  6005.4   115.1  6005.8  115.21  6042.6  116.05  6092.6  117.18
  6122.6  117.86  6142.6  118.32  6147.5  118.43
BR D #Mann= 5
  2008.9     .99  4189.6      .1 4894.43    .035 5144.76      .1  6147.5      .2
BR D Banks=4894.43,5144.76
BC Design=,, 0 ,, 0 ,,,,,,
BC HTab HWMax=118.2
BC Use User HTab Curves=0
BC User HTab FreeFlow(D)= 0

Type RM Length L Ch R = 1 ,184062.4,714.2,714.2,714.2
BEGIN DESCRIPTION:
Downstream Section of Bridge/Culvert/Weir
END DESCRIPTION:
XS GIS Cut Line= 6
      3090901.32     13907969.98      3090877.08     13906141.02
      3090830.84     13905554.98      3090751.52     13905369.91
      3090694.09     13905302.34      3089263.68     13905251.03
#Sta/Elev= 30
  2008.9  101.34  3028.9   98.27  3238.9  100.17  3278.9   97.85  3328.9   99.94
  3548.9   97.94  3748.9  100.29  3808.9   97.11  3936.2  100.48  4056.2   98.26
  4189.6   99.96    4334   97.99 4894.43  102.69 4909.43   98.69 4932.63   97.37
 4943.94   92.04 4957.57   92.11 4985.99    81.9 5035.81   82.52 5085.01   89.98
 5087.32   93.68 5132.34   96.13 5144.76  102.51  5153.9   99.32 5316.24  103.25
 5437.82   98.95  5885.4      99  5945.4  103.09  6005.8  115.19  6147.5  118.41
#Mann= 5 , 1 , 0
  2008.9     .99       0  4189.6      .1       0 4894.43    .035       0
 5144.76      .1       0  6147.5      .2       0
#XS Ineff= 2 , 0
       0    4887    99.8    5153       0      99
Permanent Ineff=
       F       F
Bank Sta=4894.43,5144.76
XS Rating Curve= 0 ,0
Exp/Cntr=0.5,0.3

Type RM Length L Ch R = 1 ,183348.2,64.5,1429.4,1656.3
BEGIN DESCRIPTION:
Cross Section 183348.2
END DESCRIPTION:
XS GIS Cut Line= 6
      3090993.34     13908207.82      3090906.97     13906100.96
      3090822.41     13905220.11      3090829.76     13905130.64
      3090972.42     13904837.67      3091462.64     13904155.62
#Sta/Elev= 30
  1671.8  102.17  2393.3     101  2712.6  100.04  2861.4   98.27  3221.4   99.42
  3251.4   97.91    3393   100.5    3873   98.13    3953  100.06    4213   97.98
    4263   99.74    4343   119.8  4420.9  120.29  4450.9  119.04  4480.9  106.95
  4510.9  101.36  4580.5   98.63    4755   98.02    4805  100.87    4885   98.61
    4935   86.32    4975   83.83  4979.5   86.05  4999.8   80.41    5009   85.28
  5033.4   89.47  5055.4   97.76  5592.5   96.18  5677.9   97.56  5922.5  103.02
#Mann= 7 , 1 , 0
  1671.8      .2       0  2393.3     .14       0  2712.6      .1       0
  4580.5     .14       0    4885    .035       0  5055.4     .14       0
  5677.9      .2       0
#XS Ineff= 2 , 0
       0    4805  100.87               0
Permanent Ineff=
       F       F
Bank Sta=4885,5055.4
XS Rating Curve= 0 ,0
Exp/Cntr=0.5,0.3

Type RM Length L Ch R = 1 ,181918.8,70,70,70
BEGIN DESCRIPTION:
Upstream Section of Bridge/Culvert/Weir
END DESCRIPTION:
XS GIS Cut Line= 6
      3090984.16     13906802.58      3090882.71     13905305.51
      3091427.13     13905325.07      3091914.12     13905382.56
      3092470.43     13905427.89      3094002.32     13904468.53
#Sta/Elev= 30
  2140.9  102.16  2775.7   99.98  2815.7   98.34  3105.7   99.85  4139.8   97.16
  4473.6   97.38  4533.6   96.35  4786.3   97.59 4881.22   95.43  4906.5    90.5
  4924.8   92.64 4929.22   84.73 4966.85   85.25 4994.24   79.81 5008.26   79.77
 5025.09   83.28 5026.82   91.15 5047.94   91.39 5049.22   96.69 5090.56   97.81
 5142.14   97.64 5223.62   93.87 5226.69   92.03 5228.93   94.22 5237.63   96.63
 5248.38   97.46  6522.1   97.41  6939.7  101.08  7042.1  101.75  7042.2   102.8
#Mann= 5 , 1 , 0
  2140.9     .99       0  4139.8      .1       0 4881.22    .035       0
 5090.56      .1       0  6939.7      .2       0
#XS Ineff= 2 , 0
       0    4819      99    5176       0     102
Permanent Ineff=
       F       F
Bank Sta=4881.22,5090.56
XS Rating Curve= 0 ,0
Exp/Cntr=0.5,0.3

Type RM Length L Ch R = 3 ,181883.8,,,
BEGIN DESCRIPTION:
SAM HOUSTON PARKWAY (HWY 8 EASTBOUND) - 50 degree skew
Structure ID: P00-69
END DESCRIPTION:
Bridge Culvert--1,0,-1,-1, 0
Deck Dist Width WeirC Skew NumUp NumDn MinLoCord MaxHiCord MaxSubmerge Is_Ogee
10,50,2.6,0, 60, 60, , , 0.95, 0, 1,1,,
  2140.9  2235.7  2255.7  2305.7  2775.7  2805.6  2815.7  2825.7  2845.7  2895.7
  2975.7  3065.7  3105.7  3215.7  4155.6  4175.7  4213.4  4223.4  4283.4  4293.4
  4303.4  4403.4  4413.4  4443.4  4473.6  4483.4  4491.9  4494.3  4533.6 4739.59
  4739.7  4786.3  4837.7 4881.22  4906.5 4915.88 4915.97  4959.2  5040.9 5120.72
 5120.83 5142.14  5188.8  5208.6 5208.71  5212.9  5214.1 5223.62 5226.69 5228.93
 5237.63 5248.38 5282.37  5436.9  5462.1  5644.7  6522.1  6822.1  7042.1  7042.2
  102.16   101.6  101.17  100.85   99.99   99.39   98.92   98.69   99.37   99.67
   99.84   99.16   99.86    99.9   97.64    97.4   98.23   99.17  111.75  114.53
  115.93  118.15  116.35  106.83   99.85   97.59   97.15   96.65   97.42  101.96
  104.36   105.4  106.37  106.98  107.21  107.29  107.29  107.68  107.71  106.74
  106.74  106.48  105.91  105.94  103.54  103.67  103.14  102.97  102.92  102.88
  102.72  102.53  101.83      98   97.69    97.4   99.54  100.93  101.75   102.8
  102.16  101.59  100.93  100.84   99.98   98.55   98.34   98.68   99.36   99.66
   99.24   98.76   99.85   99.56   97.12   97.39   97.79   97.77   97.68   97.66
   97.65   97.49   97.47   97.43   97.38      97   96.68   96.61   96.35   97.33
   97.33   97.59   96.85   95.43    90.5    91.6  101.99  102.38  102.41  101.44
   97.71   97.64   95.41   94.53   94.53   94.34   94.29   93.87   92.03   94.22
   96.63   97.46   96.66   97.69   97.39   97.39   97.41   100.3  101.75   102.8
  2140.9  2235.7  2255.7  2305.7  2775.7  2805.6  2815.7  2825.7  2845.7  2895.7
  2975.7  3065.7  3105.7  3215.7  4155.6  4175.7  4213.4  4223.4  4283.4  4293.4
  4303.4  4403.4  4413.4  4443.4  4473.6  4483.4  4491.9  4494.3  4533.6 4739.59
  4739.7  4786.3  4837.7 4881.22  4906.5 4915.88 4915.97  4959.2  5040.9 5120.72
 5120.83 5142.14  5188.8  5208.6 5208.71  5212.9  5214.1 5223.62 5226.69 5228.93
 5237.63 5248.38 5282.37  5436.9  5462.1  5644.7  6522.1  6822.1  7042.1  7042.2
  102.16   101.6  101.17  100.85   99.99   99.39   98.92   98.69   99.37   99.67
   99.84   99.16   99.86    99.9   97.64    97.4   98.23   99.17  111.75  114.53
  115.93  118.15  116.35  106.83   99.85   97.59   97.15   96.65   97.42  101.96
  104.36   105.4  106.37  106.98  107.21  107.29  107.29  107.68  107.71  106.74
  106.74  106.48  105.91  105.94  103.54  103.67  103.14  102.97  102.92  102.88
  102.72  102.53  101.83      98   97.69    97.4   99.54  100.93  101.75   102.8
  102.14  101.57  100.91  100.82   99.96   98.53   98.32   98.66   99.34   99.64
   99.22   98.74   99.83   99.54    97.1   97.37   97.77   97.75   97.66   97.64
   97.63   97.47   97.45   97.41   97.36   96.98   96.66   96.59   96.33   97.31
   97.31   97.57   96.83   95.41   90.48   91.58  101.97  102.36  102.39  101.42
   97.69   97.62   95.39   94.51   94.51   94.32   94.27   93.85   92.01    94.2
   96.61   97.44   96.64   97.67   97.37   97.37   97.39  100.28  101.73  102.78
Pier Skew, UpSta & Num, DnSta & Num=  ,4924.8, 2 ,4924.8, 2 , 0 , 0 , 0 ,,
       3       3
   88.96  103.08
       3       3
   88.94  103.06
Pier Skew, UpSta & Num, DnSta & Num=  ,4966.8, 2 ,4966.8, 2 , 0 , 0 , 0 ,,
       3       3
   83.89  103.38
       3       3
   83.87  103.36
Pier Skew, UpSta & Num, DnSta & Num=  ,5008.3, 2 ,5008.3, 2 , 0 , 0 , 0 ,,
       3       3
   78.77   103.4
       3       3
   78.75  103.38
Pier Skew, UpSta & Num, DnSta & Num=  ,5047.9, 2 ,5047.9, 2 , 0 , 0 , 0 ,,
       3       3
   90.37  103.34
       3       3
   90.35  103.32
BR Coef= 1 , 1 , 0 ,1.25, 0 ,,,0.8,0,2,0,
WSPro=,,,, 1 ,,,, 0 ,,,, 0 ,,,,-1 ,-1 ,-1 , 0 , 0 , 0 , 0 , 0
BR U #Sta/Elev= 100
  2140.9  102.16  2155.7  102.07  2235.7  101.59  2255.7  100.93  2305.7  100.84
  2455.7  100.56  2775.7   99.98  2805.6   98.55  2805.7   98.55  2815.7   98.34
  2825.7   98.68  2845.7   99.36  2895.7   99.66  2975.7   99.24  3065.7   98.76
  3095.7   99.58  3105.7   99.85  3215.7   99.56  4139.8   97.16  4155.6   97.12
  4155.7   97.12  4175.7   97.39  4183.4    97.5  4205.7    97.8  4213.4   97.79
  4223.4   97.77  4283.4   97.68  4293.4   97.66  4303.4   97.65  4403.4   97.49
  4413.4   97.47  4443.4   97.43  4473.6   97.38  4483.4      97  4491.9   96.68
  4493.6   96.61  4494.3   96.61  4533.6   96.35  4588.6   96.58    4672   96.92
 4678.08   96.95 4734.14    97.3 4739.59   97.33  4739.7   97.33 4739.81   97.33
  4786.3   97.59  4798.5   97.41  4837.7   96.85  4868.7   95.84  4873.1   95.69
 4881.22   95.43  4906.5    90.5 4915.88    91.6 4915.97   91.61 4916.03   91.61
  4924.8   92.64 4929.22   84.73  4959.2   85.14 4966.85   85.25 4974.91   83.32
 4983.74   81.41 4994.24   79.81 5008.26   79.77 5013.44   81.66 5025.09   83.28
 5026.82   91.15  5040.9   91.31 5047.94   91.39 5049.22   96.69 5090.56   97.81
 5120.67   97.71 5120.72   97.71 5120.83   97.71 5142.14   97.64 5188.29   95.43
  5188.8   95.41 5208.49   94.54  5208.6   94.53 5208.71   94.53  5212.9   94.34
  5214.1   94.29 5223.62   93.87 5226.69   92.03 5228.93   94.22 5237.63   96.63
 5248.38   97.46  5272.4   96.89 5282.37   96.66 5283.01   96.72  5359.8   97.17
  5432.1   97.59  5436.9   97.69  5442.1    97.8  5462.1   97.39  5644.7   97.39
  6522.1   97.41  6822.1   100.3  6939.7  101.08  7042.1  101.75  7042.2   102.8
BR U #Mann= 5
  2140.9     .99  4139.8      .1 4881.22    .035 5090.56      .1  6939.7      .2
BR U Banks=4881.22,5090.56
BR D #Sta/Elev= 100
  2140.9  102.14  2155.7  102.05  2235.7  101.57  2255.7  100.91  2305.7  100.82
  2455.7  100.54  2775.7   99.96  2805.6   98.53  2805.7   98.53  2815.7   98.32
  2825.7   98.66  2845.7   99.34  2895.7   99.64  2975.7   99.22  3065.7   98.74
  3095.7   99.56  3105.7   99.83  3215.7   99.54  4139.8   97.14  4155.6    97.1
  4155.7    97.1  4175.7   97.37  4183.4   97.48  4205.7   97.78  4213.4   97.77
  4223.4   97.75  4283.4   97.66  4293.4   97.64  4303.4   97.63  4403.4   97.47
  4413.4   97.45  4443.4   97.41  4473.6   97.36  4483.4   96.98  4491.9   96.66
  4493.6   96.59  4494.3   96.59  4533.6   96.33  4588.6   96.56    4672    96.9
 4678.08   96.93 4734.14   97.28 4739.59   97.31  4739.7   97.31 4739.81   97.31
  4786.3   97.57  4798.5   97.39  4837.7   96.83  4868.7   95.82  4873.1   95.67
 4881.22   95.41  4906.5   90.48 4915.88   91.58 4915.97   91.59 4916.03   91.59
  4924.8   92.62 4929.22   84.71  4959.2   85.12 4966.85   85.23 4974.91    83.3
 4983.74   81.39 4994.24   79.79 5008.26   79.75 5013.44   81.64 5025.09   83.26
 5026.82   91.13  5040.9   91.29 5047.94   91.37 5049.22   96.67 5090.56   97.79
 5120.67   97.69 5120.72   97.69 5120.83   97.69 5142.14   97.62 5188.29   95.41
  5188.8   95.39 5208.49   94.52  5208.6   94.51 5208.71   94.51  5212.9   94.32
  5214.1   94.27 5223.62   93.85 5226.69   92.01 5228.93    94.2 5237.63   96.61
 5248.38   97.44  5272.4   96.87 5282.37   96.64 5283.01    96.7  5359.8   97.15
  5432.1   97.57  5436.9   97.67  5442.1   97.78  5462.1   97.37  5644.7   97.37
  6522.1   97.39  6822.1  100.28  6939.7  101.06  7042.1  101.73  7042.2  102.78
BR D #Mann= 5
  2140.9     .99  4139.8      .1 4881.22    .035 5090.56      .1  6939.7      .2
BR D Banks=4881.22,5090.56
BC Design=,, 0 ,, 0 ,,,,,,
BC HTab HWMax=102.8
BC Use User HTab Curves=0
BC User HTab FreeFlow(D)= 0

Type RM Length L Ch R = 1 ,181848.8,109.3,109.3,109.3
BEGIN DESCRIPTION:
Downstream Section of Bridge/Culvert/Weir
END DESCRIPTION:
XS GIS Cut Line= 6
      3091034.14     13906851.59      3090932.69     13905354.51
      3091477.11     13905374.07       3091964.1     13905431.56
      3092520.41     13905476.89       3094052.3     13904517.54
#Sta/Elev= 30
  2140.9  102.22  2775.7  100.04  2815.7    98.4  3105.7   99.91  4139.8   97.22
  4473.6   97.44  4533.6   96.41  4786.3   97.65 4881.22   95.49  4906.5   90.56
  4924.8    92.7 4929.22   84.79 4966.85   85.31 4994.24   79.87 5008.26   79.83
 5025.09   83.34 5026.82   91.21 5047.94   91.45 5049.22   96.75 5090.56   97.87
 5142.14    97.7 5223.62   93.93 5226.69   92.09 5228.93   94.28 5237.63   96.69
 5248.38   97.52  6522.1   97.47  6939.7  101.14  7042.1  101.81  7042.2  102.86
#Mann= 5 , 1 , 0
  2140.9     .99       0  4139.8      .1       0 4881.22    .035       0
 5090.56      .1       0  6939.7      .2       0
#XS Ineff= 2 , 0
       0    4819      99    5176       0     102
Permanent Ineff=
       F       F
Bank Sta=4881.22,5090.56
XS Rating Curve= 0 ,0
Exp/Cntr=0.5,0.3

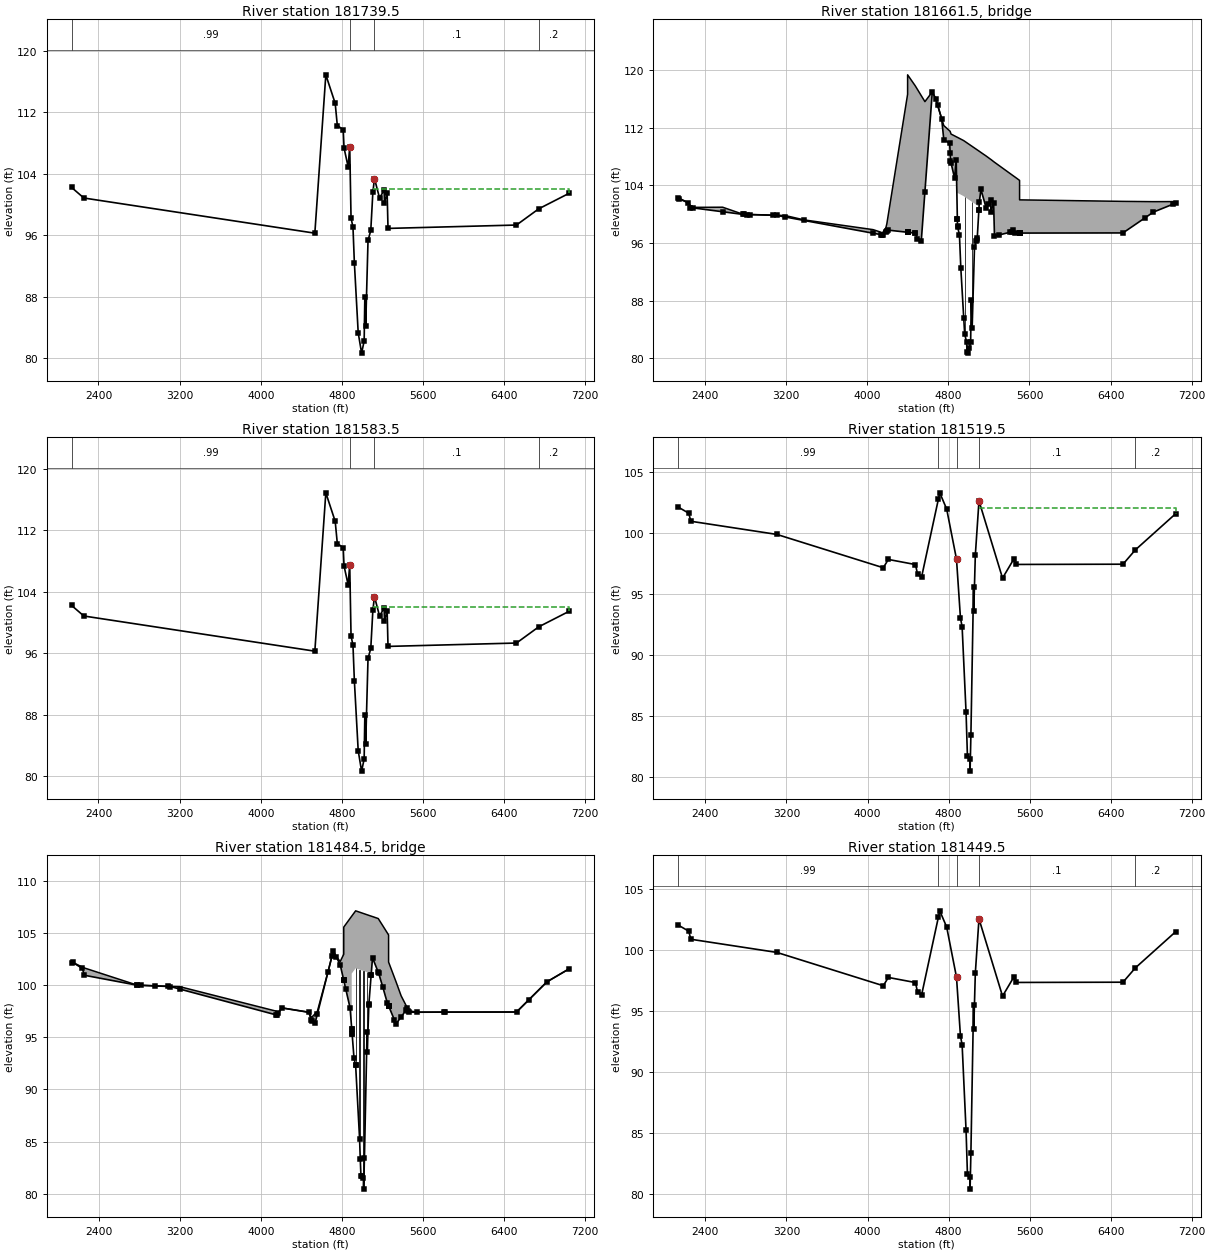
Type RM Length L Ch R = 1 ,181739.5,156,156,156
BEGIN DESCRIPTION:
Upstream Section of Bridge/Culvert/Weir
END DESCRIPTION:
XS GIS Cut Line= 5
      3091050.55     13906848.73      3090933.06     13905451.32
      3090991.37     13905452.44      3092471.53     13905555.22
       3094119.9      13904488.7
#Sta/Elev= 30
  2134.4  102.22  2255.7  100.84  4533.6   96.26 4641.86  116.88 4734.27  113.17
 4755.26  110.27 4813.31  109.75 4821.44  107.37  4861.7  104.91 4877.63  107.49
 4890.59   98.22 4909.57   97.06 4923.39    92.4 4961.15    83.3 4994.56   80.64
  5019.9   82.21 5026.62   87.97 5034.94   84.13 5058.05   95.32 5085.18   96.61
 5105.66  101.56 5121.47  103.36 5172.35  100.82 5216.83   101.9 5220.29  100.22
 5246.59  101.49 5255.17   96.88  6522.1   97.32  6741.4   99.43  7042.1  101.46
#Mann= 4 , 1 , 0
  2134.4     .99       0 4877.63    .035       0 5121.47      .1       0
  6741.4      .2       0
#XS Ineff= 2 , 0
       0    4900      96    5110       0     102
Permanent Ineff=
       F       F
Bank Sta=4877.63,5121.47
XS Rating Curve= 0 ,0
Exp/Cntr=0.5,0.3

Type RM Length L Ch R = 3 ,181661.5,,,
BEGIN DESCRIPTION:
HIGHWAY 8 - 50 degree skew
Structure ID: P00-68
END DESCRIPTION:
Bridge Culvert--1,0,-1,-1, 0
Deck Dist Width WeirC Skew NumUp NumDn MinLoCord MaxHiCord MaxSubmerge Is_Ogee
6.58,142.84,2.6,0, 54, 54, , , 0.95, 0, 1,1,,
  2134.4  2140.9  2235.7  2255.7  2284.4  2574.4  2775.7  3105.7  3193.2  3377.7
  4057.7  4137.7  4143.7  4155.7  4183.7  4193.7  4205.7 4398.39  4398.5  4473.6
  4493.6  4533.6  4569.2 4641.86 4675.01 4734.27 4755.26 4813.31    4818 4821.44
  4826.8  4861.7 4877.63 4889.06 4889.15  4951.8 5101.27 5101.38 5105.66 5121.47
 5172.35 5216.83 5220.29 5246.59 5255.17  5432.1  5442.1  5462.1  5502.6 5502.71
  6522.1  6822.1  7019.4  7042.1
  102.31  102.25   101.6  101.21  100.95  100.97   99.99   99.86   99.81   99.21
   97.86   97.49   97.26   97.51    98.1   98.67   99.72  116.64  119.34  117.82
  117.36  116.44  115.62  116.98  116.05  113.27   112.3  111.56   111.5  111.35
  111.12  110.87  110.75  110.67  110.67  110.21  108.77  108.77  108.73  108.57
  108.08  107.62  107.59   107.3  107.21  105.41  105.31  105.11  104.69  101.99
  101.78  101.74  101.75  101.55
   102.3  102.15  101.58  100.92  100.87  100.34   99.97   99.84   99.61   99.13
   97.36   97.16   97.14   97.11   97.49   97.63   97.79   97.49   97.49   97.37
    96.6   96.34  103.12  116.96  116.03  113.25  110.35  109.83  108.46  107.45
  107.12  104.99  107.57   99.39  102.96   102.5  101.06  100.61  101.64  103.44
   100.9  101.98   100.3  101.57   96.96   97.58   97.79   97.38   97.38   97.38
    97.4  100.29  101.41  101.54
  2134.4  2140.9  2235.7  2255.7  2284.4  2574.4  2775.7  3105.7  3193.2  3377.7
  4057.7  4137.7  4143.7  4155.7  4183.7  4193.7  4205.7 4398.39  4398.5  4473.6
  4493.6  4533.6  4569.2 4641.86 4675.01 4734.27 4755.26 4813.31    4818 4821.44
  4826.8  4861.7 4877.63 4889.06 4889.15  4951.8 5101.27 5101.38 5105.66 5121.47
 5172.35 5216.83 5220.29 5246.59 5255.17  5432.1  5442.1  5462.1  5502.6 5502.71
  6522.1  6822.1  7019.4  7042.1
  102.31  102.25   101.6  101.21  100.95  100.97   99.99   99.86   99.81   99.21
   97.86   97.49   97.26   97.51    98.1   98.67   99.72  116.64  119.34  117.82
  117.36  116.44  115.62  116.98  116.05  113.27   112.3  111.56   111.5  111.35
  111.12  110.87  110.75  110.67  110.67  110.21  108.77  108.77  108.73  108.57
  108.08  107.62  107.59   107.3  107.21  105.41  105.31  105.11  104.69  101.99
  101.78  101.74  101.75  101.55
  102.24  102.09  101.52  100.86  100.81  100.28   99.91   99.78   99.55   99.07
    97.3    97.1   97.08   97.05   97.43   97.57   97.73   97.43   97.43   97.31
   96.54   96.28  103.06   116.9  115.97  113.19  110.29  109.77   108.4  107.39
  107.06  104.93  107.51   99.33   102.9  102.44     101  100.55  101.58  103.38
  100.84  101.92  100.24  101.51    96.9   97.52   97.73   97.32   97.32   97.32
   97.34  100.23  101.35  101.48
Pier Skew, UpSta & Num, DnSta & Num=  ,4961.2, 2 ,4961.2, 2 , 0 , 0 , 0 ,,
       2       2
   82.29  103.42
       2       2
   82.23  103.36
Pier Skew, UpSta & Num, DnSta & Num=  ,5034.9, 2 ,5034.9, 2 , 0 , 0 , 0 ,,
       2       2
    83.9  102.71
       2       2
   83.84  102.65
Abutment Skew #Up #Dn= , 2 , 2
 4888.95 4890.69
  102.96   98.29
 4888.95 4890.69
   102.9   98.23
Abutment Skew #Up #Dn= , 2 , 2
 5080.06 5101.47
   96.45  101.06
 5080.06 5101.47
   96.39     101
BR Coef= 1 , 1 , 0 ,1.25, 0 ,,,0.8,0,2,0,
WSPro=,,,, 1 ,,,, 0 ,,,, 0 ,,,,-1 ,-1 ,-1 , 0 , 0 , 0 , 0 , 0
BR U #Sta/Elev= 84
  2134.4   102.3  2140.9  102.15  2235.7  101.58  2255.7  100.92  2284.4  100.87
  2574.4  100.34  2775.7   99.97  2784.4   99.97  2814.4   99.95  2844.4   99.94
  3074.4   99.85  3105.7   99.84  3193.2   99.61  3377.7   99.13  4057.7   97.36
  4137.7   97.16  4143.7   97.14  4155.7   97.11  4183.7   97.49  4193.7   97.63
  4205.7   97.79 4398.39   97.49  4398.5   97.49 4398.61   97.49  4398.7   97.49
  4467.8   97.38  4473.6   97.37  4493.6    96.6  4533.6   96.34  4569.2  103.12
 4641.86  116.96 4675.01  116.03    4694  115.14 4734.27  113.25 4755.26  110.35
 4813.31  109.83    4818  108.46 4821.44  107.45  4826.8  107.12  4861.7  104.99
 4877.63  107.57 4889.06   99.39 4889.15   99.33 4890.59    98.3 4890.69   98.29
 4909.57   97.14 4923.39   92.48  4951.8   85.63 4961.15   83.38 4980.03   82.25
 4984.96   80.89 4994.56   80.72 5008.51   81.48  5019.9   82.29 5026.62   88.05
 5034.94   84.21 5058.05    95.4  5077.6   96.33 5080.06   96.45 5085.18   96.69
 5101.27  100.58 5101.38  100.61 5105.66  101.64 5121.47  103.44 5172.35   100.9
  5191.9  101.37 5216.83  101.98 5220.29   100.3 5246.59  101.57 5255.17   96.96
  5301.1   97.12  5413.1   97.51  5432.1   97.58  5442.1   97.79  5462.1   97.38
  5502.4   97.38 5502.49   97.38  5502.6   97.38 5502.71   97.38  6522.1    97.4
  6741.4   99.51  6822.1  100.29  7019.4  101.41  7042.1  101.54
BR U #Mann= 4
  2134.4     .99 4877.63    .035 5121.47      .1  6741.4      .2
BR U Banks=4877.63,5121.47
BR D #Sta/Elev= 84
  2134.4  102.24  2140.9  102.09  2235.7  101.52  2255.7  100.86  2284.4  100.81
  2574.4  100.28  2775.7   99.91  2784.4   99.91  2814.4   99.89  2844.4   99.88
  3074.4   99.79  3105.7   99.78  3193.2   99.55  3377.7   99.07  4057.7    97.3
  4137.7    97.1  4143.7   97.08  4155.7   97.05  4183.7   97.43  4193.7   97.57
  4205.7   97.73 4398.39   97.43  4398.5   97.43 4398.61   97.43  4398.7   97.43
  4467.8   97.32  4473.6   97.31  4493.6   96.54  4533.6   96.28  4569.2  103.06
 4641.86   116.9 4675.01  115.97    4694  115.08 4734.27  113.19 4755.26  110.29
 4813.31  109.77    4818   108.4 4821.44  107.39  4826.8  107.06  4861.7  104.93
 4877.63  107.51 4889.06   99.33 4889.15   99.27 4890.59   98.24 4890.69   98.23
 4909.57   97.08 4923.39   92.42  4951.8   85.57 4961.15   83.32 4980.03   82.19
 4984.96   80.83 4994.56   80.66 5008.51   81.42  5019.9   82.23 5026.62   87.99
 5034.94   84.15 5058.05   95.34  5077.6   96.27 5080.06   96.39 5085.18   96.63
 5101.27  100.52 5101.38  100.55 5105.66  101.58 5121.47  103.38 5172.35  100.84
  5191.9  101.31 5216.83  101.92 5220.29  100.24 5246.59  101.51 5255.17    96.9
  5301.1   97.06  5413.1   97.45  5432.1   97.52  5442.1   97.73  5462.1   97.32
  5502.4   97.32 5502.49   97.32  5502.6   97.32 5502.71   97.32  6522.1   97.34
  6741.4   99.45  6822.1  100.23  7019.4  101.35  7042.1  101.48
BR D #Mann= 4
  2134.4     .99 4877.63    .035 5121.47      .1  6741.4      .2
BR D Banks=4877.63,5121.47
BC Design=,, 0 ,, 0 ,,,,,,
BC HTab HWMax=116.88
BC Use User HTab Curves=0
BC User HTab FreeFlow(D)= 0

Type RM Length L Ch R = 1 ,181583.5,64,64,64
BEGIN DESCRIPTION:
Downstream Section of Bridge/Culvert/Weir
END DESCRIPTION:
XS GIS Cut Line= 5
      3091151.46     13906967.69      3091033.96     13905570.28
      3091092.27      13905571.4      3092572.43     13905674.18
      3094220.81     13904607.66
#Sta/Elev= 30
  2134.4  102.21  2255.7  100.83  4533.6   96.25 4641.86  116.87 4734.27  113.16
 4755.26  110.26 4813.31  109.74 4821.44  107.36  4861.7   104.9 4877.63  107.48
 4890.59   98.21 4909.57   97.05 4923.39   92.39 4961.15   83.29 4994.56   80.63
  5019.9    82.2 5026.62   87.96 5034.94   84.12 5058.05   95.31 5085.18    96.6
 5105.66  101.55 5121.47  103.35 5172.35  100.81 5216.83  101.89 5220.29  100.21
 5246.59  101.48 5255.17   96.87  6522.1   97.31  6741.4   99.42  7042.1  101.45
#Mann= 4 , 1 , 0
  2134.4     .99       0 4877.63    .035       0 5121.47      .1       0
  6741.4      .2       0
#XS Ineff= 2 , 0
       0    4900      96    5110       0     102
Permanent Ineff=
       F       F
Bank Sta=4877.63,5121.47
XS Rating Curve= 0 ,0
Exp/Cntr=0.5,0.3

Type RM Length L Ch R = 1 ,181519.5,70,70,70
BEGIN DESCRIPTION:
Upstream Section of Bridge/Culvert/Weir
END DESCRIPTION:
XS GIS Cut Line= 5
      3091186.67     13907054.04      3091056.52      13905731.8
      3091091.85     13905650.47      3092699.43     13905726.73
      3094209.44     13904597.07
#Sta/Elev= 30
  2129.6  102.12  2235.7  101.61  2255.7  100.95  3105.7   99.87  4155.7   97.14
  4205.7   97.82  4473.6    97.4  4493.6   96.63  4533.6   96.37    4700  102.77
 4713.28  103.28 4781.57  101.95 4878.53   97.84 4917.57   93.02 4933.95   92.31
 4972.74   85.31 4986.37   81.71 5010.75    81.5 5012.61   80.47 5020.67   83.45
 5046.72   95.56  5048.7   93.56 5064.32   98.17 5100.42  102.62 5332.86   96.29
  5442.1   97.82  5462.1   97.41  6522.1   97.43  6643.6    98.6  7042.1  101.57
#Mann= 5 , 1 , 0
  2129.6     .99       0    4700      .1       0 4878.53    .035       0
 5100.42      .1       0  6643.6      .2       0
#XS Ineff= 2 , 0
       0    4882      97    5096       0     102
Permanent Ineff=
       F       F
Bank Sta=4878.53,5100.42
XS Rating Curve= 0 ,0
Exp/Cntr=0.5,0.3

Type RM Length L Ch R = 3 ,181484.5,,,
BEGIN DESCRIPTION:
SAM HOUSTON PARKWAY (HWY 8 WESTBOUND) - 50 degree skew
Structure ID: P00-67
END DESCRIPTION:
Bridge Culvert--1,0,-1,-1, 0
Deck Dist Width WeirC Skew NumUp NumDn MinLoCord MaxHiCord MaxSubmerge Is_Ogee
10,50,2.6,0, 43, 43, , , 0.95, 0, 1,1,,
  2129.6  2140.9  2235.7  2255.7  2775.7  3105.7    3197    4147  4155.7  4166.4
  4205.7  4473.6  4493.6  4502.6  4533.6  4555.7  4660.1 4713.28  4741.6 4781.57
 4816.29  4816.4 4878.53 4895.08 4895.17 4933.95 5087.25 5087.36 5100.42    5157
  5200.7 5245.38  5259.1 5259.21 5332.86    5383  5432.1  5442.1  5462.1  5537.3
  6522.1  6822.1  7042.1
   102.1  102.17  101.71  101.63   99.99   99.86   99.84    97.5    97.4   97.27
   97.81   97.39   96.94   96.93   97.24   97.46  101.22  103.27  102.72  102.25
  102.94  105.54  106.37  106.59  106.59   107.1  106.59  106.59  106.55  106.36
  105.69     105  104.79  102.19   100.3   98.96   98.03   97.84   97.53    97.4
   97.41   100.3  101.55
   102.1  102.16  101.59  100.93   99.98   99.85   99.61   97.14   97.12   97.27
    97.8   97.38   96.61   96.55   96.35    97.2  101.21  103.26  102.71  101.93
  100.46  100.45   97.82   95.81  101.09   101.6  101.09  100.99   102.6  101.22
   99.84   98.32      98      98   96.27   96.94   97.59    97.8   97.39   97.39
   97.41   100.3  101.55
  2129.6  2140.9  2235.7  2255.7  2775.7  3105.7    3197    4147  4155.7  4166.4
  4205.7  4473.6  4493.6  4502.6  4533.6  4555.7  4660.1 4713.28  4741.6 4781.57
 4816.29  4816.4 4878.53 4895.08 4895.17 4933.95 5087.25 5087.36 5100.42    5157
  5200.7 5245.38  5259.1 5259.21 5332.86    5383  5432.1  5442.1  5462.1  5537.3
  6522.1  6822.1  7042.1
   102.1  102.17  101.71  101.63   99.99   99.86   99.84    97.5    97.4   97.27
   97.81   97.39   96.94   96.93   97.24   97.46  101.22  103.27  102.72  102.25
  102.94  105.54  106.37  106.59  106.59   107.1  106.59  106.59  106.55  106.36
  105.69     105  104.79  102.19   100.3   98.96   98.03   97.84   97.53    97.4
   97.41   100.3  101.55
  102.05  102.11  101.54  100.88   99.93    99.8   99.56   97.09   97.07   97.22
   97.75   97.33   96.56    96.5    96.3   97.15  101.16  103.21  102.66  101.88
  100.41   100.4   97.77   95.76  101.04  101.55  101.04  100.94  102.55  101.17
   99.79   98.27   97.95   97.95   96.22   96.89   97.54   97.75   97.34   97.34
   97.36  100.25   101.5
Pier Skew, UpSta & Num, DnSta & Num=  ,4934, 2 ,4934, 2 , 0 , 0 , 0 ,,
       2       2
   91.11   102.6
       2       2
   91.06  102.55
Pier Skew, UpSta & Num, DnSta & Num=  ,4972.7, 2 ,4972.7, 2 , 0 , 0 , 0 ,,
       2       2
      84  102.47
       2       2
   83.95  102.42
Pier Skew, UpSta & Num, DnSta & Num=  ,5010.8, 2 ,5010.8, 2 , 0 , 0 , 0 ,,
       2       2
   79.93  102.34
       2       2
   79.88  102.29
Pier Skew, UpSta & Num, DnSta & Num=  ,5048.7, 2 ,5048.7, 2 , 0 , 0 , 0 ,,
       2       2
   92.84  102.22
       2       2
   92.79  102.17
Abutment Skew #Up #Dn= , 2 , 2
 4894.97 4899.46
  101.09   95.28
 4894.97 4899.46
  101.04   95.23
Abutment Skew #Up #Dn= , 2 , 2
 5064.32 5087.45
   98.15  101.09
 5064.32 5087.45
    98.1  101.04
BR Coef= 1 , 1 , 0 ,1.25, 0 ,,,0.8,0,2,0,
WSPro=,,,, 1 ,,,, 0 ,,,, 0 ,,,,-1 ,-1 ,-1 , 0 , 0 , 0 , 0 , 0
BR U #Sta/Elev= 73
  2129.6   102.1  2140.9  102.16  2235.7  101.59  2255.7  100.93  2775.7   99.98
  2779.6   99.98  2819.6   99.96  2949.6   99.91  3079.6   99.86  3105.7   99.85
    3197   99.61    4147   97.14  4155.7   97.12  4166.4   97.27  4205.7    97.8
  4473.6   97.38  4493.6   96.61  4502.6   96.55  4533.6   96.35  4555.7    97.2
  4660.1  101.21    4700  102.75 4713.28  103.26  4741.6  102.71 4781.57  101.93
 4816.29  100.46  4816.4  100.45 4816.51  100.45  4836.2   99.61 4878.53   97.82
 4895.08   95.81 4895.17    95.8 4899.36   95.29 4899.46   95.28 4917.57      93
    4933   92.33 4933.95   92.29 4972.74   85.29 4979.39   83.36 4986.37   81.69
 4998.66   81.75 5010.75   81.48 5012.61   80.45 5020.67   83.43 5046.72   95.54
  5048.7   93.54 5064.22   98.12 5064.32   98.15 5087.25  100.98 5087.36  100.99
 5100.42   102.6    5157  101.22 5161.92   101.1  5200.7   99.84 5245.38   98.32
 5258.99      98  5259.1      98 5259.21      98  5259.5   97.99  5314.8   96.69
 5332.86   96.27    5383   96.94  5432.1   97.59  5442.1    97.8  5454.2   97.55
  5462.1   97.39  5537.3   97.39  5809.4    97.4  5819.4    97.4  6522.1   97.41
  6643.6   98.58  6822.1   100.3  7042.1  101.55
BR U #Mann= 5
  2129.6     .99    4700      .1 4878.53    .035 5100.42      .1  6643.6      .2
BR U Banks=4878.53,5100.42
BR D #Sta/Elev= 73
  2129.6  102.05  2140.9  102.11  2235.7  101.54  2255.7  100.88  2775.7   99.93
  2779.6   99.93  2819.6   99.91  2949.6   99.86  3079.6   99.81  3105.7    99.8
    3197   99.56    4147   97.09  4155.7   97.07  4166.4   97.22  4205.7   97.75
  4473.6   97.33  4493.6   96.56  4502.6    96.5  4533.6    96.3  4555.7   97.15
  4660.1  101.16    4700   102.7 4713.28  103.21  4741.6  102.66 4781.57  101.88
 4816.29  100.41  4816.4   100.4 4816.51   100.4  4836.2   99.56 4878.53   97.77
 4895.08   95.76 4895.17   95.75 4899.36   95.24 4899.46   95.23 4917.57   92.95
    4933   92.28 4933.95   92.24 4972.74   85.24 4979.39   83.31 4986.37   81.64
 4998.66    81.7 5010.75   81.43 5012.61    80.4 5020.67   83.38 5046.72   95.49
  5048.7   93.49 5064.22   98.07 5064.32    98.1 5087.25  100.93 5087.36  100.94
 5100.42  102.55    5157  101.17 5161.92  101.05  5200.7   99.79 5245.38   98.27
 5258.99   97.95  5259.1   97.95 5259.21   97.95  5259.5   97.94  5314.8   96.64
 5332.86   96.22    5383   96.89  5432.1   97.54  5442.1   97.75  5454.2    97.5
  5462.1   97.34  5537.3   97.34  5809.4   97.35  5819.4   97.35  6522.1   97.36
  6643.6   98.53  6822.1  100.25  7042.1   101.5
BR D #Mann= 5
  2129.6     .99    4700      .1 4878.53    .035 5100.42      .1  6643.6      .2
BR D Banks=4878.53,5100.42
BC Design=,, 0 ,, 0 ,,,,,,
BC HTab HWMax=103.28
BC Use User HTab Curves=0
BC User HTab FreeFlow(D)= 0

Type RM Length L Ch R = 1 ,181449.5,491.9,491.9,491.9
BEGIN DESCRIPTION:
Downstream Section of Bridge/Culvert/Weir
END DESCRIPTION:
XS GIS Cut Line= 5
      3091237.51     13907102.16      3091107.36     13905779.92
      3091142.69     13905698.59      3092750.27     13905774.85
      3094260.28     13904645.18
#Sta/Elev= 30
  2129.6  102.04  2235.7  101.53  2255.7  100.87  3105.7   99.79  4155.7   97.06
  4205.7   97.74  4473.6   97.32  4493.6   96.55  4533.6   96.29    4700  102.69
 4713.28   103.2 4781.57  101.87 4878.53   97.76 4917.57   92.94 4933.95   92.23
 4972.74   85.23 4986.37   81.63 5010.75   81.42 5012.61   80.39 5020.67   83.37
 5046.72   95.48  5048.7   93.48 5064.32   98.09 5100.42  102.54 5332.86   96.21
  5442.1   97.74  5462.1   97.33  6522.1   97.35  6643.6   98.52  7042.1  101.49
#Mann= 5 , 1 , 0
  2129.6     .99       0    4700      .1       0 4878.53    .035       0
 5100.42      .1       0  6643.6      .2       0
#XS Ineff= 2 , 0
       0    4882    96.3    5096       0   100.5
Permanent Ineff=
       F       F
Bank Sta=4878.53,5100.42
XS Rating Curve= 0 ,0
Exp/Cntr=0.5,0.3

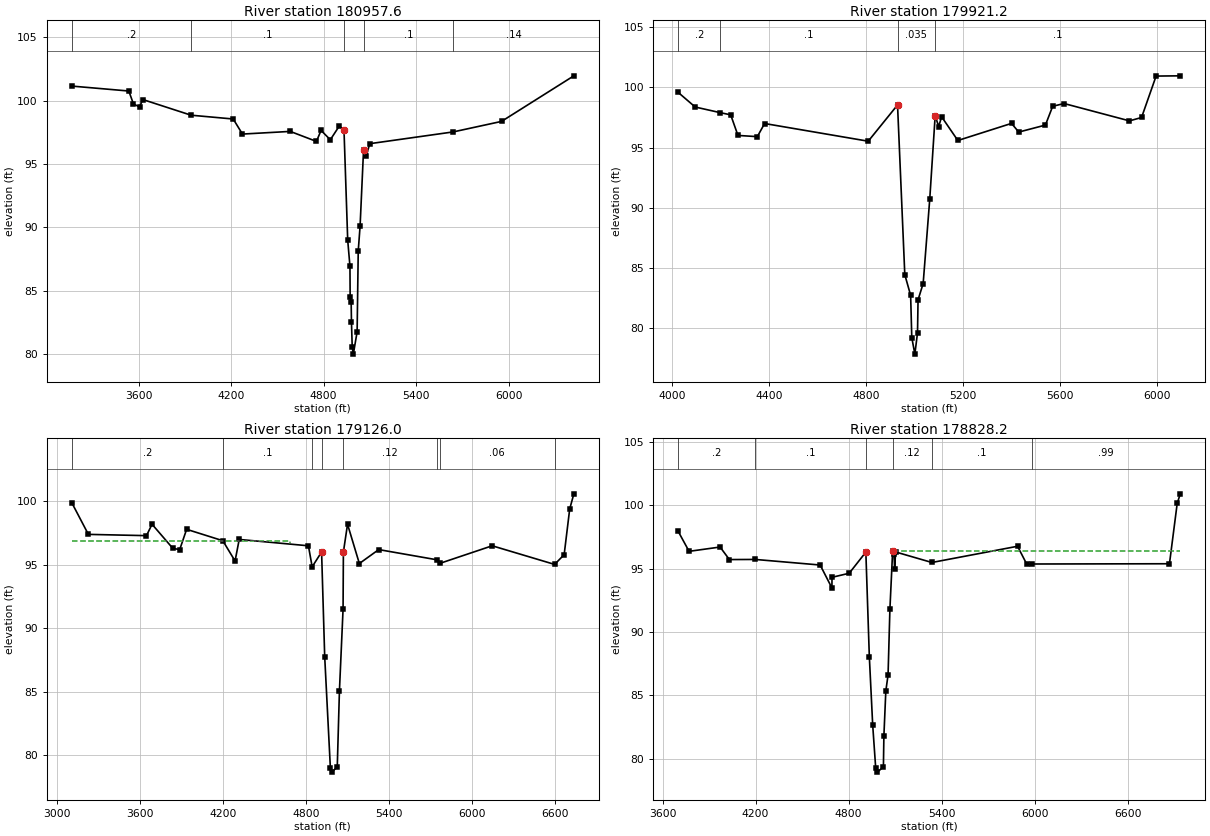
Type RM Length L Ch R = 1 ,180957.6,989.9,1036.4,1067.6
BEGIN DESCRIPTION:
Cross Section 180957.6
END DESCRIPTION:
XS GIS Cut Line= 6
      3091915.83       13907501.      3092510.91     13906985.75
      3092873.76      13906318.1      3093011.64     13905868.17
      3093170.05     13905660.39      3093928.22     13905043.07
#Sta/Elev= 30
  3166.3  101.16  3536.3  100.77  3566.3   99.75  3606.3   99.51  3626.3   100.1
  3940.3   98.86  4213.4   98.56  4273.4   97.37  4583.4   97.58  4753.3   96.79
  4783.3   97.66  4843.3   96.92  4900.7   97.99  4931.9   97.73  4956.1   88.99
  4970.7   86.92  4971.9   84.52  4978.5   84.09  4980.5   82.53  4985.4   80.53
  4992.6   79.99  5017.2   81.76  5024.4   88.14  5036.4    90.1  5058.9   96.13
  5076.8   95.65  5098.8   96.61  5640.4   97.54  5953.9   98.37  6422.9  101.97
#Mann= 5 , 1 , 0
  3166.3      .2       0  3940.3      .1       0  4931.9    .035       0
  5058.9      .1       0  5640.4     .14       0
#XS Ineff= 2 , 0
       0  4900.7   97.99               0
Permanent Ineff=
       F       F
Bank Sta=4931.9,5058.9
XS Rating Curve= 0 ,0
Exp/Cntr=0.3,0.1

Type RM Length L Ch R = 1 ,179921.2,768.6,795.2,995.2
BEGIN DESCRIPTION:
Cross Section 179921.2
END DESCRIPTION:
XS GIS Cut Line= 6
      3093155.14      13907425.2      3093229.35      13907348.6
      3093657.52     13906862.38      3093904.25     13906448.73
      3094063.91     13906129.42      3094058.09     13905649.53
#Sta/Elev= 30
  4024.2   99.58  4094.2   98.37    4198    97.9  4240.8   97.72  4270.8   96.01
  4350.8   95.91  4380.8      97  4808.7   95.53  4929.7   98.54  4959.7   84.45
  4983.8   82.73  4988.5   79.23  5001.2   77.85  5012.2   79.62  5014.4   82.36
  5035.5   83.71  5062.7   90.72  5085.1   97.65  5099.6   96.75  5111.7   97.56
  5178.7   95.59  5400.3   97.01  5430.3   96.29  5540.3   96.87  5570.3   98.43
  5617.3   98.66  5887.3   97.22  5937.3    97.5  5997.3  100.94  6097.3  100.96
#Mann= 4 , 1 , 0
  4024.2      .2       0    4198      .1       0  4929.7    .035       0
  5085.1      .1       0
#XS Ineff= 2 , 0
       0  4929.7   98.54  5111.7       0   97.56
Permanent Ineff=
       F       F
Bank Sta=4929.7,5085.1
XS Rating Curve= 0 ,0
Exp/Cntr=0.3,0.1

Type RM Length L Ch R = 1 ,179126.0,266.2,297.8,308.2
BEGIN DESCRIPTION:
Cross Section 179126.0-Interpolated
END DESCRIPTION:
XS GIS Cut Line= 4
      3093186.69     13908546.24      3094348.25     13907220.21
      3094493.39     13907022.29      3095564.74     13905807.22
#Sta/Elev= 30
  3106.3    99.9  3226.3    97.4  3646.3    97.3  3686.3    98.2  3836.3    96.3
  3886.3    96.2  3936.3    97.8  4197.8    96.9  4286.3    95.3  4316.3      97
  4816.3    96.5  4843.5   94.84  4911.6   96.01  4934.1   87.75    4975   78.99
  4986.3   78.64  5024.9   79.06  5040.5   85.05  5066.8    91.5  5069.1      96
  5099.1    98.2  5184.5    95.1  5324.5    96.2  5742.4    95.4  5765.6   95.11
  6144.5    96.5  6595.4   95.03  6664.5    95.8  6704.5    99.4  6734.5   100.6
#Mann= 8 , 1 , 0
  3106.3      .2       0  4197.8      .1       0  4843.5     .12       0
  4911.6     .04       0  5069.1     .12       0  5742.4      .1       0
  5765.6     .06       0  6595.4      .1       0
#XS Ineff= 2 , 0
       0  4686.3    96.9  5099.1       0    98.2
Permanent Ineff=
       F       F
Bank Sta=4911.6,5069.1
XS Rating Curve= 0 ,0
Exp/Cntr=0.5,0.3

Type RM Length L Ch R = 1 ,178828.2,50,50,50
BEGIN DESCRIPTION:
Upstream Section of Bridge/Culvert/Weir
END DESCRIPTION:
XS GIS Cut Line= 6
      3093904.63     13908317.39      3094337.27     13907747.22
      3094569.63     13907375.88      3094829.76     13907176.45
      3095196.82      13907043.5      3095925.56      13905893.3
#Sta/Elev= 30
  3701.2   97.93  3771.2   96.36  3971.2    96.7  4031.2   95.71  4198.1   95.72
  4616.8   95.28  4692.6   93.47  4693.3   94.31  4804.3   94.63  4911.6    96.3
  4934.1   88.04  4955.8   82.64    4975   79.28  4986.3   78.93  5024.9   79.35
    5028   81.79  5040.5   85.34  5054.9    86.6  5066.8   91.79  5084.4   96.37
  5093.3   96.14  5097.1   94.99  5103.7   96.31  5337.6   95.48  5890.4   96.76
  5950.4   95.33  5984.2   95.36  6870.4   95.38  6920.4  100.15  6940.4   100.9
#Mann= 6 , 1 , 0
  3701.2      .2       0  4198.1      .1       0  4911.6    .035       0
  5084.4     .12       0  5337.6      .1       0  5984.2     .99       0
#XS Ineff= 2 , 0
       0  4911.6    96.3  5084.4       0    96.4
Permanent Ineff=
       F       F
Bank Sta=4911.6,5084.4
XS Rating Curve= 0 ,0
Exp/Cntr=0.5,0.3