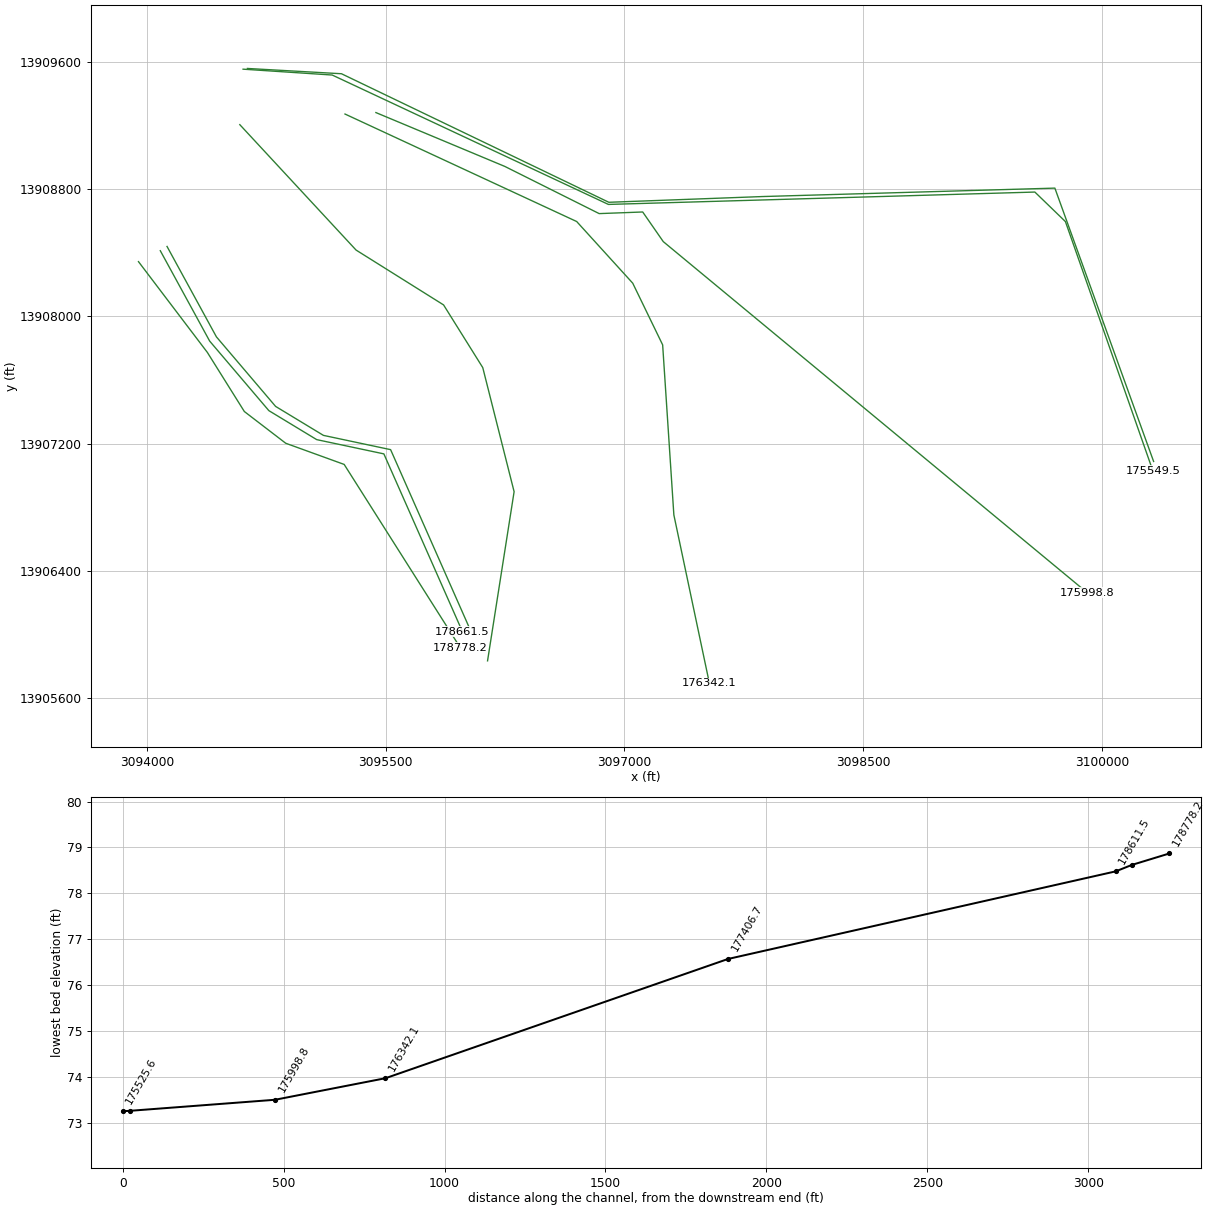
HEC-RAS study P100-00-00.prj: P100-00-00

--- P100-00-00.g01 (geometry) --- (continued)

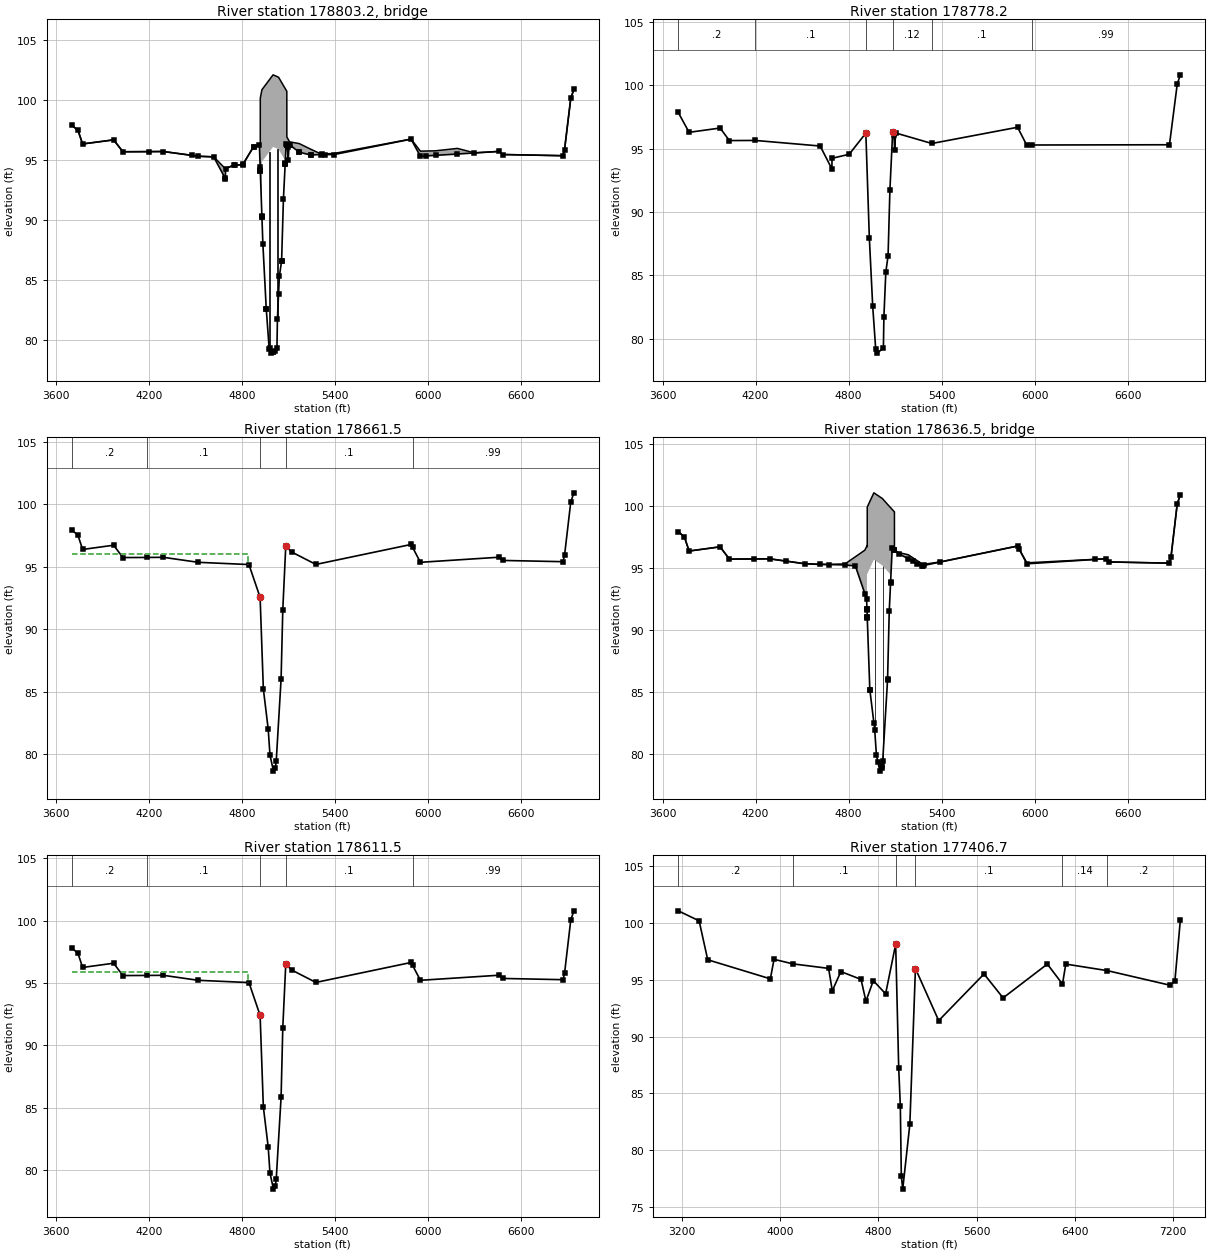
Type RM Length L Ch R = 3 ,178803.2,,,
BEGIN DESCRIPTION:
GREENS PARKWAY (SOUTHEAST)
Structure ID: P00-66
END DESCRIPTION:
Bridge Culvert--1,0,-1,-1, 0
Deck Dist Width WeirC Skew NumUp NumDn MinLoCord MaxHiCord MaxSubmerge Is_Ogee
10,30,2.6,0, 45, 45, , , 0.95, 0, 1,1,,
  3701.2  3741.2  3771.2  3971.2  4031.2    4292  4516.8  4616.8  4692.6  4693.3
    4749  4804.3  4873.7  4911.6  4916.6 4917.39  4917.5 4928.01  4928.1    5000
  5035.3 5077.99  5078.1  5084.4  5088.7 5088.81  5093.3  5097.1  5103.7  5106.2
  5168.9  5241.6  5308.3  5390.4  5890.4  5950.4  6048.8  6188.8  6298.8  6460.4
  6480.4  6870.4  6880.4  6920.4  6940.4
   97.94    97.5   96.37   96.71   95.72   95.74   95.35    95.3    94.3   94.33
   94.61   94.65   96.14   96.32   96.33   96.39  100.19  100.89  100.89  102.13
  101.93  100.99  100.99  100.85  100.75   96.95   96.85   96.76   96.61   96.55
    96.4   95.94   95.54   95.57   96.78   95.77    95.8      96   95.63   95.75
   95.49   95.39    95.9  100.16  100.91
   97.94    97.5   96.37   96.71   95.72   95.74   95.34   95.29   93.48   94.32
    94.6   94.64   96.13   96.31   94.47   94.18   94.14   90.29   94.89   96.13
   95.93   94.99   94.74   96.38   96.27   96.27   96.15      95   96.32    96.3
   95.68   95.45   95.49   95.48   96.77   95.34   95.42   95.53   95.62   95.75
   95.49   95.39    95.9  100.16  100.91
  3701.2  3741.2  3771.2  3971.2  4031.2    4292  4516.8  4616.8  4692.6  4693.3
    4749  4804.3  4873.7  4911.6  4916.6 4917.39  4917.5 4928.01  4928.1    5000
  5035.3 5077.99  5078.1  5084.4  5088.7 5088.81  5093.3  5097.1  5103.7  5106.2
  5168.9  5241.6  5308.3  5390.4  5890.4  5950.4  6048.8  6188.8  6298.8  6460.4
  6480.4  6870.4  6880.4  6920.4  6940.4
   97.94    97.5   96.37   96.71   95.72   95.74   95.35    95.3    94.3   94.33
   94.61   94.65   96.14   96.32   96.33   96.39  100.19  100.89  100.89  102.13
  101.93  100.99  100.99  100.85  100.75   96.95   96.85   96.76   96.61   96.55
    96.4   95.94   95.54   95.57   96.78   95.77    95.8      96   95.63   95.75
   95.49   95.39    95.9  100.16  100.91
   97.89   97.45   96.32   96.66   95.67   95.69   95.29   95.24   93.43   94.27
   94.55   94.59   96.08   96.26   94.42   94.13   94.09   90.24   94.84   96.08
   95.88   94.94   94.69   96.33   96.22   96.22    96.1   94.95   96.27   96.25
   95.63    95.4   95.44   95.43   96.72   95.29   95.37   95.48   95.57    95.7
   95.44   95.34   95.85  100.11  100.86
Pier Skew, UpSta & Num, DnSta & Num=  ,4977, 2 ,4977, 2 , 0 , 0 , 0 ,,
     1.4     1.4
   78.32   96.74
     1.4     1.4
   78.27   96.69
Pier Skew, UpSta & Num, DnSta & Num=  ,5028, 2 ,5028, 2 , 0 , 0 , 0 ,,
     1.4     1.4
   80.25   96.97
     1.4     1.4
    80.2   96.92
Abutment Skew #Up #Dn= , 2 , 2
  4927.9  4955.9
   94.89   82.63
  4927.9  4955.9
   94.84   82.58
Abutment Skew #Up #Dn= , 2 , 2
    5055 5078.19
   86.65   94.99
    5055 5078.19
    86.6   94.94
BR Coef= 1 , 1 , 0 ,1.25, 0 ,,,0.8,-1,2,0,
WSPro=,,,, 1 ,,,, 0 ,,,, 0 ,,,,-1 ,-1 ,-1 , 0 , 0 , 0 , 0 , 0
BR U #Sta/Elev= 74
  3701.2   97.94  3741.2    97.5  3771.2   96.37  3971.2   96.71  4031.2   95.72
  4198.1   95.73    4292   95.74  4479.9   95.41  4516.8   95.34  4616.8   95.29
  4691.6    93.5  4692.6   93.48  4693.3   94.32    4749    94.6  4751.2    94.6
  4804.3   94.64  4807.6   94.71  4873.7   96.13  4875.7   96.14  4911.6   96.31
  4916.6   94.47 4917.39   94.18  4917.5   94.14 4917.61    94.1  4927.9   90.33
 4928.01   90.29  4928.1   90.25  4934.1   88.05  4955.8   82.65  4955.9   82.63
    4975   79.29    4977   79.35  4986.3   78.94  4999.4   79.06    5000   79.06
  5015.5    79.1  5024.9   79.36    5028    81.8  5035.3   83.87  5040.5   85.35
  5054.9   86.61    5055   86.65  5066.8    91.8 5077.99   94.71  5078.1   94.74
  5078.2   94.77  5084.4   96.38 5088.59   96.27  5088.7   96.27 5088.81   96.27
  5093.3   96.15  5097.1      95  5103.7   96.32  5106.2    96.3  5168.9   95.68
  5169.7   95.68  5241.6   95.45  5244.7   95.45  5308.3   95.49  5318.6    95.5
  5337.6   95.49  5390.4   95.48  5890.4   96.77  5950.4   95.34  5984.2   95.37
  6048.8   95.42  6188.8   95.53  6298.8   95.62  6460.4   95.75  6480.4   95.49
  6870.4   95.39  6880.4    95.9  6920.4  100.16  6940.4  100.91
BR U #Mann= 6
  3701.2      .2  4198.1      .1  4911.6    .035  5084.4     .12  5337.6      .1
  5984.2     .99
BR U Banks=4911.6,5084.4
BR D #Sta/Elev= 74
  3701.2   97.89  3741.2   97.45  3771.2   96.32  3971.2   96.66  4031.2   95.67
  4198.1   95.68    4292   95.69  4479.9   95.36  4516.8   95.29  4616.8   95.24
  4691.6   93.45  4692.6   93.43  4693.3   94.27    4749   94.55  4751.2   94.55
  4804.3   94.59  4807.6   94.66  4873.7   96.08  4875.7   96.09  4911.6   96.26
  4916.6   94.42 4917.39   94.13  4917.5   94.09 4917.61   94.05  4927.9   90.28
 4928.01   90.24  4928.1    90.2  4934.1      88  4955.8    82.6  4955.9   82.58
    4975   79.24    4977    79.3  4986.3   78.89  4999.4   79.01    5000   79.01
  5015.5   79.05  5024.9   79.31    5028   81.75  5035.3   83.82  5040.5    85.3
  5054.9   86.56    5055    86.6  5066.8   91.75 5077.99   94.66  5078.1   94.69
  5078.2   94.72  5084.4   96.33 5088.59   96.22  5088.7   96.22 5088.81   96.22
  5093.3    96.1  5097.1   94.95  5103.7   96.27  5106.2   96.25  5168.9   95.63
  5169.7   95.63  5241.6    95.4  5244.7    95.4  5308.3   95.44  5318.6   95.45
  5337.6   95.44  5390.4   95.43  5890.4   96.72  5950.4   95.29  5984.2   95.32
  6048.8   95.37  6188.8   95.48  6298.8   95.57  6460.4    95.7  6480.4   95.44
  6870.4   95.34  6880.4   95.85  6920.4  100.11  6940.4  100.86
BR D #Mann= 6
  3701.2      .2  4198.1      .1  4911.6    .035  5084.4     .12  5337.6      .1
  5984.2     .99
BR D Banks=4911.6,5084.4
BC Design=,, 0 ,, 0 ,,,,,,
BC HTab HWMax=100.9
BC Use User HTab Curves=0
BC User HTab FreeFlow(D)= 0

Type RM Length L Ch R = 1 ,178778.2,116.7,116.7,116.7
BEGIN DESCRIPTION:
Downstream Section of Bridge/Culvert/Weir
END DESCRIPTION:
XS GIS Cut Line= 6
      3093947.39     13908343.31      3094380.03     13907773.14
      3094612.39      13907401.8      3094872.52     13907202.37
      3095239.58     13907069.42      3095968.31     13905919.23
#Sta/Elev= 30
  3701.2   97.87  3771.2    96.3  3971.2   96.64  4031.2   95.65  4198.1   95.66
  4616.8   95.22  4692.6   93.41  4693.3   94.25  4804.3   94.57  4911.6   96.24
  4934.1   87.98  4955.8   82.58    4975   79.22  4986.3   78.87  5024.9   79.29
    5028   81.73  5040.5   85.28  5054.9   86.54  5066.8   91.73  5084.4   96.31
  5093.3   96.08  5097.1   94.93  5103.7   96.25  5337.6   95.42  5890.4    96.7
  5950.4   95.27  5984.2    95.3  6870.4   95.32  6920.4  100.09  6940.4  100.84
#Mann= 6 , 1 , 0
  3701.2      .2       0  4198.1      .1       0  4911.6    .035       0
  5084.4     .12       0  5337.6      .1       0  5984.2     .99       0
#XS Ineff= 2 , 0
       0  4911.6    96.2  5084.4       0    96.3
Permanent Ineff=
       F       F
Bank Sta=4911.6,5084.4
XS Rating Curve= 0 ,0
Exp/Cntr=0.5,0.3

Type RM Length L Ch R = 1 ,178661.5,50,50,50
BEGIN DESCRIPTION:
Upstream Section of Bridge/Culvert/Weir
END DESCRIPTION:
XS GIS Cut Line= 6
      3094084.43     13908412.02      3094394.61      13907844.2
      3094766.39     13907407.32      3095066.98     13907225.24
      3095488.95     13907135.64      3095982.71      13906018.4
#Sta/Elev= 30
  3701.2   97.96  3741.2   97.52  3771.2   96.39  3971.2   96.73  4031.2   95.74
  4188.3   95.75    4292   95.76  4516.8   95.36  4844.2   95.18  4916.3   92.55
  4937.2   85.21  4968.6   81.98  4979.8   79.92  5002.5   78.62  5013.9   78.84
  5020.2    79.4  5051.6   85.98  5062.6   91.56  5081.7   96.63  5122.4   96.17
  5276.2   95.19  5890.4   96.79    5900   96.56  5950.4   95.36  6460.4   95.77
  6480.4   95.51  6870.4   95.41  6880.4   95.92  6920.4  100.18  6940.4  100.93
#Mann= 5 , 1 , 0
  3701.2      .2       0  4188.3      .1       0  4916.3    .035       0
  5081.7      .1       0    5900     .99       0
#XS Ineff= 2 , 0
       0    4840      96  5081.7       0   96.61
Permanent Ineff=
       F       F
Bank Sta=4916.3,5081.7
XS Rating Curve= 0 ,0
Exp/Cntr=0.5,0.3

Type RM Length L Ch R = 3 ,178636.5,,,
BEGIN DESCRIPTION:
GREENS PARKWAY (NORTHWEST)
Structure ID: P00-65
END DESCRIPTION:
Bridge Culvert--1,0,-1,-1, 0
Deck Dist Width WeirC Skew NumUp NumDn MinLoCord MaxHiCord MaxSubmerge Is_Ogee
10,30,2.6,0, 58, 58, , , 0.95, 0, 1,1,,
  3701.2  3741.2  3771.2  3971.2  4031.2  4188.3    4292  4398.8  4516.8  4616.8
  4672.6  4776.8  4844.2    4905  4916.3  4918.7 4918.81  4918.9 4920.49  4920.6
 4920.71  4937.2  4937.3  4963.3  4968.6  4979.8  4988.7  5002.5  5013.9  5016.3
  5020.2  5051.6  5051.7  5062.6 5071.19  5071.3  5081.7 5095.99  5096.1 5096.21
  5122.4  5185.2  5215.5  5244.8  5276.2  5279.2  5287.5  5390.4  5890.4    5900
  5950.4  6388.9  6460.4  6480.4  6870.4  6880.4  6920.4  6940.4
   97.94    97.5   96.37   96.71   95.72   95.73   95.74   95.56   95.35    95.3
   95.29   95.33   95.91   96.44   96.72   96.78   96.78   96.77   96.72   99.92
   99.92  100.37  100.37  101.07  101.03  100.93  100.86  100.74  100.65  100.63
  100.58  100.14  100.14   99.99   99.87   99.87   99.73   99.53   99.53   96.46
   96.25   96.07   95.82   95.58   95.32    95.3    95.3   95.49   96.78   96.55
   95.42    95.7   95.75   95.49   95.39    95.9  100.16  100.91
   97.94    97.5   96.37   96.71   95.72   95.73   95.74   95.55   95.34   95.29
   95.28   95.25   95.16   92.94   92.53   91.69   91.65   94.57   94.52   94.52
   94.52   94.97   94.97   95.67   95.63   95.53   95.46   95.34   95.25   95.23
   95.18   94.74   94.74   94.59   94.47   93.85   96.61   96.45   96.45   96.45
   96.15   95.75   95.56   95.29   95.17   95.18   95.21   95.48   96.77   96.54
   95.34   95.69   95.75   95.49   95.39    95.9  100.16  100.91
  3701.2  3741.2  3771.2  3971.2  4031.2  4188.3    4292  4398.8  4516.8  4616.8
  4672.6  4776.8  4844.2    4905  4916.3  4918.7 4918.81  4918.9 4920.49  4920.6
 4920.71  4937.2  4937.3  4963.3  4968.6  4979.8  4988.7  5002.5  5013.9  5016.3
  5020.2  5051.6  5051.7  5062.6 5071.19  5071.3  5081.7 5095.99  5096.1 5096.21
  5122.4  5185.2  5215.5  5244.8  5276.2  5279.2  5287.5  5390.4  5890.4    5900
  5950.4  6388.9  6460.4  6480.4  6870.4  6880.4  6920.4  6940.4
   97.94    97.5   96.37   96.71   95.72   95.73   95.74   95.56   95.35    95.3
   95.29   95.33   95.91   96.44   96.72   96.78   96.78   96.77   96.72   99.92
   99.92  100.37  100.37  101.07  101.03  100.93  100.86  100.74  100.65  100.63
  100.58  100.14  100.14   99.99   99.87   99.87   99.73   99.53   99.53   96.46
   96.25   96.07   95.82   95.58   95.32    95.3    95.3   95.49   96.78   96.55
   95.42    95.7   95.75   95.49   95.39    95.9  100.16  100.91
   97.84    97.4   96.27   96.61   95.62   95.63   95.64   95.45   95.24   95.19
   95.18   95.15   95.06   92.84   92.43   91.59   91.55   94.47   94.42   94.42
   94.42   94.87   94.87   95.57   95.53   95.43   95.36   95.24   95.15   95.13
   95.08   94.64   94.64   94.49   94.37   93.75   96.51   96.35   96.35   96.35
   96.05   95.65   95.46   95.19   95.07   95.08   95.11   95.38   96.67   96.44
   95.24   95.59   95.65   95.39   95.29    95.8  100.06  100.81
Pier Skew, UpSta & Num, DnSta & Num=  ,4968.6, 2 ,4968.6, 2 , 0 , 0 , 0 ,,
     1.4     1.4
   80.83   96.64
     1.4     1.4
   80.73   96.54
Pier Skew, UpSta & Num, DnSta & Num=  ,5020.2, 2 ,5020.2, 2 , 0 , 0 , 0 ,,
     1.4     1.4
   78.32   96.19
     1.4     1.4
   78.22   96.09
Abutment Skew #Up #Dn= , 2 , 2
  4918.7  4937.3
   94.57   85.18
  4918.7  4937.3
   94.47   85.08
Abutment Skew #Up #Dn= , 2 , 2
  5051.7 5071.39
   86.01   94.47
  5051.7 5071.39
   85.91   94.37
BR Coef= 1 , 1 , 0 ,1.25, 0 ,,,0.8,-1,2,0,
WSPro=,,,, 1 ,,,, 0 ,,,, 0 ,,,,-1 ,-1 ,-1 , 0 , 0 , 0 , 0 , 0
BR U #Sta/Elev= 58
  3701.2   97.94  3741.2    97.5  3771.2   96.37  3971.2   96.71  4031.2   95.72
  4188.3   95.73    4292   95.74  4398.8   95.55  4516.8   95.34  4616.8   95.29
  4672.6   95.28  4776.8   95.25  4844.2   95.16    4905   92.94  4916.3   92.53
  4918.7   91.69 4918.81   91.65  4918.9   91.62 4920.49   91.06  4920.6   91.02
 4920.71   90.98  4937.2   85.19  4937.3   85.18  4963.3   82.51  4968.6   81.96
  4979.8    79.9  4988.7   79.36  5002.5    78.6  5013.9   78.82  5016.3   79.03
  5020.2   79.38  5051.6   85.96  5051.7   86.01  5062.6   91.54 5071.19   93.82
  5071.3   93.85  5081.7   96.61 5095.99   96.45  5096.1   96.45 5096.21   96.45
  5122.4   96.15  5185.2   95.75  5215.5   95.56  5244.8   95.29  5276.2   95.17
  5279.2   95.18  5287.5   95.21  5390.4   95.48  5890.4   96.77    5900   96.54
  5950.4   95.34  6388.9   95.69  6460.4   95.75  6480.4   95.49  6870.4   95.39
  6880.4    95.9  6920.4  100.16  6940.4  100.91
BR U #Mann= 5
  3701.2      .2  4188.3      .1  4916.3    .035  5081.7      .1    5900     .99
BR U Banks=4916.3,5081.7
BR D #Sta/Elev= 58
  3701.2   97.84  3741.2    97.4  3771.2   96.27  3971.2   96.61  4031.2   95.62
  4188.3   95.63    4292   95.64  4398.8   95.45  4516.8   95.24  4616.8   95.19
  4672.6   95.18  4776.8   95.15  4844.2   95.06    4905   92.84  4916.3   92.43
  4918.7   91.59 4918.81   91.55  4918.9   91.52 4920.49   90.96  4920.6   90.92
 4920.71   90.88  4937.2   85.09  4937.3   85.08  4963.3   82.41  4968.6   81.86
  4979.8    79.8  4988.7   79.26  5002.5    78.5  5013.9   78.72  5016.3   78.93
  5020.2   79.28  5051.6   85.86  5051.7   85.91  5062.6   91.44 5071.19   93.72
  5071.3   93.75  5081.7   96.51 5095.99   96.35  5096.1   96.35 5096.21   96.35
  5122.4   96.05  5185.2   95.65  5215.5   95.46  5244.8   95.19  5276.2   95.07
  5279.2   95.08  5287.5   95.11  5390.4   95.38  5890.4   96.67    5900   96.44
  5950.4   95.24  6388.9   95.59  6460.4   95.65  6480.4   95.39  6870.4   95.29
  6880.4    95.8  6920.4  100.06  6940.4  100.81
BR D #Mann= 5
  3701.2      .2  4188.3      .1  4916.3    .035  5081.7      .1    5900     .99
BR D Banks=4916.3,5081.7
BC Design=,, 0 ,, 0 ,,,,,,
BC HTab HWMax=100.93
BC Use User HTab Curves=0
BC User HTab FreeFlow(D)= 0

Type RM Length L Ch R = 1 ,178611.5,1204.8,1204.8,1204.8
BEGIN DESCRIPTION:
Downstream Section of Bridge/Culvert/Weir
END DESCRIPTION:
XS GIS Cut Line= 6
      3094126.75     13908438.64      3094436.93     13907870.82
      3094808.71     13907433.94       3095109.3     13907251.86
      3095531.27     13907162.26      3096025.04     13906045.03
#Sta/Elev= 30
  3701.2   97.82  3741.2   97.38  3771.2   96.25  3971.2   96.59  4031.2    95.6
  4188.3   95.61    4292   95.62  4516.8   95.22  4844.2   95.04  4916.3   92.41
  4937.2   85.07  4968.6   81.84  4979.8   79.78  5002.5   78.48  5013.9    78.7
  5020.2   79.26  5051.6   85.84  5062.6   91.42  5081.7   96.49  5122.4   96.03
  5276.2   95.05  5890.4   96.65    5900   96.42  5950.4   95.22  6460.4   95.63
  6480.4   95.37  6870.4   95.27  6880.4   95.78  6920.4  100.04  6940.4  100.79
#Mann= 5 , 1 , 0
  3701.2      .2       0  4188.3      .1       0  4916.3    .035       0
  5081.7      .1       0    5900     .99       0
#XS Ineff= 2 , 0
       0    4840    95.9  5081.7       0   96.49
Permanent Ineff=
       F       F
Bank Sta=4916.3,5081.7
XS Rating Curve= 0 ,0
Exp/Cntr=0.5,0.3

Type RM Length L Ch R = 1 ,177406.7,1029.3,1064.6,1107.3
BEGIN DESCRIPTION:
Cross Section 177406.7
END DESCRIPTION:
XS GIS Cut Line= 6
      3094583.97     13909203.84      3095314.26     13908416.11
      3095864.03     13908071.48       3096110.2     13907677.61
      3096307.13     13906898.09       3096140.3     13905835.41
#Sta/Elev= 30
  3170.6  101.08  3340.6   100.2  3410.6   96.77  3920.6   95.09  3950.6   96.81
    4103   96.41  4394.8   96.01  4424.8   94.04  4494.8   95.73  4658.9   95.04
  4698.9   93.12  4758.9   94.93  4858.9   93.77  4940.9   98.13  4965.5   87.27
  4978.9   83.85  4986.8   77.71  4998.3   76.57  5056.3   82.29  5101.8      96
  5291.1   91.41  5660.3   95.52  5815.4   93.41  6175.7   96.39  6299.1   94.63
  6325.7   96.39  6664.9   95.81  7174.2   94.53  7214.2   94.91  7258.3  100.23
#Mann= 6 , 1 , 0
  3170.6      .2       0    4103      .1       0  4940.9    .035       0
  5101.8      .1       0  6299.1     .14       0  6664.9      .2       0
#XS Ineff= 2 , 0
       0  4494.8   95.73  5660.3       0   95.52
Permanent Ineff=
       F       F
Bank Sta=4940.9,5101.8
XS Rating Curve= 0 ,0
Exp/Cntr=0.3,0.1

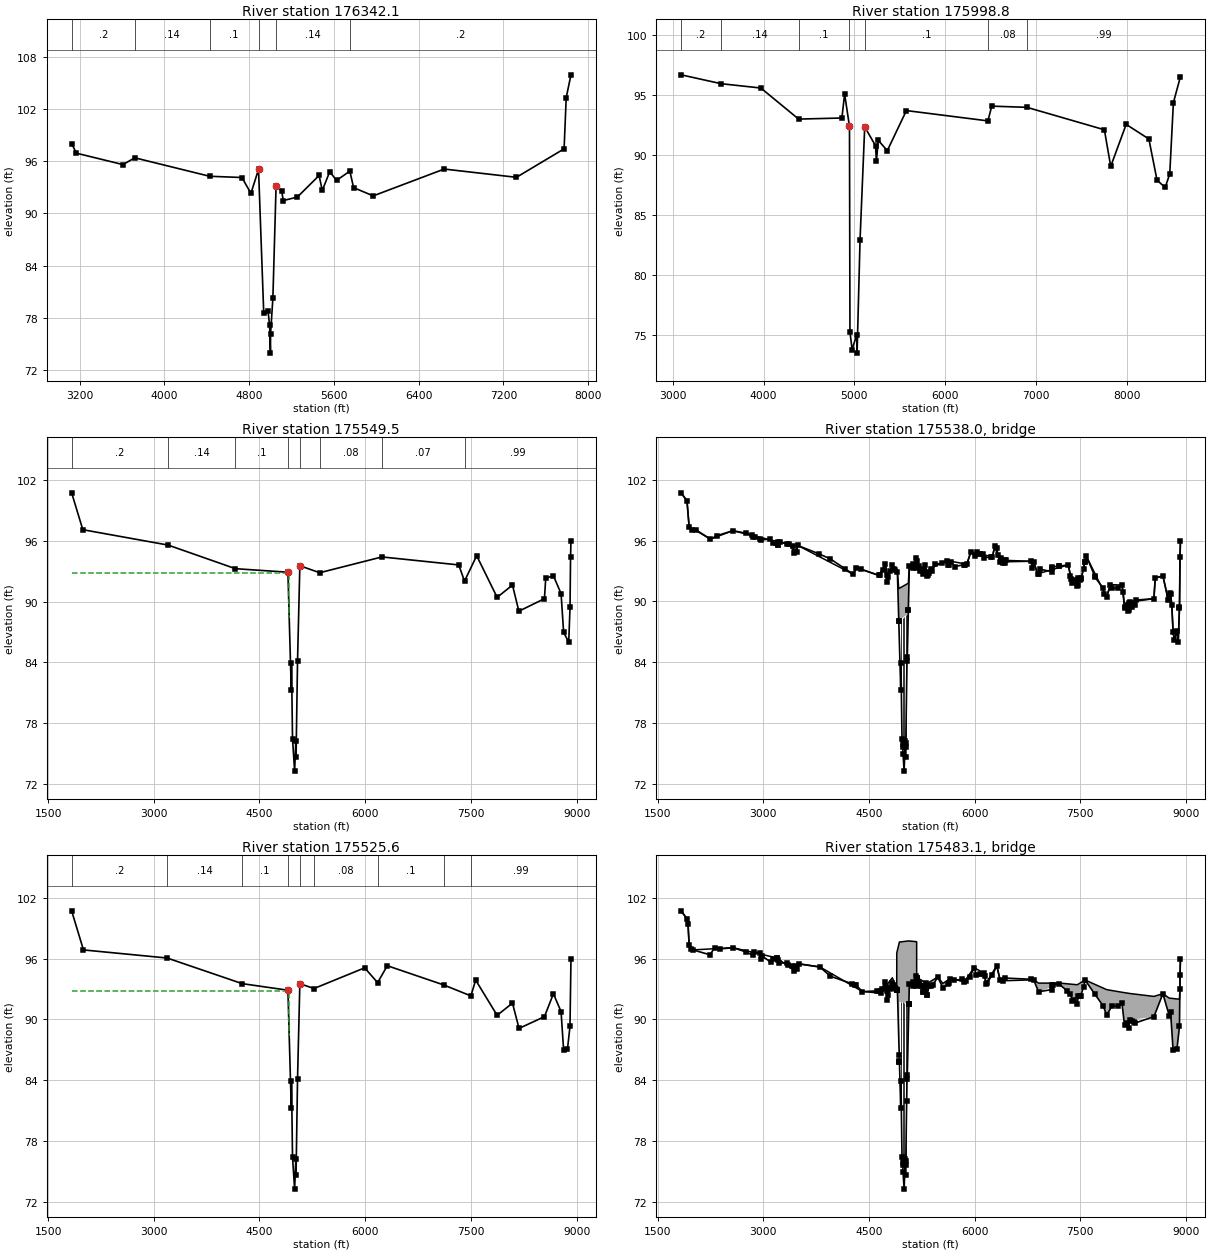
Type RM Length L Ch R = 1 ,176342.1,224.5,343.3,362.5
BEGIN DESCRIPTION:
Cross Section 176342.1
END DESCRIPTION:
XS GIS Cut Line= 6
       3095244.9     13909270.55      3096700.22     13908595.35
      3097052.44     13908207.91      3097240.29     13907820.47
      3097310.74     13906752.07      3097533.81     13905695.41
#Sta/Elev= 30
  3123.6   98.01  3168.6   96.91  3608.6    95.6  3719.6   96.38  4426.6   94.26
  4731.1   94.12  4816.1    92.3    4888   95.05  4936.9    78.6  4976.9   78.81
  4992.3   77.24  5000.4   73.97  5001.7    76.2  5023.4   80.29  5053.6   93.18
  5106.1   92.62  5121.1   91.47  5254.7   91.88  5459.7   94.35  5489.7   92.63
  5559.7   94.78  5624.7   93.79    5750   94.85  5785.3   92.96  5970.3   92.01
  6640.7   95.09  7322.5   94.14  7772.5   97.41  7792.5  103.29  7837.4   105.9
#Mann= 6 , 1 , 0
  3123.6      .2       0  3719.6     .14       0  4426.6      .1       0
    4888    .035       0  5053.6     .14       0    5750      .2       0
Bank Sta=4888,5053.6
XS Rating Curve= 0 ,0
Exp/Cntr=0.3,0.1

Type RM Length L Ch R = 1 ,175998.8,77.8,449.3,1136.1
BEGIN DESCRIPTION:
Cross Section 175998.8-Interpolated
END DESCRIPTION:
XS GIS Cut Line= 6
      3095438.95     13909279.75      3096249.25     13908941.26
      3096841.57      13908645.1      3097114.98     13908655.29
       3097244.2      13908469.1       3099907.3     13906263.86
#Sta/Elev= 30
  3092.2    96.7  3533.1   95.96  3970.4    95.6    4386   93.01  4862.6    93.1
  4892.6    95.1  4946.2    92.4 4951.45   75.26 4975.25    73.8 5024.35   75.01
 5029.95    73.5 5062.55   82.96 5113.85   92.36  5232.8   90.79  5242.8   89.48
  5262.8   91.24  5362.8   90.38  5572.8   93.72  6470.3   92.86  6512.8   94.09
  6899.9   93.99  7752.8   92.12  7822.8   89.07  7992.8   92.57  8242.8   91.35
  8332.8   87.91  8422.8   87.31  8472.8   88.45  8512.8   94.38  8590.5   96.55
#Mann= 7 ,-1 , 0
  3092.2      .2       0  3533.1     .14       0    4386      .1       0
  4946.2    .035       0 5113.85      .1       0  6470.3     .08       0
  6899.9     .99       0
Bank Sta=4946.2,5113.85
XS Rating Curve= 0 ,0
Exp/Cntr=0.5,0.3

Type RM Length L Ch R = 1 ,175549.5,23.9,23.9,23.9
BEGIN DESCRIPTION:
Upstream Section of Bridge/Culvert/Weir
END DESCRIPTION:
XS GIS Cut Line= 6
      3094604.43     13909552.46      3095164.47     13909515.63
      3096899.48     13908702.78       3099578.7     13908780.46
      3099770.61      13908594.9      3100320.28     13907028.13
#Sta/Elev= 30
  1834.8  100.74  1993.6    97.1  3204.2   95.58  4158.7   93.25 4903.71    92.9
 4951.01   81.29 4954.21   83.98 4968.93   76.44 4998.62   73.26 5015.58   76.19
 5019.17   74.68 5040.03   84.14 5072.86   93.54  5354.8   92.85  6237.5   94.41
  7327.8   93.62  7409.2   92.02  7581.8   94.53  7872.1   90.42  8089.8   91.63
  8180.5   89.05  8543.4   90.29  8561.5   92.31  8670.4   92.55  8779.3   90.79
  8815.6   86.96  8888.1      86  8906.3   89.44    8914   94.45  8919.8   96.01
#Mann= 8 ,-1 , 0
  1834.8      .2       0  3204.2     .14       0  4158.7      .1       0
 4903.71    .035       0 5072.86      .1       0  5354.8     .08       0
  6237.5     .07       0  7409.2     .99       0
#XS Ineff= 2 , 0
       0    4922    92.8    5076       0    92.3
Permanent Ineff=
       F       F
Bank Sta=4903.71,5072.86
XS Rating Curve= 0 ,0
Exp/Cntr=0.5,0.3

Type RM Length L Ch R = 3 ,175538.0,,,
BEGIN DESCRIPTION:
36" PIPELINE - 50 degree skew
Structure ID: PL1_PL64
END DESCRIPTION:
Bridge Culvert--1,0,-1,-1, 0
Deck Dist Width WeirC Skew NumUp NumDn MinLoCord MaxHiCord MaxSubmerge Is_Ogee
10,3,2.6,0, 60, 60, , , 0.95, 0, 1,1,,
  1834.8  1918.1  1948.3  2250.7  2567.9  3370.2  3442.3  3491.5  4279.7  4316.2
  4640.6  4734.5 4756.58  4832.1 4903.71 4923.33 5044.26 5058.87 5072.86 5168.16
 5169.89  5223.4  5262.1  5292.1  5322.1    5601  5888.6  5946.1  6252.7  6283.3
  6359.8  6799.5  6819.8  6837.9  6892.3  7327.8  7382.2  7454.8  7472.9  7509.2
  7581.8  7872.1  7926.5  8089.8  8126.1  8180.5  8198.7  8543.4  8561.5  8670.4
  8745.9  8779.3  8797.4  8815.6  8833.7    8870  8888.1  8906.3    8914  8919.8
  100.73   99.94    97.4   96.16   96.99   95.63   94.83   95.53   92.68   93.34
   92.58   93.73   91.96   93.58    92.9   91.27   91.75   91.81   93.54   93.33
   94.29   93.07   93.06   93.66   93.06   94.05   93.68   94.91   94.41   95.44
   93.91   93.97   93.27   93.91   92.73   93.61   91.86   91.55   92.35   92.25
   94.52   90.41   91.67   91.62   89.43   89.04   89.94   90.28    92.3   92.54
   90.18   90.78   89.61   86.95   86.23   87.07   85.99   89.43   94.44      96
  100.73   99.94    97.4   96.16   96.99   95.63   94.83   95.53   92.68   93.34
   92.58   93.73   91.96   93.58   92.89   88.07   88.75   89.12   93.53   93.32
   94.28   92.97   92.75   93.65   92.55   94.04   93.67    94.9   94.41   95.44
   93.91   93.97   93.27   93.91   92.73   93.61   91.86   91.55   92.35   92.25
   94.52   90.41   91.67   91.62   89.43   89.04   89.94   90.28    92.3   92.54
   90.18   90.78   89.61   86.95   86.23   87.07   85.99   89.43   94.44      96
  1834.8  1918.1  1948.3  2250.7  2567.9  3370.2  3442.3  3491.5  4279.7  4316.2
  4640.6  4734.5 4756.58  4832.1 4903.71 4923.33 5044.26 5058.87 5072.86 5168.16
 5169.89  5223.4  5262.1  5292.1  5322.1    5601  5888.6  5946.1  6252.7  6283.3
  6359.8  6799.5  6819.8  6837.9  6892.3  7327.8  7382.2  7454.8  7472.9  7509.2
  7581.8  7872.1  7926.5  8089.8  8126.1  8180.5  8198.7  8543.4  8561.5  8670.4
  8745.9  8779.3  8797.4  8815.6  8833.7    8870  8888.1  8906.3    8914  8919.8
  100.73   99.94    97.4   96.16   96.99   95.63   94.83   95.53   92.68   93.34
   92.58   93.73   91.96   93.58    92.9   91.27   91.75   91.81   93.54   93.33
   94.29   93.07   93.06   93.66   93.06   94.05   93.68   94.91   94.41   95.44
   93.91   93.97   93.27   93.91   92.73   93.61   91.86   91.55   92.35   92.25
   94.52   90.41   91.67   91.62   89.43   89.04   89.94   90.28    92.3   92.54
   90.18   90.78   89.61   86.95   86.23   87.07   85.99   89.43   94.44      96
  100.73   99.94    97.4   96.16   96.99   95.63   94.83   95.53   92.68   93.34
   92.58   93.73   91.96   93.58   92.89   88.07   88.75   89.12   93.53   93.32
   94.28   92.97   92.75   93.65   92.55   94.04   93.67    94.9   94.41   95.44
   93.91   93.97   93.27   93.91   92.73   93.61   91.86   91.55   92.35   92.25
   94.52   90.41   91.67   91.62   89.43   89.04   89.94   90.28    92.3   92.54
   90.18   90.78   89.61   86.95   86.23   87.07   85.99   89.43   94.44      96
Pier Skew, UpSta & Num, DnSta & Num=  ,4954.2, 2 ,4954.2, 2 , 0 , 0 , 0 ,,
     1.4     1.4
   82.38    89.4
     1.4     1.4
   82.38    89.4
Pier Skew, UpSta & Num, DnSta & Num=  ,4977.5, 2 ,4977.5, 2 , 0 , 0 , 0 ,,
     1.4     1.4
   74.79   89.49
     1.4     1.4
   74.79   89.49
Pier Skew, UpSta & Num, DnSta & Num=  ,4998.6, 2 ,4998.6, 2 , 0 , 0 , 0 ,,
     1.4     1.4
   72.33   89.57
     1.4     1.4
   72.33   89.57
Pier Skew, UpSta & Num, DnSta & Num=  ,5022.7, 2 ,5022.7, 2 , 0 , 0 , 0 ,,
     1.4     1.4
   74.92   89.67
     1.4     1.4
   74.92   89.67
Pier Skew, UpSta & Num, DnSta & Num=  ,5044.3, 2 ,5044.3, 2 , 0 , 0 , 0 ,,
     1.4     1.4
   83.45   89.77
     1.4     1.4
   83.45   89.77
BR Coef= 1 , 1 , 0 ,1.25, 0 ,,,0.8,0,2,0,
WSPro=,,,, 1 ,,,, 0 ,,,, 0 ,,,,-1 ,-1 ,-1 , 0 , 0 , 0 , 0 , 0
BR U #Sta/Elev= 175
  1834.8  100.73  1918.1   99.94  1948.3    97.4  1993.6   97.09    2039    97.1
  2250.7   96.16  2349.3   96.51  2567.9   96.99  2749.4   96.75  2842.3   96.54
  2853.6   96.35  2881.3    96.4  2955.7   96.16  2973.3   96.09  3102.6   96.15
    3138   95.76  3178.2   95.76  3204.2   95.57  3204.5   95.57  3215.8   95.86
  3244.2   95.86  3343.1   95.69  3370.2   95.63  3425.6   95.49  3442.3   94.83
  3472.3    94.9  3491.5   95.53  3788.4   94.71  3951.5   94.21  4158.7   93.24
  4279.7   92.68  4316.2   93.34  4392.9   93.18  4640.6   92.58  4661.7   92.66
  4703.2   93.13  4734.5   93.73  4751.8   92.65 4756.58   91.96 4763.36   92.38
 4800.42   92.97  4832.1   93.58 4861.35   93.25 4875.17    93.1 4903.71   92.89
 4923.33   88.07 4923.42   88.05 4951.01   81.28 4954.21   83.97 4968.93   76.43
  4977.5   75.89 4979.62    75.6 4984.16   74.97 4998.62   73.25 5015.58   76.18
 5019.17   74.67 5020.38   75.68 5022.69   76.03 5040.03   84.13 5044.26   84.51
 5058.87   89.12 5058.98   89.15 5072.86   93.53 5107.15   93.39  5130.4   93.29
 5131.23   93.66 5168.16   93.32 5169.89   94.28  5185.6   93.95 5207.26    93.5
  5223.4   92.97  5238.5   93.16  5262.1   92.75  5277.1   92.92  5292.1   93.65
  5322.1   92.55  5337.2   92.58  5354.8   92.84  5382.2   93.25  5397.4   93.02
  5440.4    93.7  5533.4   93.77    5601   94.04  5625.3   93.62  5640.6   93.56
  5666.8   93.87  5717.1   93.45  5845.1   93.63  5857.8   93.65  5888.6   93.67
  5946.1    94.9  6003.6   94.49  6038.4   94.87  6074.2   94.66  6074.3   94.66
  6114.9    94.7  6137.8   94.33  6237.5    94.4  6252.7   94.41  6283.3   95.44
  6313.9   95.31  6329.2   94.56  6359.8   93.91  6375.1    94.3  6405.7   93.81
  6425.4   93.82  6436.3   94.09  6449.8   94.05  6799.5   93.97  6819.8   93.27
  6837.9   93.91  6892.3   92.73  6906.2   92.74  6932.9   93.18  7091.9   92.95
    7101   93.26  7103.1    93.4  7199.5   93.51  7200.3   93.49  7327.8   93.61
  7359.5   92.54  7364.1   92.26  7382.2   91.86  7400.4   92.12  7409.2   92.01
  7416.2   91.92  7439.5   91.97  7454.8   91.55  7459.4   91.62  7472.9   92.35
  7492.8   92.15  7502.6   92.33  7509.2   92.25  7545.5   93.19  7563.7   93.88
  7567.3   93.89  7581.8   94.52  7706.1   92.49  7708.8   92.37  7826.5   91.31
  7839.4   90.73  7872.1   90.41  7926.5   91.67  7944.7    91.3  8035.4   91.32
  8089.8   91.62    8108   90.92  8126.1   89.43  8128.8   89.39  8162.4   89.62
  8180.5   89.04  8182.8   89.12  8193.6   89.81  8198.7   89.94  8212.7   89.68
  8225.9   89.86    8235   89.47  8271.2   89.64  8289.4   90.14  8543.4   90.28
  8561.5    92.3  8670.4   92.54  8745.9   90.18  8761.1   90.38  8772.6   90.81
  8779.3   90.78  8797.4   89.61  8815.6   86.95  8833.7   86.23    8870   87.07
  8888.1   85.99  8905.9   89.32  8906.3   89.43    8914   94.44  8919.8      96
BR U #Mann= 8
  1834.8      .2  3204.2     .14  4158.7      .1 4903.71    .035 5072.86      .1
  5354.8     .08  6237.5     .07  7409.2     .99
BR U Banks=4903.71,5072.86
BR D #Sta/Elev= 175
  1834.8  100.73  1918.1   99.94  1948.3    97.4  1993.6   97.09    2039    97.1
  2250.7   96.16  2349.3   96.51  2567.9   96.99  2749.4   96.75  2842.3   96.54
  2853.6   96.35  2881.3    96.4  2955.7   96.16  2973.3   96.09  3102.6   96.15
    3138   95.76  3178.2   95.76  3204.2   95.57  3204.5   95.57  3215.8   95.86
  3244.2   95.86  3343.1   95.69  3370.2   95.63  3425.6   95.49  3442.3   94.83
  3472.3    94.9  3491.5   95.53  3788.4   94.71  3951.5   94.21  4158.7   93.24
  4279.7   92.68  4316.2   93.34  4392.9   93.18  4640.6   92.58  4661.7   92.66
  4703.2   93.13  4734.5   93.73  4751.8   92.65 4756.58   91.96 4763.36   92.38
 4800.42   92.97  4832.1   93.58 4861.35   93.25 4875.17    93.1 4903.71   92.89
 4923.33   88.07 4923.42   88.05 4951.01   81.28 4954.21   83.97 4968.93   76.43
  4977.5   75.89 4979.62    75.6 4984.16   74.97 4998.62   73.25 5015.58   76.18
 5019.17   74.67 5020.38   75.68 5022.69   76.03 5040.03   84.13 5044.26   84.51
 5058.87   89.12 5058.98   89.15 5072.86   93.53 5107.15   93.39  5130.4   93.29
 5131.23   93.66 5168.16   93.32 5169.89   94.28  5185.6   93.95 5207.26    93.5
  5223.4   92.97  5238.5   93.16  5262.1   92.75  5277.1   92.92  5292.1   93.65
  5322.1   92.55  5337.2   92.58  5354.8   92.84  5382.2   93.25  5397.4   93.02
  5440.4    93.7  5533.4   93.77    5601   94.04  5625.3   93.62  5640.6   93.56
  5666.8   93.87  5717.1   93.45  5845.1   93.63  5857.8   93.65  5888.6   93.67
  5946.1    94.9  6003.6   94.49  6038.4   94.87  6074.2   94.66  6074.3   94.66
  6114.9    94.7  6137.8   94.33  6237.5    94.4  6252.7   94.41  6283.3   95.44
  6313.9   95.31  6329.2   94.56  6359.8   93.91  6375.1    94.3  6405.7   93.81
  6425.4   93.82  6436.3   94.09  6449.8   94.05  6799.5   93.97  6819.8   93.27
  6837.9   93.91  6892.3   92.73  6906.2   92.74  6932.9   93.18  7091.9   92.95
    7101   93.26  7103.1    93.4  7199.5   93.51  7200.3   93.49  7327.8   93.61
  7359.5   92.54  7364.1   92.26  7382.2   91.86  7400.4   92.12  7409.2   92.01
  7416.2   91.92  7439.5   91.97  7454.8   91.55  7459.4   91.62  7472.9   92.35
  7492.8   92.15  7502.6   92.33  7509.2   92.25  7545.5   93.19  7563.7   93.88
  7567.3   93.89  7581.8   94.52  7706.1   92.49  7708.8   92.37  7826.5   91.31
  7839.4   90.73  7872.1   90.41  7926.5   91.67  7944.7    91.3  8035.4   91.32
  8089.8   91.62    8108   90.92  8126.1   89.43  8128.8   89.39  8162.4   89.62
  8180.5   89.04  8182.8   89.12  8193.6   89.81  8198.7   89.94  8212.7   89.68
  8225.9   89.86    8235   89.47  8271.2   89.64  8289.4   90.14  8543.4   90.28
  8561.5    92.3  8670.4   92.54  8745.9   90.18  8761.1   90.38  8772.6   90.81
  8779.3   90.78  8797.4   89.61  8815.6   86.95  8833.7   86.23    8870   87.07
  8888.1   85.99  8905.9   89.32  8906.3   89.43    8914   94.44  8919.8      96
BR D #Mann= 8
  1834.8      .2  3204.2     .14  4158.7      .1 4903.71    .035 5072.86      .1
  5354.8     .08  6237.5     .07  7409.2     .99
BR D Banks=4903.71,5072.86
BC Design=,, 0 ,, 0 ,,,,,,
BC HTab HWMax=100.74
BC Use User HTab Curves=0
BC User HTab FreeFlow(D)= 0

Type RM Length L Ch R = 1 ,175525.6,85,85,85
BEGIN DESCRIPTION:
Upstream Section of Bridge/Culvert/Weir
END DESCRIPTION:
XS GIS Cut Line= 6
      3094631.65     13909556.95      3095222.61     13909523.76
       3096902.3      13908716.2      3097865.85     13908752.19
      3099704.26     13908805.21      3100324.62       13907088.
#Sta/Elev= 30
  1834.8  100.73  2002.5   96.87  3190.1   96.07    4255   93.54 4903.68   92.89
 4950.98   81.28 4954.18   83.97  4968.9   76.43 4998.59   73.25 5015.55   76.18
 5019.14   74.67    5040   84.13 5072.83   93.53  5274.7   93.06  5992.5    95.1
  6176.2   93.64  6313.9   95.31  7114.7   93.41  7499.7   92.33  7567.3   93.89
  7872.1   90.41  8089.8   91.62  8182.8   89.12  8543.4   90.28  8670.4   92.54
  8779.3   90.78  8815.6   86.95    8870   87.07  8905.9   89.32  8919.8      96
#Mann= 9 ,-1 , 0
  1834.8      .2       0  3190.1     .14       0    4255      .1       0
 4903.68    .035       0 5072.83      .1       0  5274.7     .08       0
  6176.2      .1       0  7114.7     .07       0  7499.7     .99       0
#XS Ineff= 2 , 0
       0    4922    92.8    5076       0    92.2
Permanent Ineff=
       F       F
Bank Sta=4903.68,5072.83
XS Rating Curve= 0 ,0
Exp/Cntr=0.5,0.3

Type RM Length L Ch R = 3 ,175483.1,,,
BEGIN DESCRIPTION:
GEARS ROAD - 50 degree skew
Structure ID: P00-63
END DESCRIPTION:
Bridge Culvert--1,0,-1,-1, 0
Deck Dist Width WeirC Skew NumUp NumDn MinLoCord MaxHiCord MaxSubmerge Is_Ogee
10,65,2.6,0, 60, 60, , , 0.95, 0, 1,1,,
  1834.8  1918.1  1933.1  1948.3  2002.5  2570.6  3193.1  3442.1  3514.5  3804.9
  4407.3  4671.9  4721.8 4756.54 4832.06  4894.3 4894.39  4894.5 4903.68 4932.26
 4932.35 5066.62 5072.83 5168.13 5169.86  5177.1 5177.21  5264.5  5307.1  5325.2
  5475.8  5548.8  5654.1  5854.8  5992.5  6130.2  6160.8  6313.9  6359.8  6405.7
  6837.9  6906.2  7200.3  7454.8  7567.3  7872.1  8089.8  8126.1  8182.8  8198.7
  8543.4  8670.4  8761.1  8779.3  8815.6    8870  8905.9  8911.7    8914  8919.8
  100.73   99.94   99.41    97.4   96.87   97.09   96.08   94.83   95.49   95.19
   92.76    92.6    93.7   93.45   94.12   93.03   93.04   96.54   96.83   97.65
   97.65   97.76   97.75   97.69   97.68   97.67   94.17    93.8   93.62   93.55
    94.2   93.56   94.04   93.76   95.11    94.6   93.57   95.32   93.92   93.82
   93.92   93.59    93.6   93.43    93.9   92.95   92.69   92.65   92.59   92.57
   92.28   92.55   92.11    92.1   92.07   92.03      92      93   94.44      96
  100.73   99.94   99.41    97.4   96.87   97.09   96.08   94.83   95.48   95.18
   92.75   92.59   93.69   91.96   93.58   92.96   92.96   92.96   92.89   85.87
   91.75   91.57   93.53   93.32   94.28   94.13   94.13   92.75   93.61   92.44
   94.19   93.14   94.03   93.75    95.1   94.59   93.49   95.31   93.91   93.81
   93.91   92.74   93.49   91.55   93.89   90.41   91.62   89.43   89.12   89.94
   90.28   92.54   90.38   90.78   86.95   87.07   89.32   92.99   94.44      96
  1834.8  1918.1  1933.1  1948.3  2002.5  2570.6  3193.1  3442.1  3514.5  3804.9
  4407.3  4671.9  4721.8 4756.54 4832.06  4894.3 4894.39  4894.5 4903.68 4932.26
 4932.35 5066.62 5072.83 5168.13 5169.86  5177.1 5177.21  5264.5  5307.1  5325.2
  5475.8  5548.8  5654.1  5854.8  5992.5  6130.2  6160.8  6313.9  6359.8  6405.7
  6837.9  6906.2  7200.3  7454.8  7567.3  7872.1  8089.8  8126.1  8182.8  8198.7
  8543.4  8670.4  8761.1  8779.3  8815.6    8870  8905.9  8911.7    8914  8919.8
  100.73   99.94   99.41    97.4   96.87   97.09   96.08   94.83   95.49   95.19
   92.76    92.6    93.7   93.45   94.12   93.03   93.04   96.54   96.83   97.65
   97.65   97.76   97.75   97.69   97.68   97.67   94.17    93.8   93.62   93.55
    94.2   93.56   94.04   93.76   95.11    94.6   93.57   95.32   93.92   93.82
   93.92   93.59    93.6   93.43    93.9   92.95   92.69   92.65   92.59   92.57
   92.28   92.55   92.11    92.1   92.07   92.03      92      93   94.44      96
  100.63   99.84   99.31    97.3   96.77   96.99   95.98   94.73   95.38   95.08
   92.65   92.49   93.59   91.86   93.48   92.86   92.86   92.86   92.79   85.77
   91.65   91.47   93.43   93.22   94.18   94.03   94.03   92.65   93.51   92.34
   94.09   93.04   93.93   93.65      95   94.49   93.39   95.21   93.81   93.71
   93.81   92.64   93.39   91.45   93.79   90.31   91.52   89.33   89.02   89.84
   90.18   92.44   90.28   90.68   86.85   86.97   89.22   92.89   94.34    95.9
Pier Skew, UpSta & Num, DnSta & Num=  ,4954.2, 2 ,4954.2, 2 , 0 , 0 , 0 ,,
     1.4     1.4
   82.38   92.78
     1.4     1.4
   82.28   92.68
Pier Skew, UpSta & Num, DnSta & Num=  ,4977.5, 2 ,4977.5, 2 , 0 , 0 , 0 ,,
     1.4     1.4
   74.79    92.8
     1.4     1.4
   74.69    92.7
Pier Skew, UpSta & Num, DnSta & Num=  ,4998.6, 2 ,4998.6, 2 , 0 , 0 , 0 ,,
     1.4     1.4
   72.33   92.83
     1.4     1.4
   72.23   92.73
Pier Skew, UpSta & Num, DnSta & Num=  ,5022.7, 2 ,5022.7, 2 , 0 , 0 , 0 ,,
     1.4     1.4
   74.92   92.86
     1.4     1.4
   74.82   92.76
Pier Skew, UpSta & Num, DnSta & Num=  ,5044.2, 2 ,5044.2, 2 , 0 , 0 , 0 ,,
     1.4     1.4
   83.45   92.87
     1.4     1.4
   83.35   92.77
BR Coef= 1 , 1 , 0 ,1.25, 0 ,,,0.8,-1,2,0,
WSPro=,,,, 1 ,,,, 0 ,,,, 0 ,,,,-1 ,-1 ,-1 , 0 , 0 , 0 , 0 , 0
BR U #Sta/Elev= 163
  1834.8  100.73  1918.1   99.94  1933.1   99.41  1948.3    97.4  1978.5   96.99
  2002.5   96.87  2244.7   96.39    2309   97.08  2389.3   96.97  2570.6   97.09
  2751.7   96.68  2848.3   96.36  2864.8   96.69  2947.3   96.56  2963.8      96
  2978.1   96.29  3112.2   95.64  3145.2   95.97  3190.1   96.07  3193.1   96.08
  3211.2   95.85  3227.7   95.54  3340.3   95.62  3351.6   95.37  3411.5   95.24
  3442.1   94.83  3458.6   95.28  3466.7   95.17  3478.4      95  3514.5   95.48
  3804.9   95.18  3953.4   94.27    4255   93.54  4308.2   93.41  4318.9   93.39
  4407.3   92.75  4617.4   92.83  4656.2   92.84  4671.9   92.59  4689.3   92.97
  4721.8   93.69  4737.4   93.22  4750.2   92.84 4756.54   91.96 4763.33   92.38
 4800.38   92.97  4806.9    93.1 4832.06   93.58  4849.2   93.39 4875.14    93.1
  4883.4   93.04  4894.3   92.96 4894.39   92.96  4894.5   92.96 4894.61   92.96
 4903.68   92.89  4929.6   86.53 4932.26   85.87 4932.35   85.85 4932.42   85.84
 4950.98   81.28 4954.18   83.97  4968.9   76.43 4977.47   75.89 4979.58    75.6
 4984.13   74.97 4998.59   73.25 5015.55   76.18 5019.14   74.67 5020.35   75.68
 5022.66   76.03  5035.4   81.98    5040   84.13 5044.22   84.51 5066.46   91.52
 5066.51   91.54 5066.62   91.57 5072.83   93.53 5130.37   93.29  5131.2   93.66
  5150.5   93.48 5168.13   93.32 5169.86   94.28 5176.99   94.13  5177.1   94.13
 5177.21   94.13  5203.3   93.58 5207.23    93.5  5232.1   93.34  5247.1   93.27
  5264.3   92.76  5264.5   92.75  5274.7   93.06  5282.8    93.3  5307.1   93.61
  5325.2   92.44  5325.8    92.4  5352.2   93.32  5383.1   93.28  5412.2   93.45
  5475.8   94.19  5548.8   93.14  5620.2   93.47  5639.4    93.6  5654.1   94.03
    5705   93.88  5824.2   93.95  5854.8   93.75  5870.1   93.84  5931.3   94.21
  5992.5    95.1  6023.1   94.42    6069   94.54  6100.3   94.46  6130.2   94.59
  6145.5   94.26  6160.8   93.49  6176.2   93.64  6252.7   94.41  6313.9   95.31
  6359.8   93.91  6405.7   93.81  6436.3   94.09  6799.5   93.97  6837.9   93.91
  6906.2   92.74  7091.9   92.95  7103.1    93.4  7114.7   93.41  7200.3   93.49
  7312.8   92.82  7359.5   92.54  7382.2   91.86  7416.2   91.92  7454.8   91.55
  7472.9   92.35  7499.7   92.33  7502.6   92.33  7545.5   93.19  7567.3   93.89
  7706.1   92.49  7826.5   91.31  7872.1   90.41  7944.7    91.3  8035.4   91.32
  8089.8   91.62  8126.1   89.43  8162.4   89.62  8182.8   89.12  8198.7   89.94
  8225.9   89.86  8256.7   89.71  8271.2   89.64  8543.4   90.28  8670.4   92.54
  8761.1   90.38  8779.3   90.78  8815.6   86.95    8870   87.07  8905.9   89.32
  8911.7   92.99    8914   94.44  8919.8      96
BR U #Mann= 9
  1834.8      .2  3190.1     .14    4255      .1 4903.68    .035 5072.83      .1
  5274.7     .08  6176.2      .1  7114.7     .07  7499.7     .99
BR U Banks=4903.68,5072.83
BR D #Sta/Elev= 163
  1834.8  100.63  1918.1   99.84  1933.1   99.31  1948.3    97.3  1978.5   96.89
  2002.5   96.77  2244.7   96.29    2309   96.98  2389.3   96.87  2570.6   96.99
  2751.7   96.58  2848.3   96.26  2864.8   96.59  2947.3   96.46  2963.8    95.9
  2978.1   96.19  3112.2   95.54  3145.2   95.87  3190.1   95.97  3193.1   95.98
  3211.2   95.75  3227.7   95.44  3340.3   95.52  3351.6   95.27  3411.5   95.14
  3442.1   94.73  3458.6   95.18  3466.7   95.07  3478.4    94.9  3514.5   95.38
  3804.9   95.08  3953.4   94.17    4255   93.44  4308.2   93.31  4318.9   93.29
  4407.3   92.65  4617.4   92.73  4656.2   92.74  4671.9   92.49  4689.3   92.87
  4721.8   93.59  4737.4   93.12  4750.2   92.74 4756.54   91.86 4763.33   92.28
 4800.38   92.87  4806.9      93 4832.06   93.48  4849.2   93.29 4875.14      93
  4883.4   92.94  4894.3   92.86 4894.39   92.86  4894.5   92.86 4894.61   92.86
 4903.68   92.79  4929.6   86.43 4932.26   85.77 4932.35   85.75 4932.42   85.74
 4950.98   81.18 4954.18   83.87  4968.9   76.33 4977.47   75.79 4979.58    75.5
 4984.13   74.87 4998.59   73.15 5015.55   76.08 5019.14   74.57 5020.35   75.58
 5022.66   75.93  5035.4   81.88    5040   84.03 5044.22   84.41 5066.46   91.42
 5066.51   91.44 5066.62   91.47 5072.83   93.43 5130.37   93.19  5131.2   93.56
  5150.5   93.38 5168.13   93.22 5169.86   94.18 5176.99   94.03  5177.1   94.03
 5177.21   94.03  5203.3   93.48 5207.23    93.4  5232.1   93.24  5247.1   93.17
  5264.3   92.66  5264.5   92.65  5274.7   92.96  5282.8    93.2  5307.1   93.51
  5325.2   92.34  5325.8    92.3  5352.2   93.22  5383.1   93.18  5412.2   93.35
  5475.8   94.09  5548.8   93.04  5620.2   93.37  5639.4    93.5  5654.1   93.93
    5705   93.78  5824.2   93.85  5854.8   93.65  5870.1   93.74  5931.3   94.11
  5992.5      95  6023.1   94.32    6069   94.44  6100.3   94.36  6130.2   94.49
  6145.5   94.16  6160.8   93.39  6176.2   93.54  6252.7   94.31  6313.9   95.21
  6359.8   93.81  6405.7   93.71  6436.3   93.99  6799.5   93.87  6837.9   93.81
  6906.2   92.64  7091.9   92.85  7103.1    93.3  7114.7   93.31  7200.3   93.39
  7312.8   92.72  7359.5   92.44  7382.2   91.76  7416.2   91.82  7454.8   91.45
  7472.9   92.25  7499.7   92.23  7502.6   92.23  7545.5   93.09  7567.3   93.79
  7706.1   92.39  7826.5   91.21  7872.1   90.31  7944.7    91.2  8035.4   91.22
  8089.8   91.52  8126.1   89.33  8162.4   89.52  8182.8   89.02  8198.7   89.84
  8225.9   89.76  8256.7   89.61  8271.2   89.54  8543.4   90.18  8670.4   92.44
  8761.1   90.28  8779.3   90.68  8815.6   86.85    8870   86.97  8905.9   89.22
  8911.7   92.89    8914   94.34  8919.8    95.9
BR D #Mann= 9
  1834.8      .2  3190.1     .14    4255      .1 4903.68    .035 5072.83      .1
  5274.7     .08  6176.2      .1  7114.7     .07  7499.7     .99
BR D Banks=4903.68,5072.83
BC Design=,, 0 ,, 0 ,,,,,,
BC HTab HWMax=100.73
BC Use User HTab Curves=0
BC User HTab FreeFlow(D)= 0