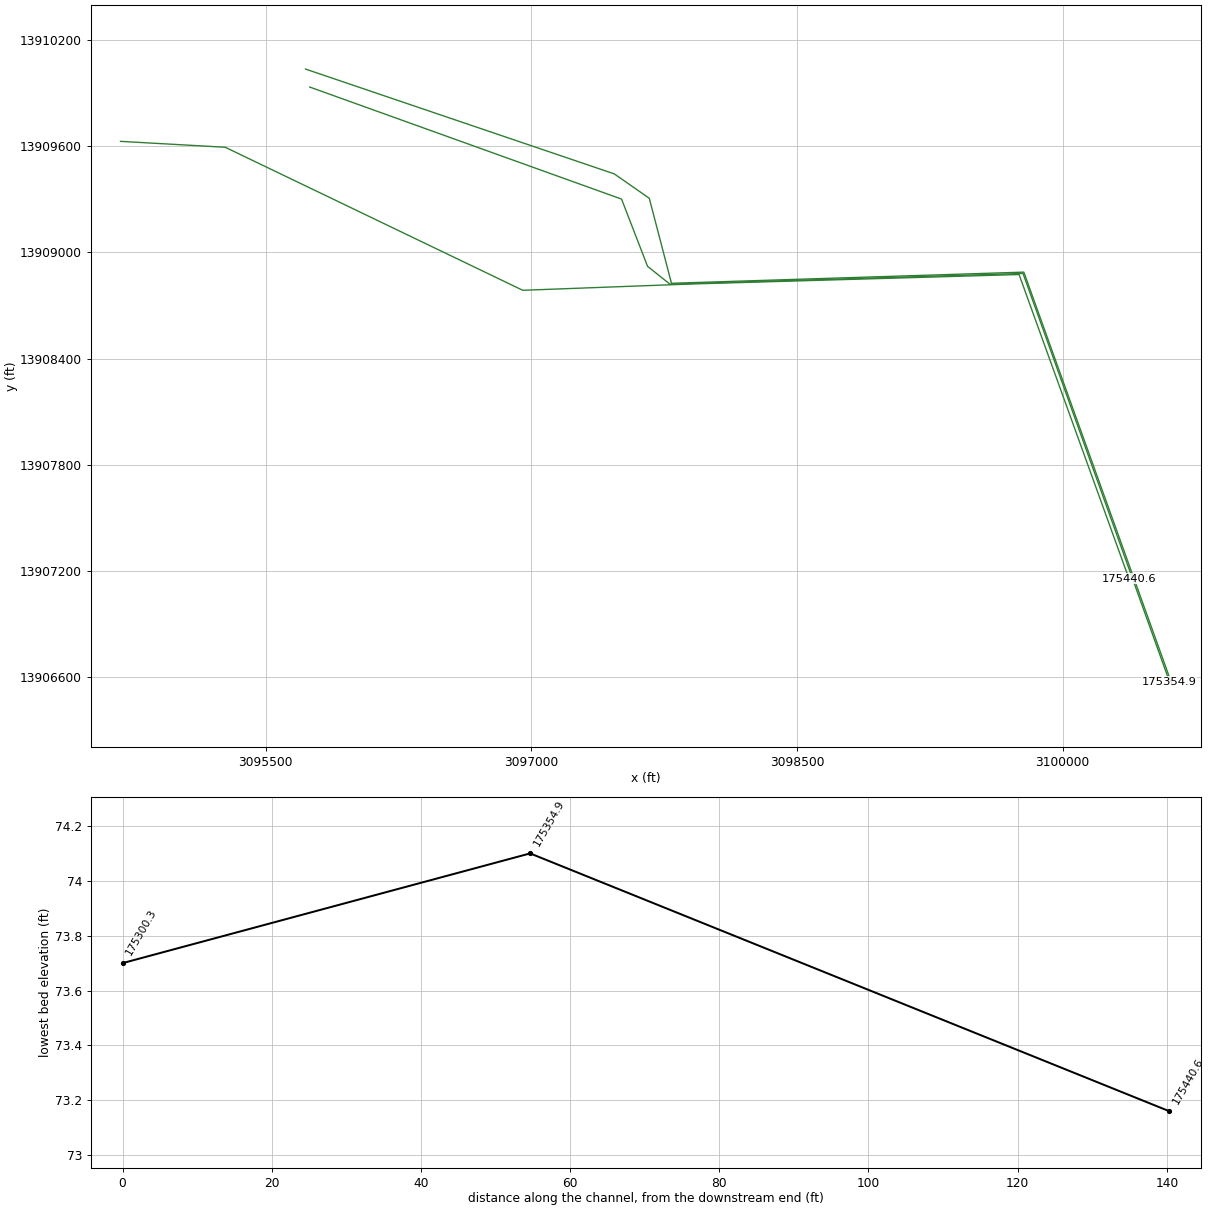
HEC-RAS study P100-00-00.prj: P100-00-00

--- P100-00-00.g01 (geometry) --- (continued)

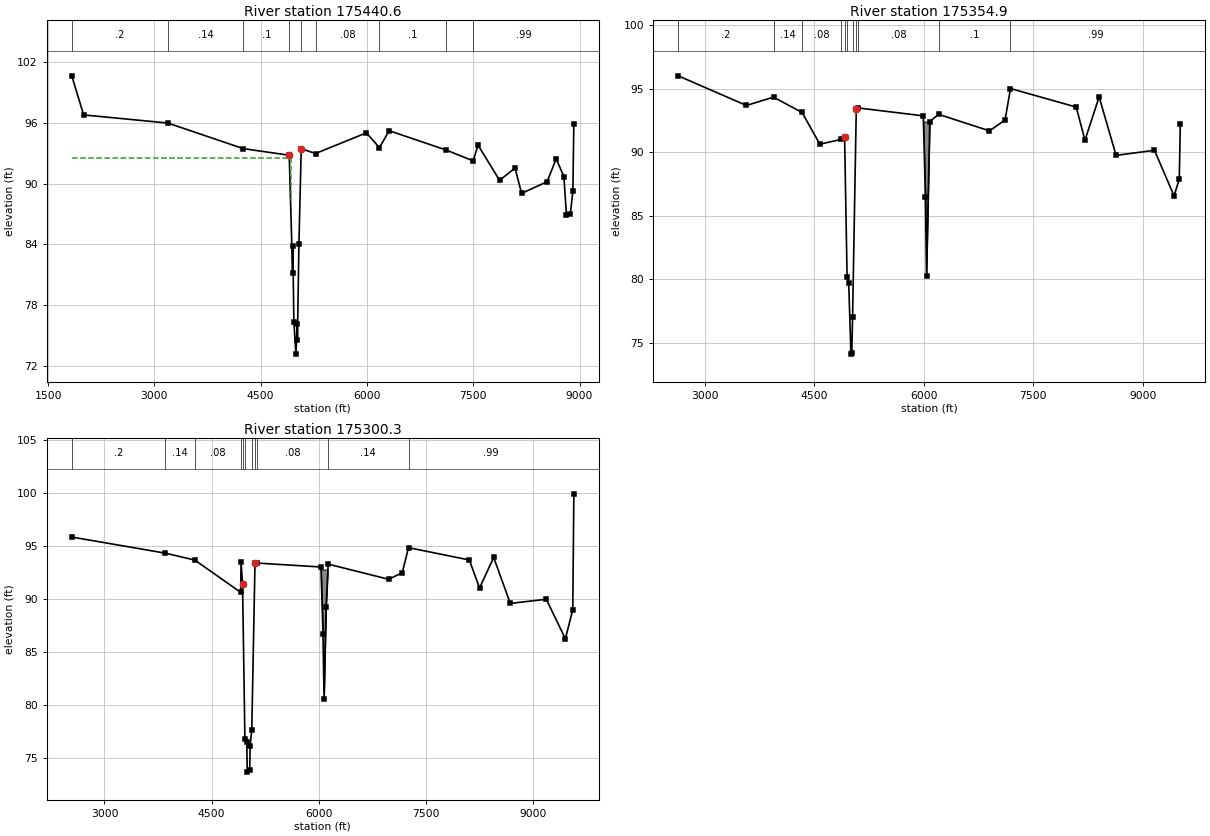
Type RM Length L Ch R = 1 ,175440.6,475.6,85.7,3.2
BEGIN DESCRIPTION:
Downstream Section of Bridge/Culvert/Weir
END DESCRIPTION:
XS GIS Cut Line= 6
      3094681.16     13909626.04      3095272.13     13909592.84
      3096951.82     13908785.28      3097915.37     13908821.27
      3099753.78     13908874.29      3100374.13     13907157.09
#Sta/Elev= 30
  1834.8  100.64  2002.5   96.78  3190.1   95.98    4255   93.45 4903.68    92.8
 4950.98   81.19 4954.18   83.88  4968.9   76.34 4998.59   73.16 5015.55   76.09
 5019.14   74.58    5040   84.04 5072.83   93.44  5274.7   92.97  5992.5   95.01
  6176.2   93.55  6313.9   95.22  7114.7   93.32  7499.7   92.24  7567.3    93.8
  7872.1   90.32  8089.8   91.53  8182.8   89.03  8543.4   90.19  8670.4   92.45
  8779.3   90.69  8815.6   86.86    8870   86.98  8905.9   89.23  8919.8   95.91
#Mann= 9 ,-1 , 0
  1834.8      .2       0  3190.1     .14       0    4255      .1       0
 4903.68    .035       0 5072.83      .1       0  5274.7     .08       0
  6176.2      .1       0  7114.7     .07       0  7499.7     .99       0
#XS Ineff= 2 , 0
       0    4922    92.5    5076       0    92.1
Permanent Ineff=
       F       F
Bank Sta=4903.68,5072.83
XS Rating Curve= 0 ,0
Exp/Cntr=0.5,0.3

Type RM Length L Ch R = 1 ,175354.9,148.7,54.64,4.03
BEGIN DESCRIPTION:
EHRA Imported Cross Section 175354.9 (April 2011 LOMR)
END DESCRIPTION:
XS GIS Cut Line= 6
 3095749.720205113909932.4941559 3097509.641419113909300.1450558
 3097656.400554513908920.6466853 3097782.557154513908820.0545145
 3099776.1167221 13908880.330364 3100602.783414813906576.4829413
#Sta/Elev= 30
    2632      96 3566.19   93.67 3938.23   94.32 4329.39   93.12 4572.87   90.62
 4869.21      91  4912.8    91.2  4946.9    80.2  4969.1    79.7    5000    74.1
  5011.2    74.2  5022.3      77  5073.1    93.4 5102.98   93.47 5991.52   92.85
 6020.97   86.49  6035.7   80.22  6080.7    92.4 6200.69   92.97 6899.18   91.67
 7112.42   92.52 7187.12      95 8088.65   93.54 8208.24   90.93  8402.3   94.34
 8634.96   89.74 9161.02   90.14 9429.86   86.55 9501.19   87.87 9515.46   92.23
#Mann= 11 ,-1 , 0
    2632      .2       0 3938.23     .14       0 4329.39     .08       0
 4869.21     .04       0  4912.8    .013       0  4946.9    .035       0
  5022.3    .013       0  5073.1    .035       0 5102.98     .08       0
 6200.69      .1       0 7187.12     .99       0
#Block Obstruct= 1 ,-1
 5991.52  6080.7    92.4
Bank Sta=4912.8,5073.1
XS Rating Curve= 0 ,0
Exp/Cntr=0.3,0.1

Type RM Length L Ch R = 1 ,175300.3,109.83,154.03,30.16
BEGIN DESCRIPTION:
EHRA Imported Cross Section 175300.3 (April 2011 LOMR)
END DESCRIPTION:
XS GIS Cut Line= 6
 3095725.539999313910034.1547791 3097468.326807713909442.5433224
 3097666.2292782  13909304.67868 3097791.447063313908824.7929842
 3099780.7114166  13908887.81218 3100613.677651513906570.3168352
#Sta/Elev= 30
 2541.85   95.84  3854.6   94.32 4265.93   93.67  4908.1   90.63    4913    93.5
  4934.1    91.4    4967   76.85  4993.3    76.5    5000    73.7  5034.9    73.9
    5040    76.2  5063.3    77.7  5108.4    93.4 5135.64   93.39 6032.09   93.02
 6061.01   86.68 6075.47   80.63  6104.4   89.23 6133.32   93.29 6981.17   91.86
 7170.64   92.48 7258.99   94.84 8110.75   93.68 8253.73   91.04 8451.53   93.92
 8684.44   89.59  9188.4   89.98 9455.89   86.26 9559.74   89.01 9574.59   99.91
#Mann= 11 ,-1 , 0
 2541.85      .2       0  3854.6     .14       0 4265.93     .08       0
  4908.1    .035       0  4934.1    .013       0    4967    .035       0
  5063.3    .013       0  5108.4    .035       0 5135.64     .08       0
 6133.32     .14       0 7258.99     .99       0
#XS Ineff= 2 , 0
       0  4919.6   91.19  5118.4       0   92.38
Permanent Ineff=
       F       F
#Block Obstruct= 1 ,-1
 6032.09 6126.24   92.78
Bank Sta=4934.1,5108.4
XS Rating Curve= 0 ,0
Exp/Cntr=0.5,0.3