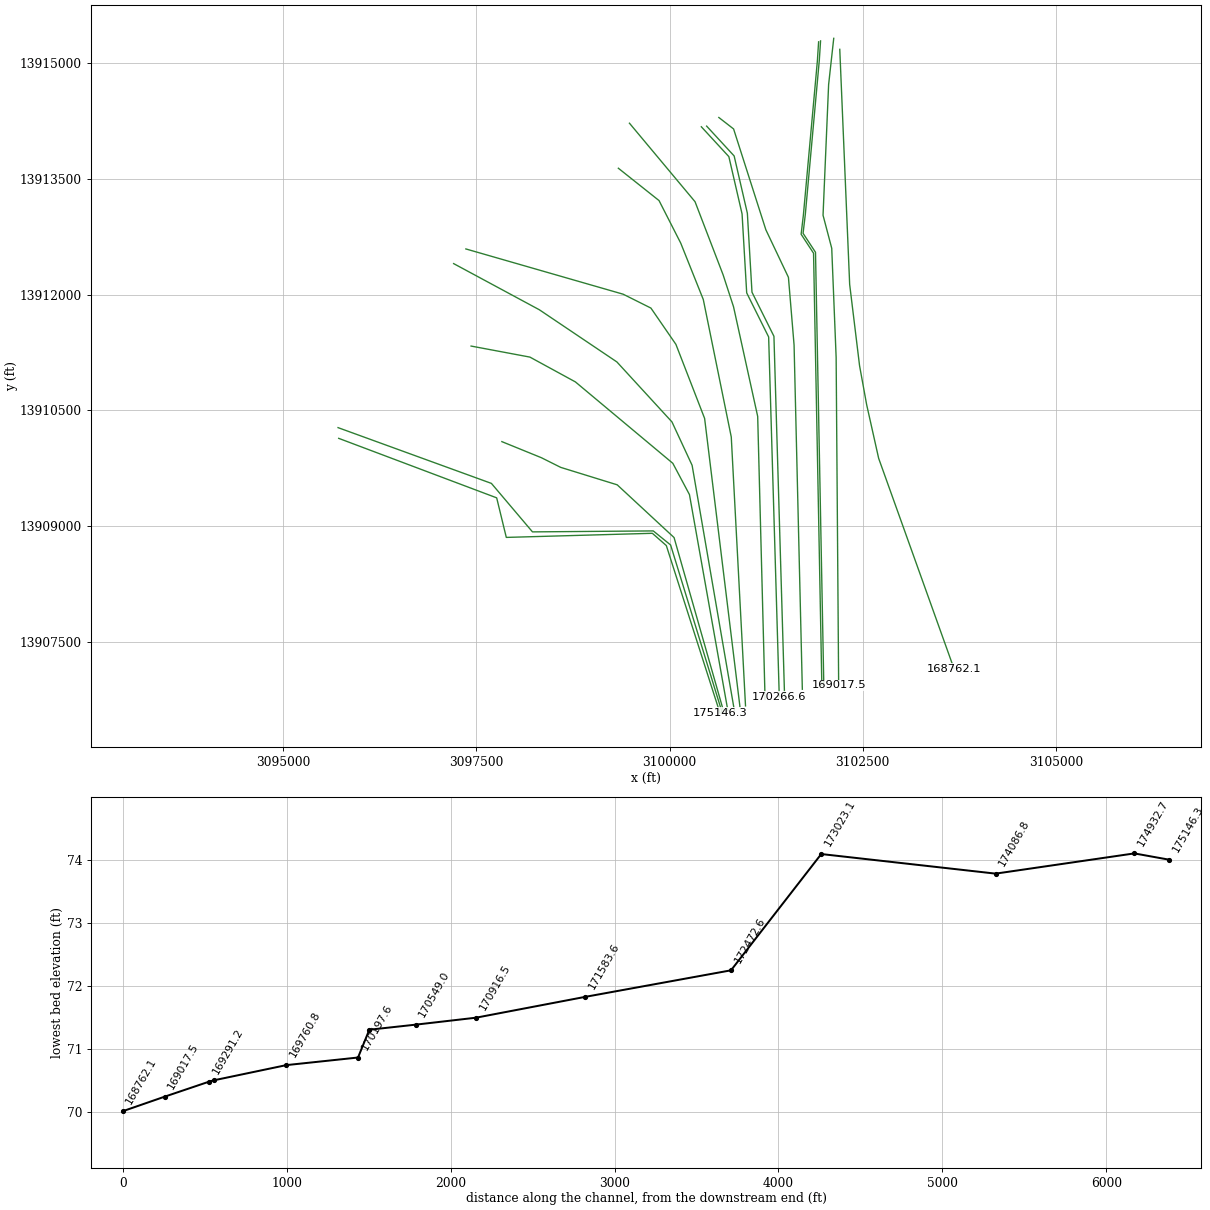
HEC-RAS study P100-00-00.prj: P100-00-00

--- P100-00-00.g01 (geometry) --- (continued)

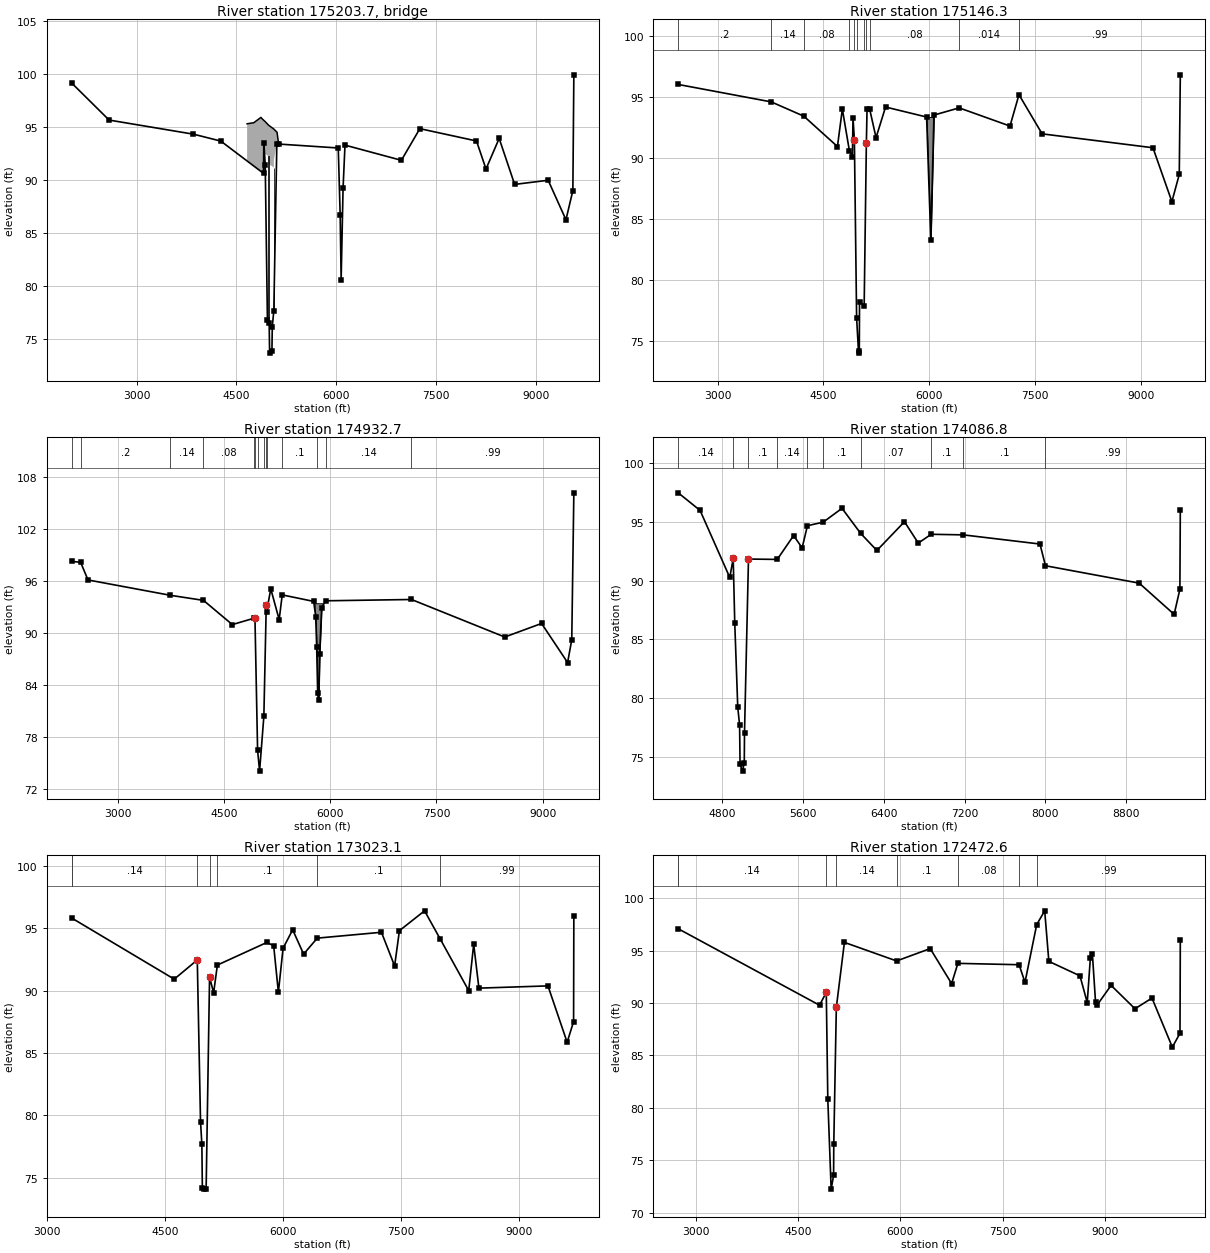
Type RM Length L Ch R = 3 ,175203.7,,,
BEGIN DESCRIPTION:
Ella Boulevard Bridge (April 2011)
END DESCRIPTION:
Bridge Culvert--1,0,-1,-1, 0
Deck Dist Width WeirC Skew NumUp NumDn MinLoCord MaxHiCord MaxSubmerge Is_Ogee
14.3,94,2.6,0, 11, 12, 91.2, , 0.95, 0, 0,0,,
  4661.5  4761.7  4869.2  4888.8  4933.9  4983.8  4983.9  5063.8  5063.9  5111.8
 5135.64
    95.3    95.4    95.9   95.76    95.5   95.17   95.17    94.8    94.8    94.5
   93.39
                                   92.46   92.24   91.54   91.17   91.87   91.89
        
  4629.9  4718.4  4814.9  4915.6  4927.8  4936.5  4983.5  4983.6  5063.8  5063.9
  5111.5    5120
    95.7    95.3    95.4    95.9   95.76    95.6   95.17   95.17    94.8    94.8
    94.5      94
                                            92.6   92.44   91.44   91.22   91.97
   91.86
Pier Skew, UpSta & Num, DnSta & Num=  ,4983.8, 2 ,4983.6, 2 , 0 , 0 , 0 ,,
     2.5     2.5
      40    92.5
     2.5     2.5
      40    92.5
Pier Skew, UpSta & Num, DnSta & Num=  ,5063.8, 2 ,5063.8, 2 , 0 , 0 , 0 ,,
     2.5     2.5
      40    92.5
     2.5     2.5
      40    92.5
BR Coef= 1 , 1 , 0 ,1.25, 0 ,,,0.8,0,1.2,0,
WSPro=,,,, 1 ,,,, 0 ,,,, 0 ,,,,-1 ,-1 ,-1 , 0 , 0 , 0 , 0 , 0
BR U #Sta/Elev= 30
    2025   99.13 2586.15   95.65  3854.6   94.32 4265.93   93.67  4908.1   90.63
    4913    93.5  4934.1    91.4    4967   76.85  4993.3    76.5    5000    73.7
  5034.9    73.9    5040    76.2  5063.3    77.7  5108.4    93.4 5135.64   93.39
 6032.09   93.02 6061.01   86.68 6075.47   80.63  6104.4   89.23 6133.32   93.29
 6981.17   91.86 7258.99   94.84 8110.75   93.68 8253.73   91.04 8451.53   93.92
 8684.44   89.59  9188.4   89.98 9455.89   86.26 9559.74   89.01 9574.59   99.91
BR U #Mann= 11
    2025      .2  3854.6     .14 4265.93     .08  4908.1    .035  4934.1    .013
    4967    .035  5063.3    .013  5108.4    .035 5135.64     .08 6133.32     .14
 7258.99     .99
BR D #Sta/Elev= 30
  1967.1   95.59 2041.93   98.45 2281.39   98.38 3761.75    94.6 4223.31   93.43
 4700.17   90.94  4769.8   94.01 4869.28   90.61  4940.5    91.5  4972.2   76.88
    5000      74  5010.2    74.2  5013.7    78.2  5079.3    77.9  5110.5    91.2
    5120      94  5157.6      94  5247.7   91.67  5382.6   94.18 5964.81   93.36
 6024.45   83.28 6069.18   93.52 6427.02   94.11 7147.65   92.62    7275   95.19
 7603.14   91.98  9175.2   90.84 9443.93   86.42 9548.43   88.65 9563.36   96.82
BR D #Mann= 12
  1967.1     .99 2281.39      .2 3761.75     .14 4223.31     .08 4869.28    .035
  4940.5    .013  4972.2    .035  5079.3    .013  5110.5    .035  5157.6     .08
 6427.02    .014    7275     .99
BC Design=,, 0 ,, 0 ,,,,,,
BC HTab HWMax=99.91
BC Use User HTab Curves=0
BC User HTab FreeFlow(D)= 0

Type RM Length L Ch R = 1 ,175146.3,144.52,213.6,234.21
BEGIN DESCRIPTION:
EHRA Imported Cross Section 175146.3 (April 2011 LOMR)
END DESCRIPTION:
XS GIS Cut Line= 6
 3095718.840868113910139.5899874 3097763.018657613909369.7196605
 3097887.541560413908857.7921712  3099777.37426613908910.9120603
 3099958.228958213908752.2936007 3100651.9994168 13906586.484541
#Sta/Elev= 30
  2442.1   96.03 3761.75    94.6 4223.31   93.43 4700.17   90.94  4769.8   94.01
 4869.28   90.61 4912.55   90.11  4920.8    93.3  4940.5    91.5  4972.2   76.88
    5000      74  5010.2    74.2  5013.7    78.2  5079.3    77.9  5110.5    91.2
    5120      94  5157.6      94  5247.7   91.67  5382.6   94.18 5964.81   93.36
 6024.45   83.28 6069.18   93.52 6427.02   94.11 7147.65   92.62    7275   95.19
 7603.14   91.98  9175.2   90.84 9443.93   86.42 9548.43   88.65 9563.36   96.82
#Mann= 11 ,-1 , 0
  2442.1      .2       0 3761.75     .14       0 4223.31     .08       0
 4869.28    .035       0  4940.5    .013       0  4972.2    .035       0
  5079.3    .013       0  5110.5    .035       0  5157.6     .08       0
 6427.02    .014       0    7275     .99       0
#XS Ineff= 2 , 0
       0  4932.7   91.26  5115.3       0   91.67
Permanent Ineff=
       F       F
#Block Obstruct= 1 ,-1
 5964.89 6069.18   93.36
Bank Sta=4940.5,5110.5
XS Rating Curve= 0 ,0
Exp/Cntr=0.5,0.3

Type RM Length L Ch R = 1 ,174932.7,629.58,845.95,888.83
BEGIN DESCRIPTION:
EHRA Imported Cross Section 174932.7 (April 2011 LOMR)
END DESCRIPTION:
XS GIS Cut Line= 6
 3095710.435566813910278.2249698 3097694.813871713909556.6456721
 3098226.248250513908929.2712145 3099789.107964313908941.7790953
 3100013.624425913908759.7894288 3100683.734143113906580.7428618
#Sta/Elev= 30
    2346   98.24  2470.4   98.15 2575.36   96.11 3740.57   94.34 4207.04   93.76
  4614.9   90.97  4919.3    91.7  4934.7    91.7  4971.9    76.5    5000    74.1
  5060.4    80.4  5094.4    93.2 5099.28   92.47 5158.38   95.08 5276.77   91.54
 5320.03   94.39 5764.48   93.64 5793.01   91.89    5807   88.37    5821   83.05
 5834.99   82.24 5848.99   87.55 5876.98   92.92 5934.45   93.71 7146.77   93.86
 8464.48   89.54 8984.82    91.1 9352.83    86.6  9411.6   89.23 9440.98  106.14
#Mann= 14 ,-1 , 0
    2346     .99       0  2470.4      .2       0 3740.57     .14       0
 4207.04     .08       0  4919.3    .035       0  4934.7    .013       0
  4971.9    .035       0  5060.4    .013       0  5094.4    .035       0
 5099.28     .08       0 5320.03      .1       0    5807     .08       0
 5934.45     .14       0 7146.77     .99       0
#Block Obstruct= 1 ,-1
 5779.01 5890.97   93.43
Bank Sta=4934.7,5094.4
XS Rating Curve= 0 ,0
Exp/Cntr=0.3,0.1

Type RM Length L Ch R = 1 ,174086.8,1091.3,1063.7,1012.3
BEGIN DESCRIPTION:
Cross Section 174086.8
END DESCRIPTION:
XS GIS Cut Line= 6
      3097830.38     13910096.99      3098341.69      13909888.9
      3098591.41     13909764.04       3099322.7     13909538.11
       3100058.4     13908856.01      3100706.63      13906581.4
#Sta/Elev= 30
  4368.3   97.48  4584.4   95.98    4878   90.27  4911.9   91.89  4927.2    86.4
  4956.9   79.22  4975.1    77.7  4979.6   74.35  5004.5   73.78  5021.3   74.49
  5023.6   77.04    5063   91.84  5347.4   91.81  5509.3   93.84  5593.4   92.79
  5645.9   94.68  5801.4   94.98  5987.9   96.16  6172.8   94.02  6332.8   92.57
  6605.6   95.02  6741.9    93.2  6870.1   93.95  7186.6    93.9  7945.4   93.12
    8000   91.27  8926.7   89.79  9272.3   87.13  9329.1   89.27  9333.3      96
#Mann= 10 ,-1 , 0
  4368.3     .14       0  4911.9     .04       0    5063      .1       0
  5347.4     .14       0  5645.9     .07       0  5801.4      .1       0
  6172.8     .07       0  6870.1      .1       0  7186.6      .1       0
    8000     .99       0
Bank Sta=4911.9,5063
XS Rating Curve= 0 ,0
Exp/Cntr=0.3,0.1

Type RM Length L Ch R = 1 ,173023.1,530.7,550.5,556.4
BEGIN DESCRIPTION:
Cross Section 173023.1
END DESCRIPTION:
XS GIS Cut Line= 6
      3097432.03     13911333.66      3098193.06     13911190.96
      3098781.66     13910869.91      3100042.52     13909816.28
      3100257.54     13909411.73      3100754.25     13906618.48
#Sta/Elev= 30
  3315.4   95.83  4618.4   90.93  4911.5   92.47  4952.8   79.51  4969.7    77.7
  4976.1   74.21  5001.1   74.09  5024.2   74.12  5067.8   91.09  5119.5   89.83
    5167   92.06  5795.1   93.87  5882.9   93.62  5942.8   89.88  6002.7   93.41
  6124.6   94.89    6264   92.94  6437.6   94.22  7253.6   94.69  7421.2   91.99
  7482.1   94.82    7802   96.41    8000   94.16  8363.4   90.01  8426.7   93.73
  8493.1   90.21  9371.3   90.39    9615   85.87  9697.1   87.52  9700.4      96
#Mann= 7 , 1 , 0
  3315.4      .2       0  3315.4     .14       0  4911.5     .04       0
  5067.8     .14       0    5167      .1       0  6437.6      .1       0
    8000     .99       0
Bank Sta=4911.5,5067.8
XS Rating Curve= 0 ,0
Exp/Cntr=0.3,0.1

Type RM Length L Ch R = 1 ,172472.6,894.3,889,885.4
BEGIN DESCRIPTION:
Cross Section 172472.6-Interpolated
END DESCRIPTION:
XS GIS Cut Line= 6
      3097206.08     13912400.82      3098315.48     13911803.23
      3099318.68     13911128.18      3100031.36     13910351.86
      3100292.02     13909790.42      3100838.86     13906617.01
#Sta/Elev= 30
  2741.6   97.08  4814.2   89.79  4913.2   91.01  4935.7   80.82  4984.7   72.25
  5020.6   73.55  5023.1   76.51  5060.8   89.58  5179.3   95.78  5944.8   94.01
  6437.6   95.19  6751.9   91.85  6843.6   93.78  7741.7   93.65  7828.1   91.97
    8000   97.48  8117.3   98.79  8178.1   93.97  8634.8   92.59  8741.3   90.04
    8787   94.29  8817.4   94.63  8863.3   90.07  8888.9   89.83  9091.4   91.68
  9441.5   89.45  9690.9   90.47  9989.4   85.79 10101.9   87.11 10106.6      96
#Mann= 8 , 1 , 0
  2741.6      .2       0  2741.6     .14       0  4913.2     .04       0
  5060.8     .14       0  5944.8      .1       0  6843.6     .08       0
  7741.7      .1       0    8000     .99       0
Bank Sta=4913.2,5060.8
XS Rating Curve= 0 ,0
Exp/Cntr=0.3,0.1

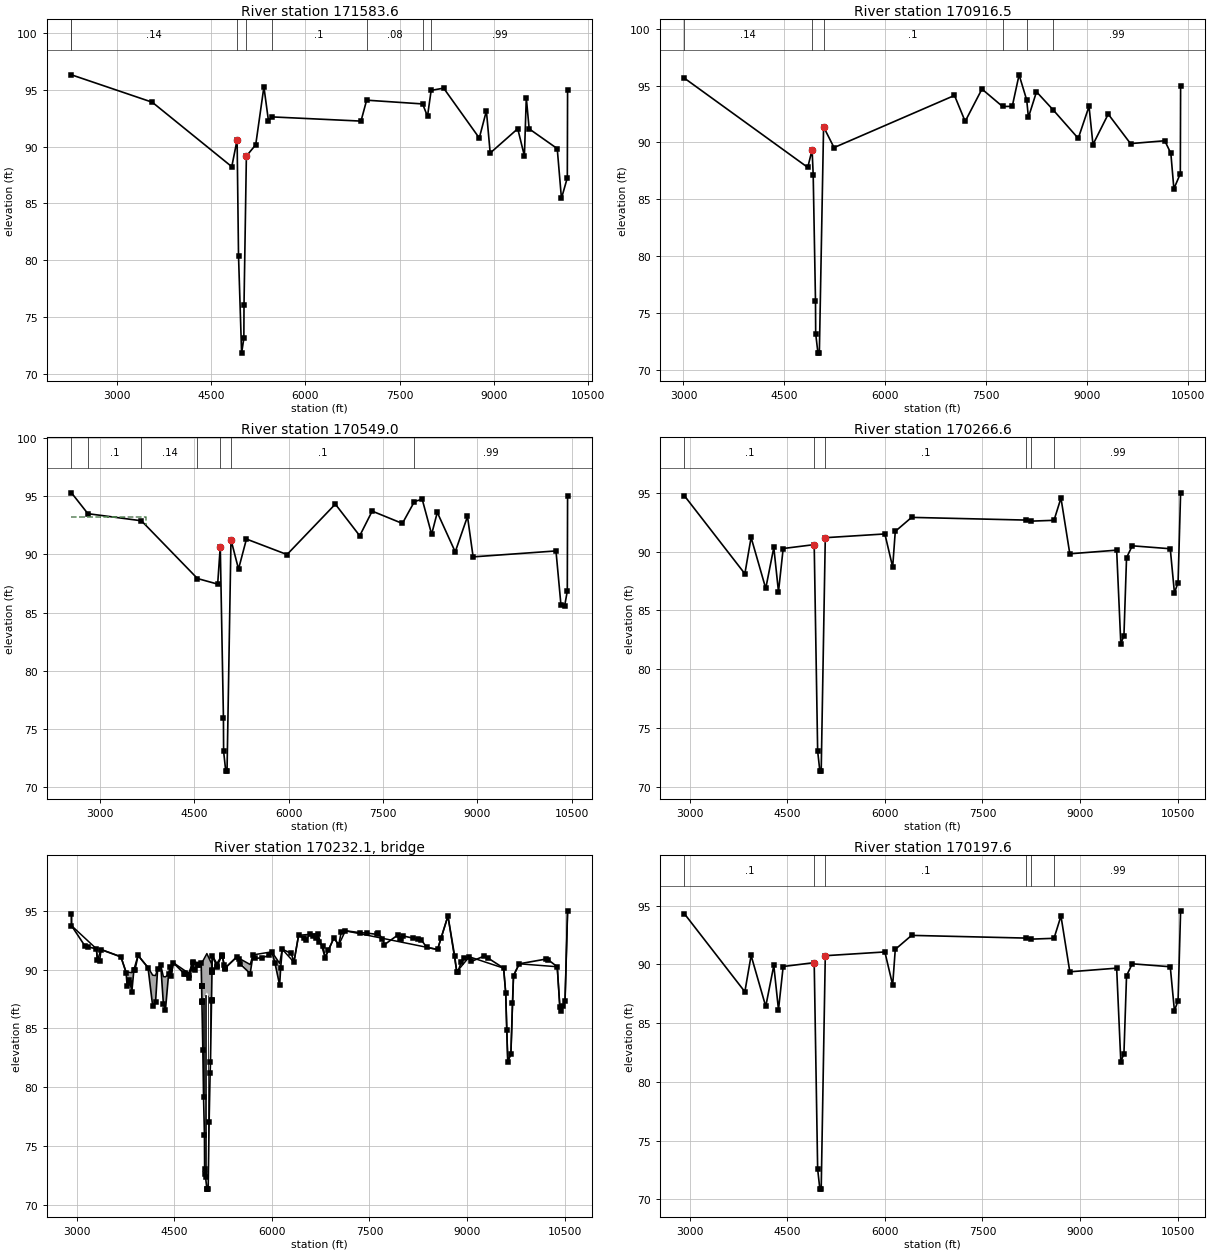
Type RM Length L Ch R = 1 ,171583.6,829,667.1,608.8
BEGIN DESCRIPTION:
Cross Section 171583.6
END DESCRIPTION:
XS GIS Cut Line= 6
      3097364.45     13912590.46      3099399.57     13912004.79
      3099759.11     13911825.02      3100082.36     13911355.56
      3100453.74      13910397.4      3100910.92     13906665.56
#Sta/Elev= 30
  2278.4   96.31  3563.4    93.9  4828.4   88.23  4913.2   90.59  4935.7    80.4
  4984.7   71.83  5020.6   73.13  5023.1   76.09  5060.8   89.16  5209.4   90.16
  5339.6   95.25  5411.4   92.29  5465.8   92.61  6884.1   92.24  6973.7   94.08
  7864.5   93.75    7942   92.66    8000   94.94  8198.9   95.14  8765.7   90.75
  8878.9   93.14  8939.4   89.43  9377.6   91.57  9483.4   89.17  9513.6    94.3
    9559   91.56 10005.7   89.82 10072.8   85.44 10166.1   87.25 10170.4      95
#Mann= 8 , 1 , 0
  2278.4      .2       0  2278.4     .14       0  4913.2     .04       0
  5060.8     .14       0  5465.8      .1       0  6973.7     .08       0
  7864.5      .1       0    8000     .99       0
Bank Sta=4913.2,5060.8
XS Rating Curve= 0 ,0
Exp/Cntr=0.3,0.1

Type RM Length L Ch R = 1 ,170916.5,368.8,367.5,360
BEGIN DESCRIPTION:
Cross Section 170916.5-Interpolated
END DESCRIPTION:
XS GIS Cut Line= 6
       3099337.5     13913634.76      3099863.86     13913216.39
      3100144.57      13912666.2       3100436.5     13911936.35
      3100798.57     13910157.46      3100982.95     13906677.64
#Sta/Elev= 30
  3015.6   95.64  4848.2   87.81  4912.8   89.35    4929   87.18  4963.3   76.09
  4966.2    73.2    5000    71.5  5020.6   71.51  5083.5   91.37    5239   89.55
    7030   94.13  7188.7   91.85  7438.1   94.69  7744.3   93.16  7888.7   93.17
  7990.4   95.94  8104.1   93.72    8129    92.2  8249.2   94.45    8500   92.84
    8870   90.36  9030.3   93.17  9088.9   89.82  9315.7   92.49  9647.2    89.9
 10156.9   90.15   10247   89.04   10292   85.93 10387.7   87.26   10392      95
#Mann= 6 , 1 , 0
  3015.6     .14       0  4912.8    .035       0  5083.5      .1       0
  7744.3     .08       0  8104.1      .1       0    8500     .99       0
Bank Sta=4912.8,5083.5
XS Rating Curve= 0 ,0
Exp/Cntr=0.3,0.1

Type RM Length L Ch R = 1 ,170549.0,428.4,282.4,132.2
BEGIN DESCRIPTION:
Cross Section 170549.0-Interpolated
END DESCRIPTION:
XS GIS Cut Line= 6
       3099481.1      13914217.5      3100329.69     13913201.91
      3100692.81     13912256.11      3100827.92     13911842.32
      3101140.38     13910423.63      3101235.99     13906761.72
#Sta/Elev= 30
  2547.3   95.29    2808    93.5  3658.9   92.89  4550.4   87.93  4871.7   87.45
    4913   90.67  4963.3   75.98  4966.2   73.09    5000   71.39  5020.6    71.4
  5083.5   91.26  5203.3   88.74  5329.2   91.32  5974.3   89.99  6742.3   94.32
  7130.3    91.6  7328.2   93.72  7808.3   92.66    8000   94.54  8123.4   94.74
  8273.5   91.73  8363.5   93.61  8648.6   90.22  8843.7   93.26    8933   89.79
 10250.5    90.3 10329.2   85.68 10389.2   85.61 10430.4   86.85   10435      95
#Mann= 7 , 1 , 0
  2547.3     .14       0    2808      .1       0  3658.9     .14       0
  4550.4      .1       0    4913    .035       0  5083.5      .1       0
    8000     .99       0
#XS Ineff= 2 , 0
       0    3731   93.25               0
Permanent Ineff=
       F       F
Bank Sta=4913,5083.5
XS Rating Curve= 0 ,0
Exp/Cntr=0.5,0.3

Type RM Length L Ch R = 1 ,170266.6,69,69,69
BEGIN DESCRIPTION:
Upstream Section of Bridge/Culvert/Weir
END DESCRIPTION:
XS GIS Cut Line= 6
      3100411.31     13914171.33      3100767.32     13913785.17
      3100938.41     13913043.45       3100998.2     13912021.98
      3101282.27     13911451.47      3101419.82     13906795.31
#Sta/Elev= 30
  2919.3   94.74  3847.1   88.11  3943.1    91.2  4168.2   86.86  4292.1   90.35
  4364.1   86.58  4436.1   90.26    4913   90.59  4966.2   73.01    5000   71.31
  5020.6   71.32  5083.5   91.18  5999.3    91.5  6119.3   88.68  6159.3   91.72
  6410.3   92.91  8165.7   92.68  8243.3   92.59  8599.4   92.66  8706.3   94.56
  8842.3   89.81  9562.3   90.12  9626.3   82.15  9674.3   82.85  9714.3   89.48
  9802.3   90.49 10386.3   90.24 10450.3    86.5 10506.3   87.35 10545.4      95
#Mann= 6 , 1 , 0
  2919.3      .1       0    4913    .035       0  5083.5      .1       0
  8165.7     .08       0  8243.3      .1       0  8599.4     .99       0
#XS Ineff= 2 , 0
       0    4914    89.2    5083       0    89.9
Permanent Ineff=
       F       F
Bank Sta=4913,5083.5
XS Rating Curve= 0 ,0
Exp/Cntr=0.5,0.3

Type RM Length L Ch R = 3 ,170232.1,,,
BEGIN DESCRIPTION:
NORTHBOROUGH DRIVE
Structure ID: P00-61
END DESCRIPTION:
Bridge Culvert--1,0,-1,-1, 0
Deck Dist Width WeirC Skew NumUp NumDn MinLoCord MaxHiCord MaxSubmerge Is_Ogee
10,49,2.6,0, 60, 60, , , 0.95, 0, 1,1,,
  2919.3  2919.4  3302.2  3318.2  3374.2  3679.1  3759.1  3775.1  3847.1  3879.1
  3943.1  4096.2  4168.2  4212.1  4244.1  4292.1  4332.1  4364.1  4412.1  4452.1
  4484.1  4719.5  4789.2    4913 4924.41  5000.7  5072.6  5080.7  5083.5  5155.4
    5234  5274.9  5458.2  5666.2  5710.1  5999.3  6119.3  6159.3  6338.3  6410.3
  6706.3  6818.3  6954.3  7026.3  7130.3  8546.3  8706.3  8842.3  9034.3  9562.3
  9594.3  9626.3  9674.3  9714.3  9802.3 10386.3 10426.3 10450.3 10506.3 10545.4
   94.74   93.74   91.77    90.8   91.71   91.09    89.8   89.79   89.74   90.01
   91.21   90.17   89.52   89.49    90.1   90.36    89.4   89.38   89.61   89.48
   90.59   89.69   90.63    90.6   90.58   91.36    90.5   89.91   91.19   90.51
   91.25    90.1   91.07   90.43   91.25   91.51   90.53   91.73   90.63   92.92
   93.05   91.03   92.71   92.08    93.3   91.71   94.56   89.81   91.09   90.12
      88   82.15   82.85   89.48   90.49   90.24   86.83    86.5   87.35      95
   94.74   93.74   91.76   90.79    91.7   91.08   89.73   88.61   88.11      90
    91.2   90.16   86.86   87.25   90.09   90.35   87.08   86.58    89.6   89.47
   90.58   89.32   90.62   90.59   87.29   88.06   87.34   89.91   91.18   90.25
   91.24   90.09   91.06   89.66   91.24    91.5   88.68   91.72   90.62   92.91
   93.04   91.02   92.71   92.08    93.3   91.71   94.56   89.81   91.09   90.12
      88   82.15   82.85   89.48   90.49   90.24   86.83    86.5   87.35      95
  2919.3  2919.4  3302.2  3318.2  3374.2  3679.1  3759.1  3775.1  3847.1  3879.1
  3943.1  4096.2  4168.2  4212.1  4244.1  4292.1  4332.1  4364.1  4412.1  4452.1
  4484.1  4719.5  4789.2    4913 4924.41  5000.7  5072.6  5080.7  5083.5  5155.4
    5234  5274.9  5458.2  5666.2  5710.1  5999.3  6119.3  6159.3  6338.3  6410.3
  6706.3  6818.3  6954.3  7026.3  7130.3  8546.3  8706.3  8842.3  9034.3  9562.3
  9594.3  9626.3  9674.3  9714.3  9802.3 10386.3 10426.3 10450.3 10506.3 10545.4
   94.74   93.74   91.77    90.8   91.71   91.09    89.8   89.79   89.74   90.01
   91.21   90.17   89.52   89.49    90.1   90.36    89.4   89.38   89.61   89.48
   90.59   89.69   90.63    90.6   90.58   91.36    90.5   89.91   91.19   90.51
   91.25    90.1   91.07   90.43   91.25   91.51   90.53   91.73   90.63   92.92
   93.05   91.03   92.71   92.08    93.3   91.71   94.56   89.81   91.09   90.12
      88   82.15   82.85   89.48   90.49   90.24   86.83    86.5   87.35      95
    94.3    93.3   91.32   90.35   91.26   90.64   89.29   88.17   87.67   89.56
   90.76   89.72   86.42   86.81   89.65   89.91   86.64   86.14   89.16   89.03
   90.14   88.88   90.18   90.15   86.85   87.62    86.9   89.47   90.74   89.81
    90.8   89.65   90.62   89.22    90.8   91.06   88.24   91.28   90.18   92.47
    92.6   90.58   92.27   91.64   92.86   91.27   94.12   89.37   90.65   89.68
   87.56   81.71   82.41   89.04   90.05    89.8   86.39   86.06   86.91   94.56
Pier Skew, UpSta & Num, DnSta & Num=  ,4949.5, 2 ,4949.5, 2 , 0 , 0 , 0 ,,
       2       2
   77.95   88.55
       2       2
   77.51   88.11
Pier Skew, UpSta & Num, DnSta & Num=  ,4980.4, 2 ,4980.4, 2 , 0 , 0 , 0 ,,
       2       2
   71.29   88.86
       2       2
   70.85   88.42
Pier Skew, UpSta & Num, DnSta & Num=  ,5020.6, 2 ,5020.6, 2 , 0 , 0 , 0 ,,
       2       2
   70.32   88.83
       2       2
   69.88   88.39
Pier Skew, UpSta & Num, DnSta & Num=  ,5050.5, 2 ,5050.5, 2 , 0 , 0 , 0 ,,
       2       2
   79.93   88.48
       2       2
   79.49   88.04
BR Coef= 1 , 1 , 0 ,1.25, 0 ,,,0.8,0,2,0,
WSPro=,,,, 1 ,,,, 0 ,,,, 0 ,,,,-1 ,-1 ,-1 , 0 , 0 , 0 , 0 , 0
BR U #Sta/Elev= 148
  2919.3   94.74  2919.4   93.74  3127.4      92    3176   91.93  3302.2   91.76
  3318.2   90.79  3350.2   90.69  3374.2    91.7  3679.1   91.08  3759.1   89.73
  3775.1   88.61  3799.1   89.09  3823.1   88.82  3847.1   88.11  3879.1      90
  3895.1   89.97  3943.1    91.2  4096.2   90.16  4168.2   86.86  4212.1   87.25
  4244.1   90.09  4292.1   90.35  4332.1   87.08  4364.1   86.58  4412.1    89.6
  4436.1   90.26  4452.1   89.47  4484.1   90.58  4654.8   89.63  4659.3   89.61
  4665.6   89.67  4719.5   89.32  4730.6   89.53  4787.1   90.58  4789.2   90.62
  4791.7   90.09    4819   89.97  4863.8   90.38  4866.9   90.41    4913   90.59
 4919.79   88.62  4919.9   88.59 4920.01   88.56 4924.41   87.29  4924.5   87.26
  4924.6   87.23  4938.8   83.12  4949.5   79.19  4963.3    75.9  4966.2   73.01
  4971.4   72.62  4980.4   72.34    5000   71.31  5000.7   71.31  5020.6   71.32
  5035.2   77.06  5050.5    81.2  5056.1    82.1  5072.6   87.34 5072.69   87.37
  5072.8    87.4 5080.29   89.78  5080.4   89.81 5080.51   89.85  5080.7   89.91
  5080.8   89.96  5083.5   91.18  5149.5   90.33  5155.4   90.25    5226   91.14
  5228.4   91.17    5234   91.24  5268.4    90.4  5273.2   90.17  5274.9   90.09
  5280.5   90.12  5458.2   91.06  5490.2    90.9  5514.2   90.47  5666.2   89.66
  5710.1   91.24  5742.1   90.95  5846.1      91  5959.3   91.21  5999.3    91.5
  6047.3   90.55  6119.3   88.68  6135.3   90.16  6159.3   91.72  6298.3   91.38
  6338.3   90.62  6410.3   92.91  6498.3   92.66  6530.3   92.53  6578.3      93
  6634.3   92.85  6674.3   92.71  6706.3   93.04  6730.3   92.32  6786.3   91.98
  6818.3   91.02  6868.2   91.64  6954.3   92.71  7026.3   92.08  7066.3   93.18
  7130.3    93.3  7354.3   93.14  7466.3    93.1  7610.3      93  7626.3   93.15
  7698.3   92.64  7730.3   92.12  7938.3   92.95  7962.3    92.6  7986.3   92.64
  8018.3   92.86  8165.7   92.68  8243.3   92.59  8298.3   92.52  8378.3   91.89
  8546.3   91.71  8599.4   92.66  8706.3   94.56  8810.3   91.13  8842.3   89.81
  8858.3   89.81  8914.3   90.67  8946.3   90.96  9034.3   91.09  9066.3   90.69
  9258.3   91.14  9322.3   90.98  9562.3   90.12  9594.3      88  9610.3   84.85
  9626.3   82.15  9674.3   82.85  9698.3   87.16  9714.3   89.48  9802.3   90.49
 10210.3   90.89 10250.3   90.82 10386.3   90.24 10426.3   86.83 10450.3    86.5
 10474.3   86.94 10506.3   87.35 10545.4      95
BR U #Mann= 6
  2919.3      .1    4913    .035  5083.5      .1  8165.7     .08  8243.3      .1
  8599.4     .99
BR U Banks=4913,5083.5
BR D #Sta/Elev= 148
  2919.3    94.3  2919.4    93.3  3127.4   91.56    3176   91.49  3302.2   91.32
  3318.2   90.35  3350.2   90.25  3374.2   91.26  3679.1   90.64  3759.1   89.29
  3775.1   88.17  3799.1   88.65  3823.1   88.38  3847.1   87.67  3879.1   89.56
  3895.1   89.53  3943.1   90.76  4096.2   89.72  4168.2   86.42  4212.1   86.81
  4244.1   89.65  4292.1   89.91  4332.1   86.64  4364.1   86.14  4412.1   89.16
  4436.1   89.82  4452.1   89.03  4484.1   90.14  4654.8   89.19  4659.3   89.17
  4665.6   89.23  4719.5   88.88  4730.6   89.09  4787.1   90.14  4789.2   90.18
  4791.7   89.65    4819   89.53  4863.8   89.94  4866.9   89.97    4913   90.15
 4919.79   88.18  4919.9   88.15 4920.01   88.12 4924.41   86.85  4924.5   86.82
  4924.6   86.79  4938.8   82.68  4949.5   78.75  4963.3   75.46  4966.2   72.57
  4971.4   72.18  4980.4    71.9    5000   70.87  5000.7   70.87  5020.6   70.88
  5035.2   76.62  5050.5   80.76  5056.1   81.66  5072.6    86.9 5072.69   86.93
  5072.8   86.96 5080.29   89.34  5080.4   89.37 5080.51   89.41  5080.7   89.47
  5080.8   89.52  5083.5   90.74  5149.5   89.89  5155.4   89.81    5226    90.7
  5228.4   90.73    5234    90.8  5268.4   89.96  5273.2   89.73  5274.9   89.65
  5280.5   89.68  5458.2   90.62  5490.2   90.46  5514.2   90.03  5666.2   89.22
  5710.1    90.8  5742.1   90.51  5846.1   90.56  5959.3   90.77  5999.3   91.06
  6047.3   90.11  6119.3   88.24  6135.3   89.72  6159.3   91.28  6298.3   90.94
  6338.3   90.18  6410.3   92.47  6498.3   92.22  6530.3   92.09  6578.3   92.56
  6634.3   92.41  6674.3   92.27  6706.3    92.6  6730.3   91.88  6786.3   91.54
  6818.3   90.58  6868.2    91.2  6954.3   92.27  7026.3   91.64  7066.3   92.74
  7130.3   92.86  7354.3    92.7  7466.3   92.66  7610.3   92.56  7626.3   92.71
  7698.3    92.2  7730.3   91.68  7938.3   92.51  7962.3   92.16  7986.3    92.2
  8018.3   92.42  8165.7   92.24  8243.3   92.15  8298.3   92.08  8378.3   91.45
  8546.3   91.27  8599.4   92.22  8706.3   94.12  8810.3   90.69  8842.3   89.37
  8858.3   89.37  8914.3   90.23  8946.3   90.52  9034.3   90.65  9066.3   90.25
  9258.3    90.7  9322.3   90.54  9562.3   89.68  9594.3   87.56  9610.3   84.41
  9626.3   81.71  9674.3   82.41  9698.3   86.72  9714.3   89.04  9802.3   90.05
 10210.3   90.45 10250.3   90.38 10386.3    89.8 10426.3   86.39 10450.3   86.06
 10474.3    86.5 10506.3   86.91 10545.4   94.56
BR D #Mann= 6
  2919.3      .1    4913    .035  5083.5      .1  8165.7     .08  8243.3      .1
  8599.4     .99
BR D Banks=4913,5083.5
BC Design=,, 0 ,, 0 ,,,,,,
BC HTab HWMax=95
BC Use User HTab Curves=0
BC User HTab FreeFlow(D)= 0

Type RM Length L Ch R = 1 ,170197.6,436.8,436.8,436.8
BEGIN DESCRIPTION:
Downstream Section of Bridge/Culvert/Weir
END DESCRIPTION:
XS GIS Cut Line= 6
      3100479.76     13914179.95      3100835.78     13913793.79
      3101006.87     13913052.07      3101066.66      13912030.6
      3101350.73     13911460.09      3101488.28     13906803.94
#Sta/Elev= 30
  2919.3    94.3  3847.1   87.67  3943.1   90.76  4168.2   86.42  4292.1   89.91
  4364.1   86.14  4436.1   89.82    4913   90.15  4966.2   72.57    5000   70.87
  5020.6   70.88  5083.5   90.74  5999.3   91.06  6119.3   88.24  6159.3   91.28
  6410.3   92.47  8165.7   92.24  8243.3   92.15  8599.4   92.22  8706.3   94.12
  8842.3   89.37  9562.3   89.68  9626.3   81.71  9674.3   82.41  9714.3   89.04
  9802.3   90.05 10386.3    89.8 10450.3   86.06 10506.3   86.91 10545.4   94.56
#Mann= 6 , 1 , 0
  2919.3      .1       0    4913    .035       0  5083.5      .1       0
  8165.7     .08       0  8243.3      .1       0  8599.4     .99       0
#XS Ineff= 2 , 0
       0    4914    88.9    5083       0    89.4
Permanent Ineff=
       F       F
Bank Sta=4913,5083.5
XS Rating Curve= 0 ,0
Exp/Cntr=0.5,0.3

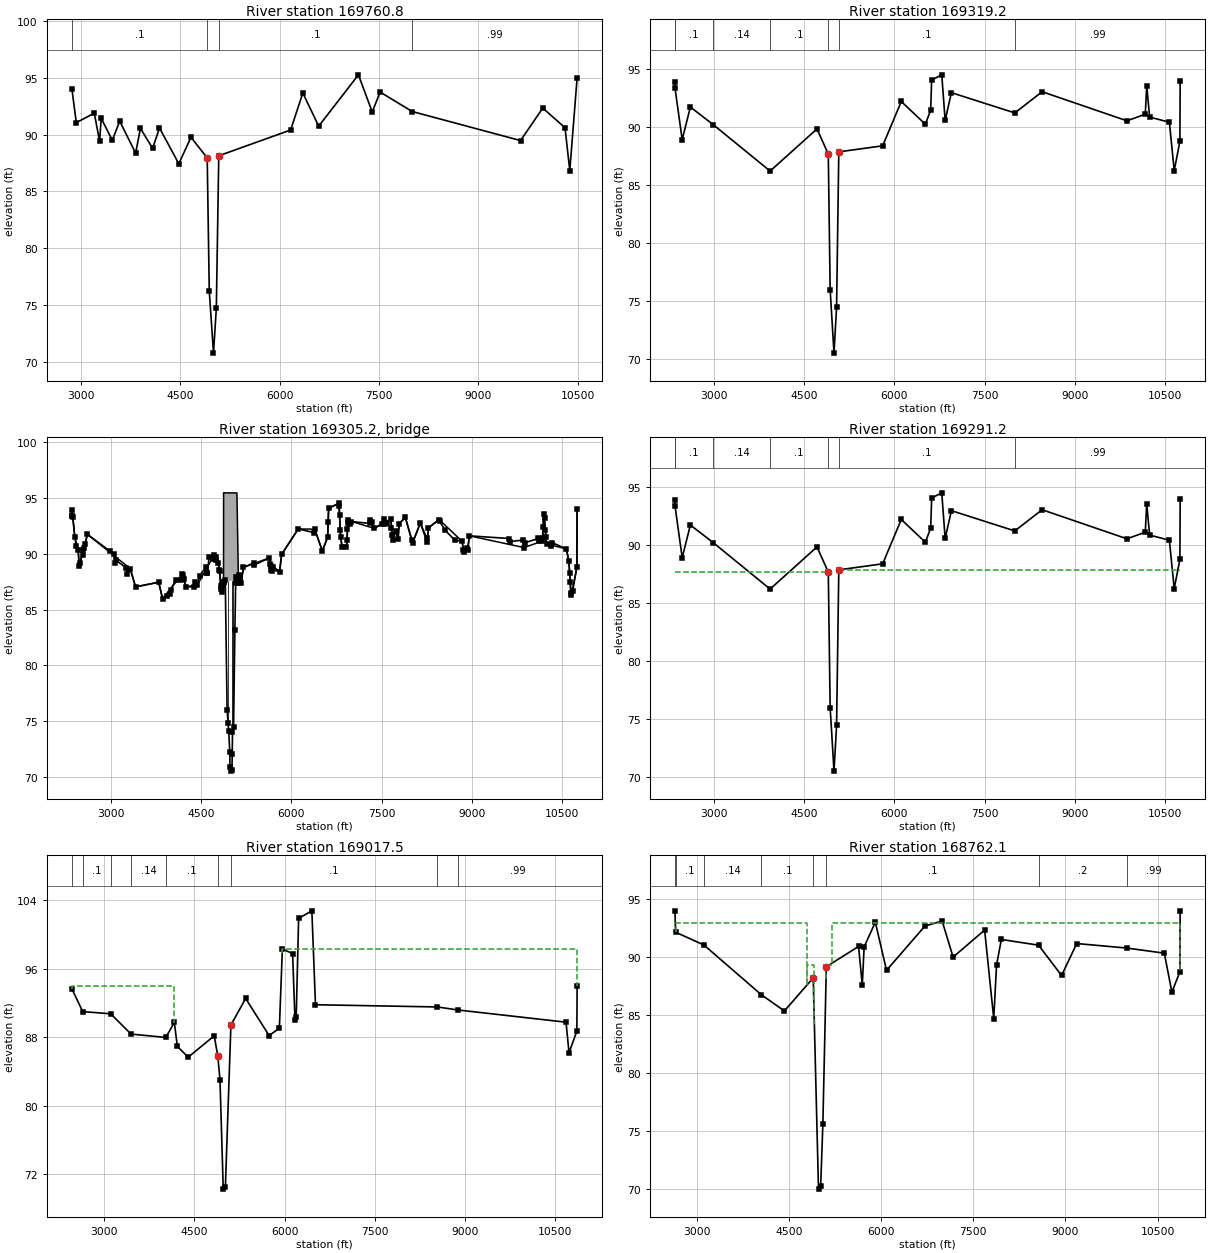
Type RM Length L Ch R = 1 ,169760.8,588.4,441.6,424.6
BEGIN DESCRIPTION:
Cross Section 169760.8-Interpolated
END DESCRIPTION:
XS GIS Cut Line= 6
      3100637.64     13914291.46      3100828.73       13914143.
      3101246.11     13912838.69      3101538.28     13912223.06
      3101611.32     13911346.56       3101718.2     13906892.98
#Sta/Elev= 30
  2861.2      94  2927.2   91.05  3199.2   91.88  3279.2   89.41  3303.2   91.43
  3471.2    89.5  3583.2   91.18  3823.2   88.36  3895.8   90.54  4079.8   88.79
  4183.8   90.58  4475.4   87.43  4659.4   89.76 4904.38   87.94 4935.38   76.24
 4999.18   70.75 5042.18   74.71 5078.88   88.13  6164.3    90.4  6348.3   93.66
  6588.3   90.74  7188.3   95.26  7396.3   91.99  7516.3   93.74    8000   92.03
  9636.3   89.47  9972.3   92.33 10308.3    90.6 10380.3   86.83 10491.2      95
#Mann= 4 , 1 , 0
  2861.2      .1       0 4904.38    .035       0 5078.88      .1       0
    8000     .99       0
Bank Sta=4904.38,5078.88
XS Rating Curve= 0 ,0
Exp/Cntr=0.5,0.3

Type RM Length L Ch R = 1 ,169319.2,28,28,28
BEGIN DESCRIPTION:
Upstream Section of Bridge/Culvert/Weir
END DESCRIPTION:
XS GIS Cut Line= 6
      3101928.72     13915270.52      3101912.56     13915020.12
      3101731.66     13913027.67      3101702.44     13912780.67
      3101863.32     13912535.27      3101970.54     13906944.93
#Sta/Elev= 30
  2359.5   93.93  2359.8   93.43  2479.6   88.94  2615.4   91.76  2991.7   90.25
  3938.9   86.23  4716.7   89.87 4904.38    87.7 4935.38      76 4999.18   70.51
 5042.18   74.47 5078.88   87.89    5807   88.41  6115.9   92.24  6515.9   90.27
  6603.9    91.5  6619.9   94.09  6787.9   94.54  6843.9    90.6  6947.9      93
    8000   91.25  8453.7   93.08  9861.7   90.57 10165.7   91.14 10189.7    93.6
 10237.7   90.89 10565.7   90.45 10645.7   86.27 10740.3   88.79 10744.6   94.01
#Mann= 7 , 1 , 0
  2359.5      .2       0  2359.8      .1       0  2991.7     .14       0
  3938.9      .1       0 4904.38    .035       0 5078.88      .1       0
    8000     .99       0
#XS Ineff= 2 , 0
       0 4904.38   87.69 5078.88       0   87.88
Permanent Ineff=
       F       F
Bank Sta=4904.38,5078.88
XS Rating Curve= 0 ,0
Exp/Cntr=0.5,0.3

Type RM Length L Ch R = 3 ,169305.2,,,
BEGIN DESCRIPTION:
PIPE RACK
Structure ID: P00-60
END DESCRIPTION:
Bridge Culvert--1,0,-1,-1, 0
Deck Dist Width WeirC Skew NumUp NumDn MinLoCord MaxHiCord MaxSubmerge Is_Ogee
10,8,2.6,0, 60, 60, , , 0.95, 0, 1,1,,
  2359.5  2407.6  2463.6  2479.6  2615.4  3327.4  3415.4  3799.4  3863.4  4191.4
  4255.4  4439.4  4716.7  4788.7 4848.98 4875.98 4876.78 5097.88 5123.88    5167
    5207    5631    5671    5807    5839  6115.9  6387.9  6515.9  6603.9  6619.9
  6787.9  6819.9  6843.9  6915.9  6947.9  7371.9  7653.7  7685.7  7733.7  7773.7
  7789.7  7893.7  8013.7  8141.7  8253.7  8277.7  8453.7  8837.7  8861.7  8925.7
  8957.7  9861.7 10165.7 10189.7 10237.7 10565.7 10605.7 10645.7 10740.3 10744.6
   93.92   91.49   90.35   88.93   91.75   88.67   87.03   87.45   85.97   88.17
   87.05   87.19   89.86   89.18   86.56   87.44   95.47   95.46   87.39   87.41
   88.78   89.62   88.56    88.4   89.94   92.23   92.21   90.26   91.49   94.08
   94.53   91.49   90.59   90.58   92.99   92.29   93.14   91.26   92.01   91.36
   92.71   93.26   90.98   92.76   91.04   92.33   93.07   91.11   90.14   90.34
   91.61   90.56   91.13   93.59   90.88   90.44   89.39   86.26   88.78      94
   93.92   91.49   90.35   88.93   91.75   88.67   87.03   87.45   85.97   88.17
   87.05   87.19   89.86   89.18   86.56   87.44   87.47   87.67   87.39   87.41
   88.78   89.62   88.56    88.4   89.94   92.23   92.21   90.26   91.49   94.08
   94.53   91.49   90.59   90.58   92.99   92.29   93.14   91.26   92.01   91.36
   92.71   93.26   90.98   92.76   91.04   92.33   93.07   91.11   90.14   90.34
   91.61   90.56   91.13   93.59   90.88   90.44   89.39   86.26   88.78      94
  2359.5  2407.6  2463.6  2479.6  2615.4  3327.4  3415.4  3799.4  3863.4  4191.4
  4255.4  4439.4  4716.7  4788.7 4848.98 4875.98 4876.78 5097.88 5123.88    5167
    5207    5631    5671    5807    5839  6115.9  6387.9  6515.9  6603.9  6619.9
  6787.9  6819.9  6843.9  6915.9  6947.9  7371.9  7653.7  7685.7  7733.7  7773.7
  7789.7  7893.7  8013.7  8141.7  8253.7  8277.7  8453.7  8837.7  8861.7  8925.7
  8957.7  9861.7 10165.7 10189.7 10237.7 10565.7 10605.7 10645.7 10740.3 10744.6
   93.92   91.49   90.35   88.93   91.75   88.67   87.03   87.45   85.97   88.17
   87.05   87.19   89.86   89.18   86.56   87.44   95.47   95.46   87.39   87.41
   88.78   89.62   88.56    88.4   89.94   92.23   92.21   90.26   91.49   94.08
   94.53   91.49   90.59   90.58   92.99   92.29   93.14   91.26   92.01   91.36
   92.71   93.26   90.98   92.76   91.04   92.33   93.07   91.11   90.14   90.34
   91.61   90.56   91.13   93.59   90.88   90.44   89.39   86.26   88.78      94
   93.92   91.49   90.35   88.93   91.75   88.67   87.03   87.45   85.97   88.17
   87.05   87.19   89.86   89.18   86.56   87.44   87.47   87.67   87.39   87.41
   88.78   89.62   88.56    88.4   89.94   92.23   92.21   90.26   91.49   94.08
   94.53   91.49   90.59   90.58   92.99   92.29   93.14   91.26   92.01   91.36
   92.71   93.26   90.98   92.76   91.04   92.33   93.07   91.11   90.14   90.34
   91.61   90.56   91.13   93.59   90.88   90.44   89.39   86.26   88.78      94
Pier Skew, UpSta & Num, DnSta & Num=  ,4877.9, 2 ,4877.9, 2 , 0 , 0 , 0 ,,
       2       2
   86.44   88.49
       2       2
   86.44   88.49
Pier Skew, UpSta & Num, DnSta & Num=  ,4950.4, 2 ,4950.4, 2 , 0 , 0 , 0 ,,
     3.3     3.3
   73.73   88.47
     3.3     3.3
   73.73   88.47
Pier Skew, UpSta & Num, DnSta & Num=  ,5024.4, 2 ,5024.4, 2 , 0 , 0 , 0 ,,
     3.3     3.3
   72.21   88.46
     3.3     3.3
   72.21   88.46
BR Coef= 1 , 1 , 0 ,1.25, 0 ,,,0.8,0,2,0,
WSPro=,,,, 1 ,,,, 0 ,,,, 0 ,,,,-1 ,-1 ,-1 , 0 , 0 , 0 , 0 , 0
BR U #Sta/Elev= 168
  2359.5   93.92  2359.6   93.42  2359.8   93.42  2375.6   93.26  2407.6   91.49
  2431.6   90.69  2463.6   90.35  2479.6   88.93  2487.6   89.13  2535.6   89.92
  2543.6    90.3  2559.4   90.54  2583.4   90.89  2615.4   91.75  2991.7   90.24
  3055.4   89.98  3079.4   89.15  3095.4    89.4  3263.4   88.73  3279.4   88.22
  3327.4   88.67  3415.4   87.03  3799.4   87.45  3863.4   85.97  3938.9   86.22
  3991.4   86.39  3999.4   86.77  4079.4   87.62  4167.4   87.68  4191.4   88.17
  4199.4   88.11  4215.4   87.73  4255.4   87.05  4383.4   87.03  4407.4   87.46
  4439.4   87.19  4479.4   88.04  4591.4   88.85  4599.4   88.32  4607.4   88.24
  4636.7   89.72  4692.7   89.56  4716.7   89.86  4732.7   89.53  4748.7   89.73
  4756.7   89.48  4788.7   89.18  4804.7   88.59  4812.7   88.49  4828.7   86.86
  4838.4    87.1  4846.4   87.18 4848.98   86.56 4849.18   87.04 4850.88   87.21
 4875.89   87.43 4875.98   87.44 4876.78   87.44 4904.38   87.69 4935.38   75.99
 4950.28   74.84 4962.18    74.1 4979.68   72.18 4982.48    70.9 4999.18    70.5
 5016.18   70.63 5020.38   72.04 5024.38   74.03 5042.18   74.46 5063.98   83.12
 5077.37    87.4 5077.48   87.43 5078.88   87.88 5097.88   87.67 5123.88   87.39
 5128.28   87.75  5134.4   88.06    5143   87.79    5167   87.41    5207   88.78
    5375   89.17    5383   88.99    5631   89.62    5647   89.12    5663   88.94
    5671   88.56    5687   88.46    5703   88.83    5807    88.4    5839   89.94
  6115.9   92.23  6379.9    91.9  6387.9   92.21  6515.9   90.26  6603.9   91.49
  6611.9   92.88  6619.9   94.08  6787.9   94.53  6795.9   94.29  6803.9   93.44
  6811.9   92.14  6819.9   91.49  6843.9   90.59  6915.9   90.58  6923.9    91.2
  6931.9   92.24  6939.9   92.72  6947.9   92.99  6979.9    92.7  6995.9   92.89
  7299.9   92.73  7307.9      93  7331.9   92.89  7371.9   92.29  7509.7   92.65
  7533.7   93.11  7549.7    92.7  7581.7   92.74  7653.7   93.14  7661.7   92.33
  7669.7   91.72  7685.7   91.26  7733.7   92.01  7773.7   91.36  7789.7   92.71
  7893.7   93.26    8000   91.24  8013.7   90.98  8141.7   92.76  8245.7   91.45
  8253.7   91.04  8277.7   92.33  8453.7   93.07  8461.7   92.91  8557.7   92.09
  8709.7   91.25  8837.7   91.11  8853.7   90.32  8861.7   90.14  8909.7   90.52
  8925.7   90.34  8957.7   91.61  9621.7   91.37  9637.7    91.1  9845.7   91.23
  9861.7   90.56  9877.7   90.99 10101.7   91.38 10109.7   91.17 10165.7   91.13
 10173.7   91.46 10181.7   92.36 10189.7   93.59 10205.7   93.23 10213.7   92.14
 10229.7   91.51 10237.7   90.88 10309.7   90.69 10325.7   91.01 10565.7   90.44
 10605.7   89.39 10621.7   88.27 10629.7    87.5 10637.7   86.44 10645.7   86.26
 10669.7   86.69 10740.3   88.78 10744.6      94
BR U #Mann= 7
  2359.5      .2  2359.8      .1  2991.7     .14  3938.9      .1 4904.38    .035
 5078.88      .1    8000     .99
BR U Banks=4904.38,5078.88
BR D #Sta/Elev= 168
  2359.5   93.92  2359.6   93.42  2359.8   93.42  2375.6   93.26  2407.6   91.49
  2431.6   90.69  2463.6   90.35  2479.6   88.93  2487.6   89.13  2535.6   89.92
  2543.6    90.3  2559.4   90.54  2583.4   90.89  2615.4   91.75  2991.7   90.24
  3055.4   89.98  3079.4   89.15  3095.4    89.4  3263.4   88.73  3279.4   88.22
  3327.4   88.67  3415.4   87.03  3799.4   87.45  3863.4   85.97  3938.9   86.22
  3991.4   86.39  3999.4   86.77  4079.4   87.62  4167.4   87.68  4191.4   88.17
  4199.4   88.11  4215.4   87.73  4255.4   87.05  4383.4   87.03  4407.4   87.46
  4439.4   87.19  4479.4   88.04  4591.4   88.85  4599.4   88.32  4607.4   88.24
  4636.7   89.72  4692.7   89.56  4716.7   89.86  4732.7   89.53  4748.7   89.73
  4756.7   89.48  4788.7   89.18  4804.7   88.59  4812.7   88.49  4828.7   86.86
  4838.4    87.1  4846.4   87.18 4848.98   86.56 4849.18   87.04 4850.88   87.21
 4875.89   87.43 4875.98   87.44 4876.78   87.44 4904.38   87.69 4935.38   75.99
 4950.28   74.84 4962.18    74.1 4979.68   72.18 4982.48    70.9 4999.18    70.5
 5016.18   70.63 5020.38   72.04 5024.38   74.03 5042.18   74.46 5063.98   83.12
 5077.37    87.4 5077.48   87.43 5078.88   87.88 5097.88   87.67 5123.88   87.39
 5128.28   87.75  5134.4   88.06    5143   87.79    5167   87.41    5207   88.78
    5375   89.17    5383   88.99    5631   89.62    5647   89.12    5663   88.94
    5671   88.56    5687   88.46    5703   88.83    5807    88.4    5839   89.94
  6115.9   92.23  6379.9    91.9  6387.9   92.21  6515.9   90.26  6603.9   91.49
  6611.9   92.88  6619.9   94.08  6787.9   94.53  6795.9   94.29  6803.9   93.44
  6811.9   92.14  6819.9   91.49  6843.9   90.59  6915.9   90.58  6923.9    91.2
  6931.9   92.24  6939.9   92.72  6947.9   92.99  6979.9    92.7  6995.9   92.89
  7299.9   92.73  7307.9      93  7331.9   92.89  7371.9   92.29  7509.7   92.65
  7533.7   93.11  7549.7    92.7  7581.7   92.74  7653.7   93.14  7661.7   92.33
  7669.7   91.72  7685.7   91.26  7733.7   92.01  7773.7   91.36  7789.7   92.71
  7893.7   93.26    8000   91.24  8013.7   90.98  8141.7   92.76  8245.7   91.45
  8253.7   91.04  8277.7   92.33  8453.7   93.07  8461.7   92.91  8557.7   92.09
  8709.7   91.25  8837.7   91.11  8853.7   90.32  8861.7   90.14  8909.7   90.52
  8925.7   90.34  8957.7   91.61  9621.7   91.37  9637.7    91.1  9845.7   91.23
  9861.7   90.56  9877.7   90.99 10101.7   91.38 10109.7   91.17 10165.7   91.13
 10173.7   91.46 10181.7   92.36 10189.7   93.59 10205.7   93.23 10213.7   92.14
 10229.7   91.51 10237.7   90.88 10309.7   90.69 10325.7   91.01 10565.7   90.44
 10605.7   89.39 10621.7   88.27 10629.7    87.5 10637.7   86.44 10645.7   86.26
 10669.7   86.69 10740.3   88.78 10744.6      94
BR D #Mann= 7
  2359.5      .2  2359.8      .1  2991.7     .14  3938.9      .1 4904.38    .035
 5078.88      .1    8000     .99
BR D Banks=4904.38,5078.88
BC Design=,, 0 ,, 0 ,,,,,,
BC HTab HWMax=94.54
BC Use User HTab Curves=0
BC User HTab FreeFlow(D)= 0

Type RM Length L Ch R = 1 ,169291.2,273.7,273.7,273.7
BEGIN DESCRIPTION:
Downstream Section of Bridge/Culvert/Weir
END DESCRIPTION:
XS GIS Cut Line= 6
      3101954.02     13915282.53      3101937.86     13915032.12
      3101756.96     13913039.67      3101727.74     13912792.67
      3101888.62     13912547.27      3101995.84     13906956.93
#Sta/Elev= 30
  2359.5   93.91  2359.8   93.41  2479.6   88.92  2615.4   91.74  2991.7   90.23
  3938.9   86.21  4716.7   89.85 4904.38   87.68 4935.38   75.98 4999.18   70.49
 5042.18   74.45 5078.88   87.87    5807   88.39  6115.9   92.22  6515.9   90.25
  6603.9   91.48  6619.9   94.07  6787.9   94.52  6843.9   90.58  6947.9   92.98
    8000   91.23  8453.7   93.06  9861.7   90.55 10165.7   91.12 10189.7   93.58
 10237.7   90.87 10565.7   90.43 10645.7   86.25 10740.3   88.77 10744.6   93.99
#Mann= 7 , 1 , 0
  2359.5      .2       0  2359.8      .1       0  2991.7     .14       0
  3938.9      .1       0 4904.38    .035       0 5078.88      .1       0
    8000     .99       0
#XS Ineff= 2 , 0
       0 4904.38   87.69 5078.88       0   87.88
Permanent Ineff=
       F       F
Bank Sta=4904.38,5078.88
XS Rating Curve= 0 ,0
Exp/Cntr=0.5,0.3

Type RM Length L Ch R = 1 ,169017.5,246.6,255.4,269.5
BEGIN DESCRIPTION:
Cross Section 169017.5-Interpolated
END DESCRIPTION:
XS GIS Cut Line= 6
      3102124.47     13915315.71      3102058.33     13914717.76
      3101986.13     13913026.42      3102098.63     13912598.92
      3102155.64      13911186.9      3102188.23     13906942.73
#Sta/Elev= 30
  2467.7   93.63  2647.4   90.99  3112.1   90.73  3450.5   88.36    4028   87.97
  4169.3   89.73  4219.3   86.92  4399.3   85.66  4832.2   88.16  4892.2   85.75
  4927.6   83.03    4982   70.25  5017.7   70.55  5109.3   89.42  5354.3   92.52
  5744.3   88.19  5914.3   89.05  5964.3   98.29  6134.3   97.77  6174.3   89.95
  6194.3   90.34  6234.3  101.88  6454.3  102.76  6514.3   91.79  8541.6   91.53
  8877.3   91.18 10677.4   89.75 10727.4   86.17 10857.3   88.72 10861.7      94
#Mann= 9 , 1 , 0
  2467.7      .2       0  2647.4      .1       0  3112.1     .03       0
  3450.5     .14       0    4028      .1       0  4892.2    .035       0
  5109.3      .1       0  8541.6     .08       0  8877.3     .99       0
#XS Ineff= 2 , 0
       0    4160      94    5962       0    98.3
Permanent Ineff=
       F       F
Bank Sta=4892.2,5109.3
XS Rating Curve= 0 ,0
Exp/Cntr=0.5,0.3

Type RM Length L Ch R = 1 ,168762.1,56,56,56
BEGIN DESCRIPTION:
Upstream Section of Bridge/Culvert/Weir
END DESCRIPTION:
XS GIS Cut Line= 6
       3102202.6     13915173.56      3102330.63     13912131.67
       3102458.7      13911079.7      3102550.18     13910576.58
      3102705.68     13909881.36      3103680.47      13907159.6
#Sta/Elev= 30
  2646.4   94.01  2656.4   92.17  3118.3   91.06  4053.9   86.77  4427.4   85.38
  4895.9   88.23    4982   70.02  5017.7   70.32  5052.9   75.61  5109.3   89.19
  5633.9   90.94  5694.3    87.6  5724.4    90.9  5906.5   93.03  6088.9   88.88
  6714.1    92.7  6993.7   93.13  7172.3   90.02  7685.1   92.35  7833.7    84.7
  7878.7   89.33  7956.7   91.54  8561.8   91.05  8937.1   88.44  9183.7   91.19
   10000    90.8 10608.7   90.36 10732.1      87 10861.9   88.75 10866.4   94.01
#Mann= 8 , 1 , 0
  2646.4      .2       0  2656.4      .1       0  3118.3     .14       0
  4053.9      .1       0  4895.9     .02       0  5109.3      .1       0
  8561.8      .2       0   10000     .99       0
#XS Ineff= 4 ,-1
    2663    4800      93  4800.1    4915    89.3    5105    5200    89.3
  5200.1   10862      93
Permanent Ineff=
       F       F       F       F
Bank Sta=4895.9,5109.3
XS Rating Curve= 0 ,0
Exp/Cntr=0.5,0.3