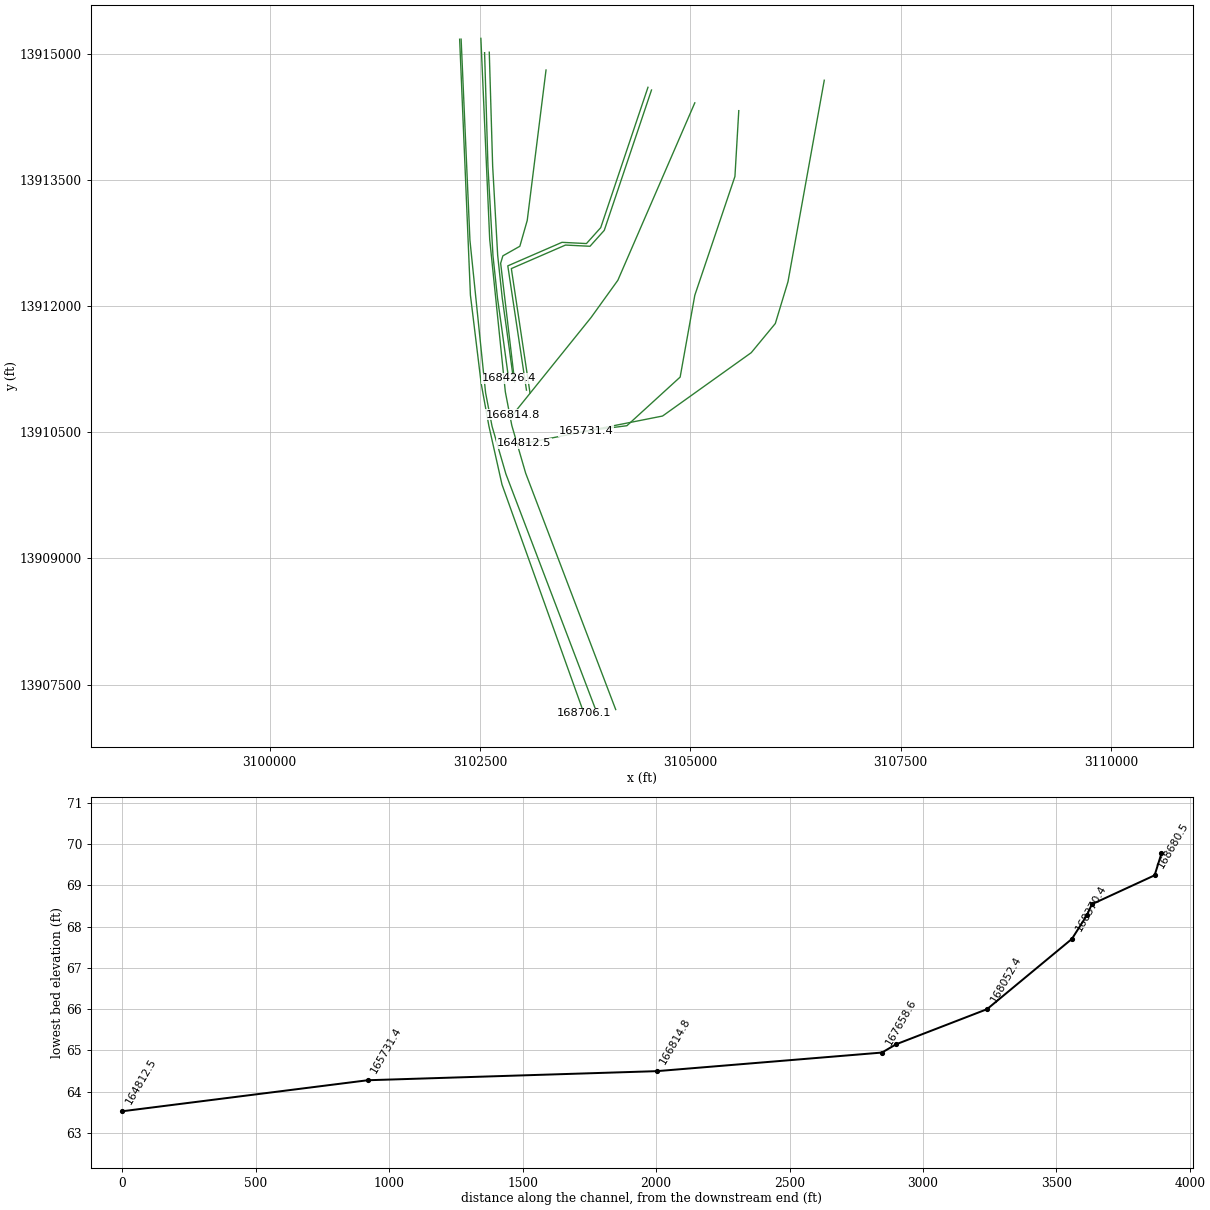
HEC-RAS study P100-00-00.prj: P100-00-00

--- P100-00-00.g01 (geometry) --- (continued)

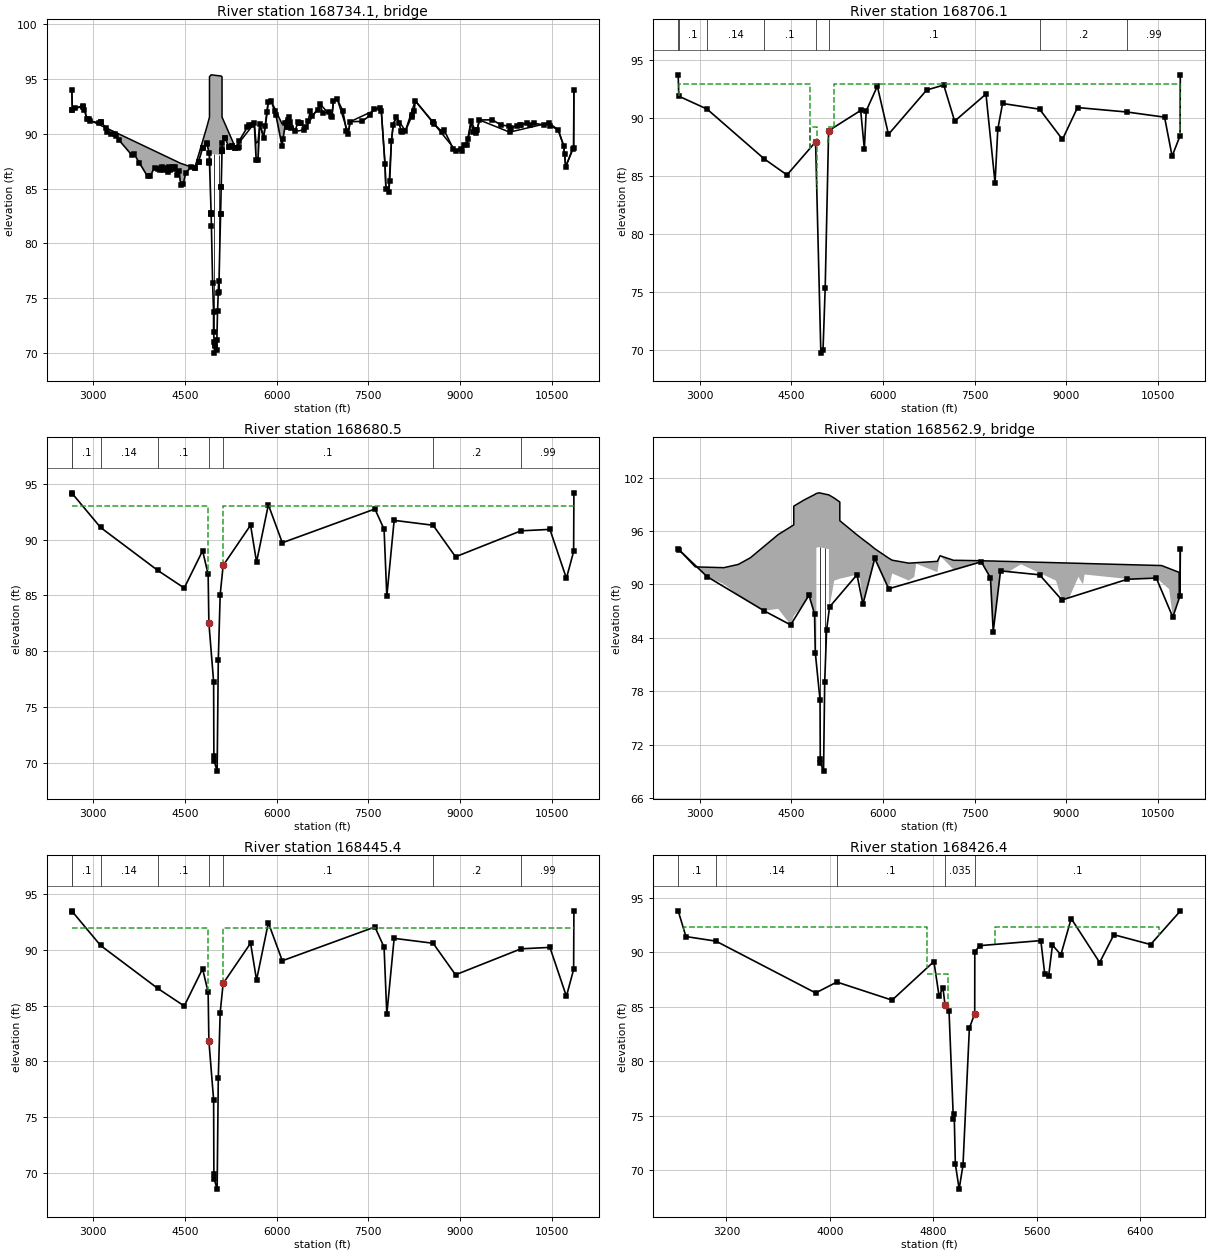
Type RM Length L Ch R = 3 ,168734.1,,,
BEGIN DESCRIPTION:
I-45 SOUTHBOUND FRONTAGE ROAD
Structure ID: P00-59
END DESCRIPTION:
Bridge Culvert--1,0,-1,-1, 0
Deck Dist Width WeirC Skew NumUp NumDn MinLoCord MaxHiCord MaxSubmerge Is_Ogee
10,36,2.6,0, 60, 60, , , 0.95, 0, 1,1,,
  2646.4  2656.4  2834.1  2896.8    3362  3887.3  4337.4  4427.4  4657.6  4857.6
  4895.9 4900.69  4900.8 4927.91    4928 5092.59  5092.7  5106.1 5106.21  5109.3
  5324.5  5633.9  5664.1  5694.3  5724.4  5786.6  5860.8  5906.5  6088.9  6197.1
  6301.1  6452.1  6714.1  6903.7  6930.9  6993.7  7172.3  7202.5  7685.1  7713.7
  7773.7  7788.7  7833.7  7878.7  7908.7  7956.7  8107.5  8268.7  8937.1  9108.7
  9183.7    9269  9318.7  9813.7 10458.7 10608.7 10698.7 10732.1 10861.9 10866.4
      94   92.16   92.54   91.34   90.12   88.73   87.54    87.3   86.86   90.62
    91.4   91.49   95.19   95.36   95.36   95.25   95.25   95.18   91.48   91.47
   88.74   90.94   89.15   89.27    90.9   89.65   92.85   93.03   90.89   91.48
    90.2   90.35   92.69   91.51   93.01   93.12   90.01   91.09   92.34   92.07
   87.23      85   84.69   89.32   90.81   91.53   90.25      93   88.43      89
   91.18   90.06   91.25   90.14   90.98   90.35    88.9   86.99   88.74      94
      94   92.16   92.54   91.31   89.97    86.1   86.99   85.37   86.85   89.11
   88.22    87.4   87.38   82.71   88.16   88.05   85.18   88.41   88.44   89.18
   88.73   90.93   87.64   87.59   90.89   89.62   92.84   93.02   88.87   91.48
    90.2   90.35   92.69   91.51   93.01   93.12   90.01   91.09   92.34   92.07
   87.23      85   84.69   89.32   90.81   91.53   90.25      93   88.43      89
   91.18   90.06   91.25   90.14   90.98   90.35    88.9   86.99   88.74      94
  2646.4  2656.4  2834.1  2896.8    3362  3887.3  4337.4  4427.4  4657.6  4857.6
  4895.9 4900.69  4900.8 4927.91    4928 5092.59  5092.7  5106.1 5106.21  5109.3
  5324.5  5633.9  5664.1  5694.3  5724.4  5786.6  5860.8  5906.5  6088.9  6197.1
  6301.1  6452.1  6714.1  6903.7  6930.9  6993.7  7172.3  7202.5  7685.1  7713.7
  7773.7  7788.7  7833.7  7878.7  7908.7  7956.7  8107.5  8268.7  8937.1  9108.7
  9183.7    9269  9318.7  9813.7 10458.7 10608.7 10698.7 10732.1 10861.9 10866.4
      94   92.16   92.54   91.34   90.12   88.73   87.54    87.3   86.86   90.62
    91.4   91.49   95.19   95.36   95.36   95.25   95.25   95.18   91.48   91.47
   88.74   90.94   89.15   89.27    90.9   89.65   92.85   93.03   90.89   91.48
    90.2   90.35   92.69   91.51   93.01   93.12   90.01   91.09   92.34   92.07
   87.23      85   84.69   89.32   90.81   91.53   90.25      93   88.43      89
   91.18   90.06   91.25   90.14   90.98   90.35    88.9   86.99   88.74      94
   93.97   92.13   92.51   91.28   89.94   86.07   86.96   85.34   86.82   89.08
   88.19   87.37   87.35   82.68   88.13   88.02   85.15   88.38   88.41   89.15
    88.7    90.9   87.61   87.56   90.86   89.59   92.81   92.99   88.84   91.45
   90.17   90.32   92.66   91.48   92.98   93.09   89.98   91.06   92.31   92.04
    87.2   84.97   84.66   89.29   90.78    91.5   90.22   92.97    88.4   88.97
   91.15   90.03   91.22   90.11   90.95   90.32   88.87   86.96   88.71   93.97
Pier Skew, UpSta & Num, DnSta & Num=  ,4968, 2 ,4968, 2 , 0 , 0 , 0 ,,
       2       2
   70.84   89.29
       2       2
   70.81   89.26
Pier Skew, UpSta & Num, DnSta & Num=  ,5052.9, 2 ,5052.9, 2 , 0 , 0 , 0 ,,
       2       2
   74.84   89.26
       2       2
   74.81   89.23
Abutment Skew #Up #Dn= , 2 , 2
  4927.8  4932.2
   88.16   81.59
  4927.8  4932.2
   88.13   81.56
Abutment Skew #Up #Dn= , 2 , 2
  5082.4 5092.79
    82.7   88.05
  5082.4 5092.79
   82.67   88.02
BR Coef= 1 , 1 , 0 ,1.25, 0 ,,,0.8,-1,2,0,
WSPro=,,,, 1 ,,,, 0 ,,,, 0 ,,,,-1 ,-1 ,-1 , 0 , 0 , 0 , 0 , 0
BR U #Sta/Elev= 198
  2646.4      94  2656.4   92.16  2656.8   92.17  2695.6   92.33  2834.1   92.54
    2838   92.46  2851.8   92.19  2896.8   91.31  2926.9    91.3  2941.9   91.14
  3091.9   91.01  3118.3   91.05  3121.9   91.06  3203.7   90.55    3227   90.16
    3287   89.94    3362   89.97    3377   89.81    3422    89.4  3625.7   88.07
  3669.8   88.11  3752.2   87.35  3887.3    86.1  3932.3   86.16    4001   86.91
  4053.9   86.76  4087.4   86.67  4102.5   86.91  4127.4   86.98  4157.4   86.67
  4202.4   86.85  4217.4   86.52  4232.4   86.95  4247.4   86.71    4299   86.97
  4314.1   86.77  4337.4   86.99  4367.4   86.23  4404.8   86.57  4427.4   85.37
  4472.4   85.46  4510.6   86.38  4591.1   86.94  4657.6   86.85  4658.4   86.86
    4722   87.45  4722.3   87.45  4789.2   88.71  4789.8   88.72    4854   89.09
  4857.6   89.11  4895.9   88.22  4899.8   87.55 4900.69    87.4  4900.8   87.38
 4900.91   87.36  4927.6   82.79  4927.8   82.74 4927.91   82.71    4928   82.69
  4932.2   81.59  4952.2   76.36  4967.3   73.78    4968   71.93  4978.3   71.02
    4982   70.01  4997.6   70.68    4999   70.74  5017.7   70.31  5021.7   71.24
  5032.5   73.82  5044.4   75.49  5052.4   76.62  5052.9    75.6  5082.2   82.65
  5082.4    82.7 5092.59   85.15  5092.7   85.18 5105.99   88.38  5106.1   88.41
 5106.21   88.44    5107   88.63  5109.3   89.18    5155   89.58  5155.8   89.59
  5216.4   88.82  5217.3   88.81  5272.9   88.92  5273.2   88.92  5324.5   88.73
  5324.6   88.73  5374.9   88.71  5376.2   88.79  5385.1   89.33  5522.2   90.61
  5541.6   90.78  5589.7   90.75  5633.9   90.93  5664.1   87.64  5694.3   87.59
  5724.4   90.89  5786.6   89.62  5815.2    90.7  5845.6   91.99  5860.8   92.84
  5906.5   93.02  5967.3   92.08  5988.6   91.68  6088.9   88.87  6104.1   89.51
    6145   90.93    6165   90.59  6165.3    90.6    6193   91.23  6197.1   91.48
  6211.2   91.06  6240.8   90.51  6301.1    90.2    6346   91.05  6361.5   90.97
  6386.7   90.94  6406.8   90.93  6452.1   90.35  6482.3   90.57  6516.7   91.17
  6550.7   92.04  6572.8   91.62  6678.5   92.17  6714.1   92.69  6753.7   91.86
  6858.7   91.98  6885.7   91.59  6903.7   91.51  6930.9   93.01  6993.7   93.12
  7083.7   92.07  7143.7   90.26  7172.3   90.01  7202.5   91.09  7398.7   91.12
  7533.7   91.68  7594.6   92.28  7685.1   92.34  7713.7   92.07  7773.7   87.23
  7788.7      85  7833.7   84.69  7851.1   85.72  7878.7   89.32  7908.7   90.81
  7956.7   91.53  7998.7   90.98  8040.3   90.28  8047.2   90.13  8107.5   90.25
  8208.7   91.55  8223.7   91.71  8253.7   92.11  8268.7      93  8553.7    91.1
  8561.8   91.04  8583.7   90.86  8703.7   90.18    8741   90.33  8890.5   88.62
  8937.1   88.43  9012.5   88.57  9027.6   88.45  9063.7   88.98  9108.7      89
  9138.7   89.49  9183.7   91.18  9213.7   90.15  9243.7   90.31    9269   90.06
  9284.1   90.34  9318.7   91.25  9528.7   91.26  9676.2   90.79  9798.7   90.69
  9813.7   90.14  9828.7   90.53  9932.7    90.7  9977.9   90.75   10000   90.79
 10098.7   90.97 10143.8    90.8 10218.7   90.94 10383.7   90.79 10458.7   90.98
 10475.7   90.74 10608.7   90.35 10698.7    88.9 10713.7   88.17 10732.1   86.99
 10844.7    88.6 10861.9   88.74 10866.4      94
BR U #Mann= 8
  2646.4      .2  2656.4      .1  3118.3     .14  4053.9      .1  4895.9     .02
  5109.3      .1  8561.8      .2   10000     .99
BR U Banks=4895.9,5109.3
BR D #Sta/Elev= 198
  2646.4   93.97  2656.4   92.13  2656.8   92.14  2695.6    92.3  2834.1   92.51
    2838   92.43  2851.8   92.16  2896.8   91.28  2926.9   91.27  2941.9   91.11
  3091.9   90.98  3118.3   91.02  3121.9   91.03  3203.7   90.52    3227   90.13
    3287   89.91    3362   89.94    3377   89.78    3422   89.37  3625.7   88.04
  3669.8   88.08  3752.2   87.32  3887.3   86.07  3932.3   86.13    4001   86.88
  4053.9   86.73  4087.4   86.64  4102.5   86.88  4127.4   86.95  4157.4   86.64
  4202.4   86.82  4217.4   86.49  4232.4   86.92  4247.4   86.68    4299   86.94
  4314.1   86.74  4337.4   86.96  4367.4    86.2  4404.8   86.54  4427.4   85.34
  4472.4   85.43  4510.6   86.35  4591.1   86.91  4657.6   86.82  4658.4   86.83
    4722   87.42  4722.3   87.42  4789.2   88.68  4789.8   88.69    4854   89.06
  4857.6   89.08  4895.9   88.19  4899.8   87.52 4900.69   87.37  4900.8   87.35
 4900.91   87.33  4927.6   82.76  4927.8   82.71 4927.91   82.68    4928   82.66
  4932.2   81.56  4952.2   76.33  4967.3   73.75    4968    71.9  4978.3   70.99
    4982   69.98  4997.6   70.65    4999   70.71  5017.7   70.28  5021.7   71.21
  5032.5   73.79  5044.4   75.46  5052.4   76.59  5052.9   75.57  5082.2   82.62
  5082.4   82.67 5092.59   85.12  5092.7   85.15 5105.99   88.35  5106.1   88.38
 5106.21   88.41    5107    88.6  5109.3   89.15    5155   89.55  5155.8   89.56
  5216.4   88.79  5217.3   88.78  5272.9   88.89  5273.2   88.89  5324.5    88.7
  5324.6    88.7  5374.9   88.68  5376.2   88.76  5385.1    89.3  5522.2   90.58
  5541.6   90.75  5589.7   90.72  5633.9    90.9  5664.1   87.61  5694.3   87.56
  5724.4   90.86  5786.6   89.59  5815.2   90.67  5845.6   91.96  5860.8   92.81
  5906.5   92.99  5967.3   92.05  5988.6   91.65  6088.9   88.84  6104.1   89.48
    6145    90.9    6165   90.56  6165.3   90.57    6193    91.2  6197.1   91.45
  6211.2   91.03  6240.8   90.48  6301.1   90.17    6346   91.02  6361.5   90.94
  6386.7   90.91  6406.8    90.9  6452.1   90.32  6482.3   90.54  6516.7   91.14
  6550.7   92.01  6572.8   91.59  6678.5   92.14  6714.1   92.66  6753.7   91.83
  6858.7   91.95  6885.7   91.56  6903.7   91.48  6930.9   92.98  6993.7   93.09
  7083.7   92.04  7143.7   90.23  7172.3   89.98  7202.5   91.06  7398.7   91.09
  7533.7   91.65  7594.6   92.25  7685.1   92.31  7713.7   92.04  7773.7    87.2
  7788.7   84.97  7833.7   84.66  7851.1   85.69  7878.7   89.29  7908.7   90.78
  7956.7    91.5  7998.7   90.95  8040.3   90.25  8047.2    90.1  8107.5   90.22
  8208.7   91.52  8223.7   91.68  8253.7   92.08  8268.7   92.97  8553.7   91.07
  8561.8   91.01  8583.7   90.83  8703.7   90.15    8741    90.3  8890.5   88.59
  8937.1    88.4  9012.5   88.54  9027.6   88.42  9063.7   88.95  9108.7   88.97
  9138.7   89.46  9183.7   91.15  9213.7   90.12  9243.7   90.28    9269   90.03
  9284.1   90.31  9318.7   91.22  9528.7   91.23  9676.2   90.76  9798.7   90.66
  9813.7   90.11  9828.7    90.5  9932.7   90.67  9977.9   90.72   10000   90.76
 10098.7   90.94 10143.8   90.77 10218.7   90.91 10383.7   90.76 10458.7   90.95
 10475.7   90.71 10608.7   90.32 10698.7   88.87 10713.7   88.14 10732.1   86.96
 10844.7   88.57 10861.9   88.71 10866.4   93.97
BR D #Mann= 8
  2646.4      .2  2656.4      .1  3118.3     .14  4053.9      .1  4895.9     .02
  5109.3      .1  8561.8      .2   10000     .99
BR D Banks=4895.9,5109.3
BC Design=,, 0 ,, 0 ,,,,,,
BC HTab HWMax=94.01
BC Use User HTab Curves=0
BC User HTab FreeFlow(D)= 0

Type RM Length L Ch R = 1 ,168706.1,25.65,25.65,25.65
BEGIN DESCRIPTION:
Downstream Section of Bridge/Culvert/Weir
END DESCRIPTION:
XS GIS Cut Line= 6
      3102258.57     13915171.76      3102386.61     13912129.87
      3102514.68      13911077.9      3102606.16     13910574.78
      3102761.66     13909879.56      3103736.44      13907157.8
#Sta/Elev= 30
  2646.4   93.76  2656.4   91.92  3118.3   90.81  4053.9   86.52  4427.4   85.13
  4895.9   87.98    4982   69.77  5017.7   70.07  5052.9   75.36  5109.3   88.94
  5633.9   90.69  5694.3   87.35  5724.4   90.65  5906.5   92.78  6088.9   88.63
  6714.1   92.45  6993.7   92.88  7172.3   89.77  7685.1    92.1  7833.7   84.45
  7878.7   89.08  7956.7   91.29  8561.8    90.8  8937.1   88.19  9183.7   90.94
   10000   90.55 10608.7   90.11 10732.1   86.75 10861.9    88.5 10866.4   93.76
#Mann= 8 , 1 , 0
  2646.4      .2       0  2656.4      .1       0  3118.3     .14       0
  4053.9      .1       0  4895.9     .02       0  5109.3      .1       0
  8561.8      .2       0   10000     .99       0
#XS Ineff= 4 ,-1
    2663    4800      93  4800.1    4915    89.3    5105    5200    89.3
  5200.1   10862      93
Permanent Ineff=
       F       F       F       F
Bank Sta=4895.9,5109.3
XS Rating Curve= 0 ,0
Exp/Cntr=0.5,0.3

Type RM Length L Ch R = 1 ,168680.5,235.1,235.1,235.1
BEGIN DESCRIPTION:
Upstream Section of Bridge/Culvert/Weir
END DESCRIPTION:
XS GIS Cut Line= 6
      3102276.12     13915172.56      3102380.92     13912782.38
      3102566.84     13910969.96      3102643.68      13910570.7
      3102808.33     13910003.55      3103879.07     13907193.11
#Sta/Elev= 30
  2646.4   94.21  2656.4   94.13  3118.3    91.1  4053.9   87.25  4487.4   85.67
  4787.8   89.01  4878.7   86.91  4890.8   82.55  4968.7   77.24  4972.5   70.61
  4975.6   70.19    5026   69.24  5044.9   79.21  5075.9   85.08  5124.3   87.69
  5573.5   91.31  5671.1      88  5864.5   93.14  6092.8   89.73  7608.7   92.76
  7758.7   90.95  7803.7   84.92  7923.7   91.74  8561.8    91.3  8928.7   88.47
   10000    90.8 10473.7   90.93 10743.7   86.54 10861.9   88.95 10866.4   94.21
#Mann= 8 , 1 , 0
  2646.4      .2       0  2656.4      .1       0  3118.3     .14       0
  4053.9      .1       0  4890.8     .02       0  5124.3      .1       0
  8561.8      .2       0   10000     .99       0
#XS Ineff= 2 , 0
       0    4876      93    5125       0      93
Permanent Ineff=
       F       F
Bank Sta=4890.8,5124.3
XS Rating Curve= 0 ,0
Exp/Cntr=0.5,0.3

Type RM Length L Ch R = 3 ,168562.9,,,
BEGIN DESCRIPTION:
INTERSTATE ROUTE 45
Structure ID: POO-58
END DESCRIPTION:
Bridge Culvert--1,0,-1,-1, 0
Deck Dist Width WeirC Skew NumUp NumDn MinLoCord MaxHiCord MaxSubmerge Is_Ogee
10,215.1,2.6,0, 60, 60, , , 0.95, 0, 1,1,,
  2646.4  2927.2  3392.8  3632.1  3827.3  3930.6  4283.9  4487.4 4538.39  4538.5
    4698  4787.8  4818.5  4833.5  4878.7  4890.8 4908.31  4908.4  4956.4 5114.49
  5114.6  5200.9  5292.6 5292.71  5573.5  5618.8  5671.1  5784.8  5864.5  6092.8
  6149.8  6421.9  6512.4  6542.6  6888.7  6933.7  7158.7  7188.7  7608.7  7758.7
  7775.6  7803.7  7848.7  7863.7  7923.7  8058.7  8258.3  8831.5  8928.7  9048.7
  9198.7  9273.7  9299.1 10558.9 10683.7 10743.7 10847.4 10848.7 10861.9 10866.4
      94   91.98   91.89   92.26      93   93.59   95.61   96.48    96.7    98.8
   99.46   99.78   99.89   99.94   100.1  100.15  100.23  100.23   100.3  100.06
  100.06   99.71   99.27   97.17   95.58   95.34   95.06   94.47   94.02   92.96
   92.73    92.4   92.44   92.45    92.6   93.23   92.71   92.72   92.67   92.64
   92.64   92.64   92.63   92.62   92.61   92.59   92.55   92.45   92.43   92.41
   92.38   92.37   92.36   92.13    91.8   91.64   91.36    88.8   88.74      94
      94    91.3   90.05   87.77   87.82   86.22   87.27   85.46   86.47   86.47
   86.74    88.8   88.44   86.34    86.7   82.34   81.42   94.13    94.2   93.96
   86.96   90.43   90.65   90.65    91.1   90.93   87.79   89.53   92.93   89.52
   91.24   90.44   90.86   92.34   91.39   93.22   89.64    90.9   92.55   90.74
   86.89   84.71   85.27   87.65   91.53   89.85   92.27   90.43   88.26   88.44
   90.86   90.01   91.12   90.23   89.48   86.33   88.77    88.8   88.74      94
  2646.4  2927.2  3392.8  3632.1  3827.3  3930.6  4283.9  4487.4 4538.39  4538.5
    4698  4787.8  4818.5  4833.5  4878.7  4890.8 4908.31  4908.4  4956.4 5114.49
  5114.6  5200.9  5292.6 5292.71  5573.5  5618.8  5671.1  5784.8  5864.5  6092.8
  6149.8  6421.9  6512.4  6542.6  6888.7  6933.7  7158.7  7188.7  7608.7  7758.7
  7775.6  7803.7  7848.7  7863.7  7923.7  8058.7  8258.3  8831.5  8928.7  9048.7
  9198.7  9273.7  9299.1 10558.9 10683.7 10743.7 10847.4 10848.7 10861.9 10866.4
      94   91.98   91.89   92.26      93   93.59   95.61   96.48    96.7    98.8
   99.46   99.78   99.89   99.94   100.1  100.15  100.23  100.23   100.3  100.06
  100.06   99.71   99.27   97.17   95.58   95.34   95.06   94.47   94.02   92.96
   92.73    92.4   92.44   92.45    92.6   93.23   92.71   92.72   92.67   92.64
   92.64   92.64   92.63   92.62   92.61   92.59   92.55   92.45   92.43   92.41
   92.38   92.37   92.36   92.13    91.8   91.64   91.36    88.8   88.74      94
   93.65   90.95    89.7   87.42   87.47   85.87   86.92   85.11   86.12   86.12
   86.39   88.45   88.09   85.99   86.35   81.99   81.07   93.78   93.85   93.61
   86.61   90.08    90.3    90.3   90.75   90.58   87.44   89.18   92.58   89.17
   90.89   90.09   90.51   91.99   91.04   92.87   89.29   90.55    92.2   90.39
   86.54   84.36   84.92    87.3   91.18    89.5   91.92   90.08   87.91   88.09
   90.51   89.66   90.77   89.88   89.13   85.98   88.42   88.45   88.39   93.65
Pier Skew, UpSta & Num, DnSta & Num=  ,4968.7, 2 ,4968.7, 2 , 0 , 0 , 0 ,,
       2       2
   74.29   95.18
       2       2
   73.94   94.83
Pier Skew, UpSta & Num, DnSta & Num=  ,5055.5, 2 ,5055.5, 2 , 0 , 0 , 0 ,,
       2       2
   77.89   95.08
       2       2
   77.54   94.73
BR Coef= 1 , 1 , 0 ,1.25, 0 ,,,0.8,0,2,0,
WSPro=,,,, 1 ,,,, 0 ,,,, 0 ,,,,-1 ,-1 ,-1 , 0 , 0 , 0 , 0 , 0
BR U #Sta/Elev= 30
  2646.4      94  2656.4   93.92  3118.3   90.89  4053.9   87.04  4487.4   85.46
  4787.8    88.8  4878.7    86.7  4890.8   82.34  4968.7   77.03  4972.5    70.4
  4975.6   69.98    5026   69.03  5044.9      79  5075.9   84.87  5124.3   87.48
  5573.5    91.1  5671.1   87.79  5864.5   92.93  6092.8   89.52  7608.7   92.55
  7758.7   90.74  7803.7   84.71  7923.7   91.53  8561.8   91.09  8928.7   88.26
   10000   90.59 10473.7   90.72 10743.7   86.33 10861.9   88.74 10866.4      94
BR U #Mann= 8
  2646.4      .2  2656.4      .1  3118.3     .14  4053.9      .1  4890.8     .02
  5124.3      .1  8561.8      .2   10000     .99
BR U Banks=4890.8,5124.3
BR D #Sta/Elev= 30
  2646.4   93.65  2656.4   93.57  3118.3   90.54  4053.9   86.69  4487.4   85.11
  4787.8   88.45  4878.7   86.35  4890.8   81.99  4968.7   76.68  4972.5   70.05
  4975.6   69.63    5026   68.68  5044.9   78.65  5075.9   84.52  5124.3   87.13
  5573.5   90.75  5671.1   87.44  5864.5   92.58  6092.8   89.17  7608.7    92.2
  7758.7   90.39  7803.7   84.36  7923.7   91.18  8561.8   90.74  8928.7   87.91
   10000   90.24 10473.7   90.37 10743.7   85.98 10861.9   88.39 10866.4   93.65
BR D #Mann= 8
  2646.4      .2  2656.4      .1  3118.3     .14  4053.9      .1  4890.8     .02
  5124.3      .1  8561.8      .2   10000     .99
BR D Banks=4890.8,5124.3
BC Design=,, 0 ,, 0 ,,,,,,
BC HTab HWMax=94.21
BC Use User HTab Curves=0
BC User HTab FreeFlow(D)= 0

Type RM Length L Ch R = 1 ,168445.4,18.95,18.95,18.95
BEGIN DESCRIPTION:
Downstream Section of Bridge/Culvert/Weir
END DESCRIPTION:
XS GIS Cut Line= 6
      3102511.01     13915182.51       3102615.8     13912792.34
      3102801.72     13910979.92      3102878.56     13910580.66
      3103043.21     13910013.51      3104113.96     13907203.07
#Sta/Elev= 30
  2646.4   93.51  2656.4   93.43  3118.3    90.4  4053.9   86.55  4487.4   84.97
  4787.8   88.31  4878.7   86.21  4890.8   81.85  4968.7   76.54  4972.5   69.91
  4975.6   69.49    5026   68.54  5044.9   78.51  5075.9   84.38  5124.3   86.99
  5573.5   90.61  5671.1    87.3  5864.5   92.44  6092.8   89.03  7608.7   92.06
  7758.7   90.25  7803.7   84.22  7923.7   91.04  8561.8    90.6  8928.7   87.77
   10000    90.1 10473.7   90.23 10743.7   85.84 10861.9   88.25 10866.4   93.51
#Mann= 8 , 1 , 0
  2646.4      .2       0  2656.4      .1       0  3118.3     .14       0
  4053.9      .1       0  4890.8     .02       0  5124.3      .1       0
  8561.8      .2       0   10000     .99       0
#XS Ineff= 2 , 0
       0    4876      92    5125       0      92
Permanent Ineff=
       F       F
Bank Sta=4890.8,5124.3
XS Rating Curve= 0 ,0
Exp/Cntr=0.5,0.3

Type RM Length L Ch R = 1 ,168426.4,56,56,56
BEGIN DESCRIPTION:
Upstream Section of Bridge/Culvert/Weir
END DESCRIPTION:
XS GIS Cut Line= 6
       3102555.1     13915011.97      3102595.18     13913659.99
      3102654.98     13912596.74       3102709.1     13912090.06
        3102758.      13911742.6      3102839.91     13911142.01
#Sta/Elev= 30
  2826.4   93.79  2886.4   91.43  3118.9   91.01  3889.8   86.26  4053.9   87.26
    4481    85.6  4804.5   89.14  4844.5   85.97  4874.5   86.74  4890.6   85.14
  4921.4   84.63  4954.9   74.74  4961.4   75.13  4970.4   70.58  4999.8   68.27
  5029.5   70.47    5079   83.03  5120.2   84.37  5120.9   90.06  5162.4    90.6
  5631.6   91.06  5661.6   88.03  5691.6   87.78  5721.6   90.65  5786.6   89.76
  5866.6   93.08  6086.6   89.05  6196.6    91.6  6480.5    90.7  6710.5   93.77
#Mann= 5 , 1 , 0
  2826.4      .1       0  3118.9     .14       0  4053.9      .1       0
  4890.6    .035       0  5120.2      .1       0
#XS Ineff= 3 ,-1
    2872    4750    92.3  4750.1    4910      88    5275    6542    92.3
Permanent Ineff=
       F       F       F
Bank Sta=4890.6,5120.2
XS Rating Curve= 0 ,0
Exp/Cntr=0.5,0.3

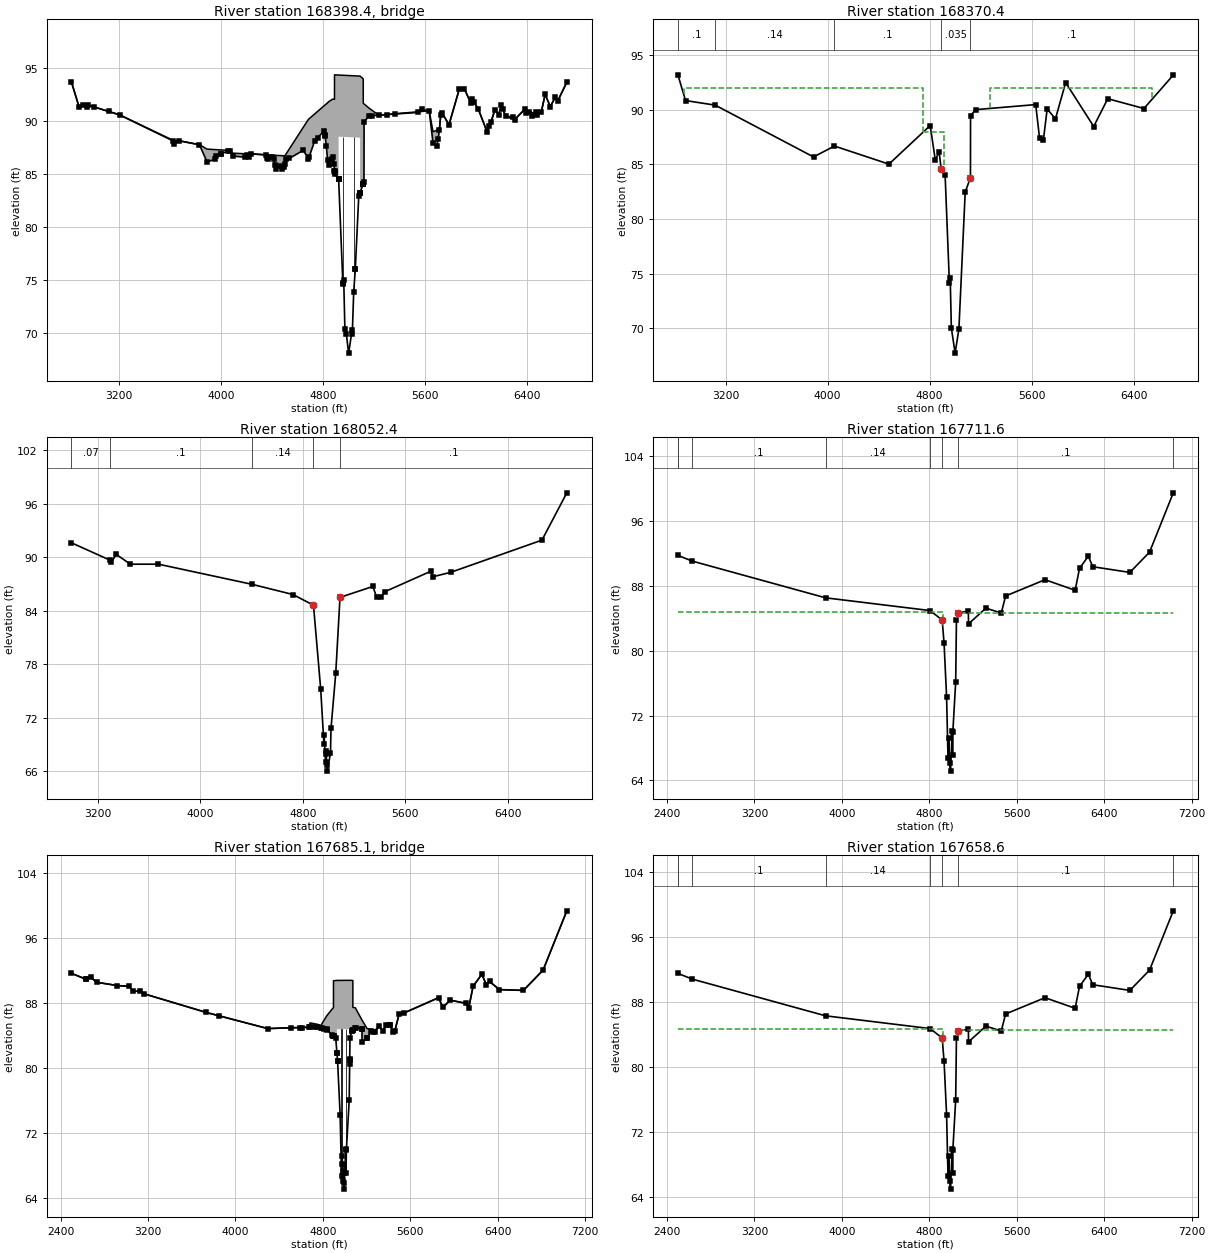
Type RM Length L Ch R = 3 ,168398.4,,,
BEGIN DESCRIPTION:
I-45 NORTHBOUND FRONTAGE ROAD
Structure ID: P00-57
END DESCRIPTION:
Bridge Culvert--1,0,-1,-1, 0
Deck Dist Width WeirC Skew NumUp NumDn MinLoCord MaxHiCord MaxSubmerge Is_Ogee
10,36,2.6,0, 60, 60, , , 0.95, 0, 1,1,,
  2826.4  2886.4  2956.4  3203.7  3633.7  3669.8  3829.8  3889.8    4071    4091
    4401    4431    4481    4500  4644.5  4684.5  4734.5  4804.5  4814.5  4834.5
  4844.5  4874.5 4888.89    4889 4920.81  4920.9 5089.49  5089.6  5114.4 5114.51
  5120.2  5120.9  5162.4  5235.7  5631.6  5661.6  5691.6  5711.6  5721.6  5731.6
  5786.6  5866.6  5906.6  5956.6  5966.6  6016.6  6086.6  6146.6  6176.6  6196.6
  6230.5  6300.5  6380.5  6480.5  6510.5  6540.5  6580.5  6620.5  6640.5  6710.5
   93.65   91.29   91.47   90.56    88.1   88.12   87.75   87.33    87.2   86.95
   86.76   86.74   86.71    86.7   89.39   90.13   90.65   91.38   91.48   91.69
    91.8   92.03   92.02   94.32    94.3    94.3    94.2    94.2   93.94   91.64
   91.58   91.58   91.16   90.53   90.93   88.96   89.11   89.21   90.52   90.76
   89.63   92.95   93.03   91.69   92.06   91.09   88.91   91.03   90.58   91.46
   90.41    90.1   91.07   90.56   90.83   92.49   91.32   92.22   91.89   93.63
   93.65   91.29   91.47   90.55   87.78   88.11   87.74   86.12   87.19   86.68
    86.6   85.44   85.46   85.96   87.22    86.4   88.13      89   88.61    86.3
   85.83    86.6   85.26   85.24    84.5    88.5    88.4   83.23   84.04   84.04
   84.23   89.92   90.46   90.52   90.92   87.89   87.64   89.16   90.51   90.75
   89.62   92.94   93.02   91.68   92.05   91.09   88.91   91.03   90.58   91.46
   90.41    90.1   91.07   90.56   90.83   92.49   91.32   92.22   91.89   93.63
  2826.4  2886.4  2956.4  3203.7  3633.7  3669.8  3829.8  3889.8    4071    4091
    4401    4431    4481    4500  4644.5  4684.5  4734.5  4804.5  4814.5  4834.5
  4844.5  4874.5 4888.89    4889 4920.81  4920.9 5089.49  5089.6  5114.4 5114.51
  5120.2  5120.9  5162.4  5235.7  5631.6  5661.6  5691.6  5711.6  5721.6  5731.6
  5786.6  5866.6  5906.6  5956.6  5966.6  6016.6  6086.6  6146.6  6176.6  6196.6
  6230.5  6300.5  6380.5  6480.5  6510.5  6540.5  6580.5  6620.5  6640.5  6710.5
   93.65   91.29   91.47   90.56    88.1   88.12   87.75   87.33    87.2   86.95
   86.76   86.74   86.71    86.7   89.39   90.13   90.65   91.38   91.48   91.69
    91.8   92.03   92.02   94.32    94.3    94.3    94.2    94.2   93.94   91.64
   91.58   91.58   91.16   90.53   90.93   88.96   89.11   89.21   90.52   90.76
   89.63   92.95   93.03   91.69   92.06   91.09   88.91   91.03   90.58   91.46
   90.41    90.1   91.07   90.56   90.83   92.49   91.32   92.22   91.89   93.63
   93.27   90.91   91.09   90.17    87.4   87.73   87.36   85.74   86.81    86.3
   86.22   85.06   85.08   85.58   86.84   86.02   87.75   88.62   88.23   85.92
   85.45   86.22   84.88   84.86   84.12   88.12   88.02   82.85   83.66   83.66
   83.85   89.54   90.08   90.14   90.54   87.51   87.26   88.78   90.13   90.37
   89.24   92.56   92.64    91.3   91.67   90.71   88.53   90.65    90.2   91.08
   90.03   89.72   90.69   90.18   90.45   92.11   90.94   91.84   91.51   93.25
Pier Skew, UpSta & Num, DnSta & Num=  ,4954.9, 2 ,4954.9, 2 , 0 , 0 , 0 ,,
       2       2
   73.66   89.48
       2       2
   73.28    89.1
Pier Skew, UpSta & Num, DnSta & Num=  ,5039.5, 2 ,5039.5, 2 , 0 , 0 , 0 ,,
       2       2
   72.52   89.43
       2       2
   72.15   89.05
Abutment Skew #Up #Dn= , 2 , 2
  4920.7  4957.4
    88.5   74.75
  4920.7  4957.4
   88.12   74.37
Abutment Skew #Up #Dn= , 2 , 2
  5052.2 5089.69
   76.08    88.4
  5052.2 5089.69
    75.7   88.02
BR Coef= 1 , 1 , 0 ,1.25, 0 ,,,0.8,-1,2,0,
WSPro=,,,, 1 ,,,, 0 ,,,, 0 ,,,,-1 ,-1 ,-1 , 0 , 0 , 0 , 0 , 0
BR U #Sta/Elev= 121
  2826.4   93.65  2886.4   91.29  2916.4    91.5  2946.4   91.25  2956.4   91.47
    3000   91.31  3118.9   90.87  3203.7   90.55  3623.7    88.1  3633.7   87.78
  3669.8   88.11  3829.8   87.74  3889.8   86.12  3949.8   86.37  3959.8   86.69
    4000    86.9    4001   86.91  4053.9   87.12    4071   87.19    4091   86.68
    4191   86.56    4201   86.81    4221   86.56    4231    86.9    4351   86.79
    4361   86.45    4371   86.37    4401    86.6    4411   86.42    4421    85.8
    4431   85.44    4461   85.72    4481   85.46    4491   85.61    4500   85.96
    4511   86.38  4534.5   86.45  4644.5   87.22  4684.5    86.4  4690.3    86.6
  4734.5   88.13  4756.4    88.4  4804.5      89  4813.1   88.66  4814.5   88.61
  4824.5   87.65  4834.5    86.3  4844.5   85.83  4867.7   86.43  4874.5    86.6
  4884.5   85.92 4888.89   85.26    4889   85.24 4889.11   85.22  4890.6      85
 4920.81    84.5  4920.9    84.5  4921.4   84.49  4954.9    74.6  4957.4   74.75
  4961.4   74.99  4970.4   70.44  4981.4   69.95  4999.8   68.13  5022.6   69.95
  5029.5   70.33  5039.5   73.88  5052.1   76.05  5052.2   76.08    5079   82.89
 5089.49   83.23  5089.6   83.23  5089.7   83.24 5114.29   84.04  5114.4   84.04
 5114.51   84.04  5120.2   84.23  5120.9   89.92  5162.4   90.46  5183.8   90.48
  5235.7   90.52  5298.4   90.57  5361.6   90.63  5541.6   90.78  5571.6   91.08
  5631.6   90.92  5661.6   87.89  5691.6   87.64  5701.6   88.24  5711.6   89.16
  5721.6   90.51  5731.6   90.75  5786.6   89.62  5866.6   92.94  5906.6   93.02
  5956.6   91.68  5966.6   92.05  5983.4   91.73  6016.6   91.09  6086.6   88.91
  6096.6   89.52  6116.6   89.85  6146.6   91.03  6176.6   90.58  6196.6   91.46
  6210.5   91.07  6230.5   90.41  6290.5   90.37  6300.5    90.1  6380.5   91.07
  6390.5   90.75  6410.5   90.79  6440.5   90.45  6470.5   90.85  6480.5   90.56
  6510.5   90.83  6540.5   92.49  6580.5   91.32  6620.5   92.22  6640.5   91.89
  6710.5   93.63
BR U #Mann= 5
  2826.4      .1  3118.9     .14  4053.9      .1  4890.6    .035  5120.2      .1
BR U Banks=4890.6,5120.2
BR D #Sta/Elev= 121
  2826.4   93.27  2886.4   90.91  2916.4   91.12  2946.4   90.87  2956.4   91.09
    3000   90.93  3118.9   90.49  3203.7   90.17  3623.7   87.72  3633.7    87.4
  3669.8   87.73  3829.8   87.36  3889.8   85.74  3949.8   85.99  3959.8   86.31
    4000   86.52    4001   86.53  4053.9   86.74    4071   86.81    4091    86.3
    4191   86.18    4201   86.43    4221   86.18    4231   86.52    4351   86.41
    4361   86.07    4371   85.99    4401   86.22    4411   86.04    4421   85.42
    4431   85.06    4461   85.34    4481   85.08    4491   85.23    4500   85.58
    4511      86  4534.5   86.07  4644.5   86.84  4684.5   86.02  4690.3   86.22
  4734.5   87.75  4756.4   88.02  4804.5   88.62  4813.1   88.28  4814.5   88.23
  4824.5   87.27  4834.5   85.92  4844.5   85.45  4867.7   86.05  4874.5   86.22
  4884.5   85.54 4888.89   84.88    4889   84.86 4889.11   84.84  4890.6   84.62
 4920.81   84.12  4920.9   84.12  4921.4   84.11  4954.9   74.22  4957.4   74.37
  4961.4   74.61  4970.4   70.06  4981.4   69.57  4999.8   67.75  5022.6   69.57
  5029.5   69.95  5039.5    73.5  5052.1   75.67  5052.2    75.7    5079   82.51
 5089.49   82.85  5089.6   82.85  5089.7   82.86 5114.29   83.66  5114.4   83.66
 5114.51   83.66  5120.2   83.85  5120.9   89.54  5162.4   90.08  5183.8    90.1
  5235.7   90.14  5298.4   90.19  5361.6   90.25  5541.6    90.4  5571.6    90.7
  5631.6   90.54  5661.6   87.51  5691.6   87.26  5701.6   87.86  5711.6   88.78
  5721.6   90.13  5731.6   90.37  5786.6   89.24  5866.6   92.56  5906.6   92.64
  5956.6    91.3  5966.6   91.67  5983.4   91.35  6016.6   90.71  6086.6   88.53
  6096.6   89.14  6116.6   89.47  6146.6   90.65  6176.6    90.2  6196.6   91.08
  6210.5   90.69  6230.5   90.03  6290.5   89.99  6300.5   89.72  6380.5   90.69
  6390.5   90.37  6410.5   90.41  6440.5   90.07  6470.5   90.47  6480.5   90.18
  6510.5   90.45  6540.5   92.11  6580.5   90.94  6620.5   91.84  6640.5   91.51
  6710.5   93.25
BR D #Mann= 5
  2826.4      .1  3118.9     .14  4053.9      .1  4890.6    .035  5120.2      .1
BR D Banks=4890.6,5120.2
BC Design=,, 0 ,, 0 ,,,,,,
BC HTab HWMax=93.79
BC Use User HTab Curves=0
BC User HTab FreeFlow(D)= 0

Type RM Length L Ch R = 1 ,168370.4,318,318,318
BEGIN DESCRIPTION:
Downstream Section of Bridge/Culvert/Weir
END DESCRIPTION:
XS GIS Cut Line= 6
      3102610.83     13915017.45      3102650.92     13913665.47
      3102710.72     13912602.22      3102764.84     13912095.54
      3102813.74     13911748.08      3102895.64     13911147.49
#Sta/Elev= 30
  2826.4   93.22  2886.4   90.86  3118.9   90.44  3889.8   85.69  4053.9   86.69
    4481   85.03  4804.5   88.57  4844.5    85.4  4874.5   86.17  4890.6   84.57
  4921.4   84.06  4954.9   74.17  4961.4   74.56  4970.4   70.01  4999.8    67.7
  5029.5    69.9    5079   82.46  5120.2    83.8  5120.9   89.49  5162.4   90.03
  5631.6   90.49  5661.6   87.46  5691.6   87.21  5721.6   90.08  5786.6   89.19
  5866.6   92.51  6086.6   88.48  6196.6   91.03  6480.5   90.13  6710.5    93.2
#Mann= 5 , 1 , 0
  2826.4      .1       0  3118.9     .14       0  4053.9      .1       0
  4890.6    .035       0  5120.2      .1       0
#XS Ineff= 3 ,-1
    2872    4750      92  4750.1    4910      88    5275    6542      92
Permanent Ineff=
       F       F       F
Bank Sta=4890.6,5120.2
XS Rating Curve= 0 ,0
Exp/Cntr=0.5,0.3

Type RM Length L Ch R = 1 ,168052.4,693.3,340.8,148.8
BEGIN DESCRIPTION:
Cross Section 168052.4-Interpolated
END DESCRIPTION:
XS GIS Cut Line= 6
      3103285.55     13914806.02      3103062.08     13913017.99
      3102974.31     13912710.79      3102772.43     13912596.68
       3102746.1     13912508.91      3102913.04     13911095.67
#Sta/Elev= 30
  2993.6    91.6  3293.2   89.66  3303.6    89.4  3343.6    90.3  3453.6    89.2
  3673.1    89.2  4401.4   86.95  4723.1    85.8  4883.5    84.6  4940.1   75.16
  4964.9   69.07  4966.4   70.07  4978.7   66.98  4979.8   68.26  4983.7   67.94
  4985.9    66.7  4991.1      66  5016.3      68  5020.4   70.79  5057.4   76.98
  5090.6   85.48    5347    86.7    5377    85.5    5407    85.5  5438.6    86.1
  5798.6    88.4  5818.6    87.8  5957.7    88.3  6667.7    91.9  6861.7    97.2
#Mann= 5 , 1 , 0
  2993.6     .07       0  3293.2      .1       0  4401.4     .14       0
  4883.5    .035       0  5090.6      .1       0
Bank Sta=4883.5,5090.6
XS Rating Curve= 0 ,0
Exp/Cntr=0.5,0.3

Type RM Length L Ch R = 1 ,167711.6,53,53,53
BEGIN DESCRIPTION:
Upstream Section of Bridge/Culvert/Weir
END DESCRIPTION:
XS GIS Cut Line= 6
      3104497.43     13914600.27      3103935.89     13912932.15
       3103766.1     13912742.89      3103475.21     13912757.44
       3102831.1     13912477.76      3103052.95     13911000.29
#Sta/Elev= 30
  2499.4   91.72  2628.7   91.02  3850.6   86.49  4807.2   84.92 4917.29   83.75
 4934.47   80.87 4957.47   74.31 4970.32    66.8 4976.14   69.22 4984.88   66.13
 4993.68   65.15 5008.95   70.12 5011.57   67.15 5014.48   69.94 5040.75   76.13
 5047.57   83.73 5064.33   84.63 5156.91   84.86 5158.12   83.28    5317   85.22
  5457.5   84.62  5497.5   86.72    5858   88.72  6133.6   87.42  6173.6   90.12
  6254.4   91.62  6294.4   90.32  6634.4   89.62  6814.4   92.12  7031.5   99.42
#Mann= 8 , 1 , 0
  2499.4      .2       0  2499.4     .07       0  2628.7      .1       0
  3850.6     .14       0  4807.2      .1       0 4917.29    .035       0
 5064.33      .1       0  7031.5      .2       0
#XS Ineff= 2 , 0
       0    4922    84.8    5053       0    84.6
Permanent Ineff=
       F       F
Bank Sta=4917.29,5064.33
XS Rating Curve= 0 ,0
Exp/Cntr=0.5,0.3

Type RM Length L Ch R = 3 ,167685.1,,,
BEGIN DESCRIPTION:
KNOBCREST DRIVE - 45 degree skew
Structure ID: POO-56
END DESCRIPTION:
Bridge Culvert--1,0,-1,-1, 0
Deck Dist Width WeirC Skew NumUp NumDn MinLoCord MaxHiCord MaxSubmerge Is_Ogee
10,33,2.6,0, 56, 56, , , 0.95, 0, 1,1,,
  2499.4  2628.7  2679.4  2729.4  2919.4  3029.4  3059.4  3129.4  3159.4  3729.4
  4295.2  4675.3  4681.8 4748.87  4781.5    4835  4878.8 4896.69  4896.8 4917.29
 4928.06 4928.15 5045.12 5045.23 5047.57 5064.33  5074.1 5074.21  5096.4 5156.91
 5158.12  5203.8 5206.89    5237    5277    5317    5347  5377.5  5417.5  5437.5
  5457.5  5497.5    5538    5858    5898  5963.6  6113.6  6133.6  6173.6  6254.4
  6294.4  6324.4  6414.4  6634.4  6814.4  7031.5
    91.7      91    91.2    90.6    90.2    90.1    89.5    89.5    89.2    86.9
    84.9   85.07    85.6   85.43   85.29   86.47   87.21   87.49   90.79   90.82
   90.83   90.83   90.84   90.84   90.84   90.84   90.81   87.51   87.46   85.97
   85.94   84.91    84.9   84.82   84.72   85.21    84.6   85.31    85.3    84.5
    84.6    86.7    86.8    88.7    87.5    88.4      88    87.4    90.1    91.6
    90.3    90.7    89.7    89.6    92.1    99.4
    91.7      91    91.2    90.6    90.2    90.1    89.5    89.5    89.2    86.9
    84.9   85.06   85.06   85.08   84.98   84.82   84.15   83.95   83.95   83.73
   81.92   84.83   84.84    81.1   83.71   84.61   84.72   84.72   84.96   84.84
   83.26   83.69   83.72    84.6    84.5    85.2    84.6    85.3    85.3    84.5
    84.6    86.7    86.8    88.7    87.5    88.4      88    87.4    90.1    91.6
    90.3    90.7    89.7    89.6    92.1    99.4
  2499.4  2628.7  2679.4  2729.4  2919.4  3029.4  3059.4  3129.4  3159.4  3729.4
  4295.2  4675.3  4681.8 4748.87  4781.5    4835  4878.8 4896.69  4896.8 4917.29
 4928.06 4928.15 5045.12 5045.23 5047.57 5064.33  5074.1 5074.21  5096.4 5156.91
 5158.12  5203.8 5206.89    5237    5277    5317    5347  5377.5  5417.5  5437.5
  5457.5  5497.5    5538    5858    5898  5963.6  6113.6  6133.6  6173.6  6254.4
  6294.4  6324.4  6414.4  6634.4  6814.4  7031.5
    91.7      91    91.2    90.6    90.2    90.1    89.5    89.5    89.2    86.9
    84.9   85.07    85.6   85.43   85.29   86.47   87.21   87.49   90.79   90.82
   90.83   90.83   90.84   90.84   90.84   90.84   90.81   87.51   87.46   85.97
   85.94   84.91    84.9   84.82   84.72   85.21    84.6   85.31    85.3    84.5
    84.6    86.7    86.8    88.7    87.5    88.4      88    87.4    90.1    91.6
    90.3    90.7    89.7    89.6    92.1    99.4
   91.53   90.83   91.03   90.43   90.03   89.93   89.33   89.33   89.03   86.73
   84.73   84.89   84.89   84.91   84.81   84.65   83.98   83.78   83.78   83.56
   81.75   84.66   84.67   80.93   83.54   84.44   84.55   84.55   84.79   84.67
   83.09   83.52   83.55   84.43   84.33   85.03   84.43   85.13   85.13   84.33
   84.43   86.53   86.63   88.53   87.33   88.23   87.83   87.23   89.93   91.43
   90.13   90.53   89.53   89.43   91.93   99.23
Pier Skew, UpSta & Num, DnSta & Num=  ,4970.3, 2 ,4970.3, 2 , 0 , 0 , 0 ,,
     1.4     1.4
   65.99   85.84
     1.4     1.4
   65.82   85.67
Pier Skew, UpSta & Num, DnSta & Num=  ,5008.9, 2 ,5008.9, 2 , 0 , 0 , 0 ,,
     1.4     1.4
   68.31   85.84
     1.4     1.4
   68.14   85.67
Abutment Skew #Up #Dn= , 2 , 2
 4927.95 4934.47
   84.83   80.85
 4927.95 4934.47
   84.66   80.68
BR Coef= 1 , 1 , 0 ,1.25, 0 ,,,0.8,-1,2,0,
WSPro=,,,, 1 ,,,, 0 ,,,, 0 ,,,,-1 ,-1 ,-1 , 0 , 0 , 0 , 0 , 0
BR U #Sta/Elev= 91
  2499.4    91.7  2628.7      91  2629.4      91  2679.4    91.2  2729.4    90.6
  2919.4    90.2  3029.4    90.1  3059.4    89.5  3129.4    89.5  3159.4    89.2
  3729.4    86.9  3850.6   86.47  4295.2    84.9    4512      85  4593.8   85.03
    4607   85.03  4675.3   85.06  4681.8   85.06  4731.8   85.07 4748.87   85.08
  4781.5   84.98 4793.46   84.94  4807.2    84.9    4835   84.82  4841.7   84.72
  4878.8   84.15 4896.69   83.95  4896.8   83.95 4896.91   83.95  4898.8   83.93
 4917.29   83.73 4928.06   81.92 4928.15   81.91 4934.37   80.87 4934.47   80.85
 4957.47   74.29 4970.32   66.78 4975.08    68.2 4976.14    69.2  4979.4   68.05
 4984.88   66.11 4985.66   67.39 4988.43   67.07 4989.99   65.83 4993.68   65.13
 5008.95    70.1 5011.57   67.13 5014.48   69.92 5040.75   76.11 5044.73   80.55
 5045.12   80.98 5045.23    81.1 5047.57   83.71  5063.7   84.58 5064.33   84.61
 5073.99   84.72  5074.1   84.72 5074.21   84.72  5096.4   84.96 5099.61      85
  5155.4   84.84 5156.91   84.84 5158.12   83.26  5203.8   83.69 5206.89   83.72
    5237    84.6  5261.9   84.54    5277    84.5    5317    85.2    5347    84.6
  5377.5    85.3  5404.9    85.3  5414.9    85.3  5417.5    85.3  5437.5    84.5
  5457.5    84.6  5497.5    86.7    5538    86.8    5858    88.7    5898    87.5
  5963.6    88.4  6113.6      88  6133.6    87.4  6173.6    90.1  6254.4    91.6
  6294.4    90.3  6324.4    90.7  6414.4    89.7  6634.4    89.6  6814.4    92.1
  7031.5    99.4
BR U #Mann= 8
  2499.4      .2  2499.4     .07  2628.7      .1  3850.6     .14  4807.2      .1
 4917.29    .035 5064.33      .1  7031.5      .2
BR U Banks=4917.29,5064.33
BR D #Sta/Elev= 91
  2499.4   91.53  2628.7   90.83  2629.4   90.83  2679.4   91.03  2729.4   90.43
  2919.4   90.03  3029.4   89.93  3059.4   89.33  3129.4   89.33  3159.4   89.03
  3729.4   86.73  3850.6    86.3  4295.2   84.73    4512   84.83  4593.8   84.86
    4607   84.86  4675.3   84.89  4681.8   84.89  4731.8    84.9 4748.87   84.91
  4781.5   84.81 4793.46   84.77  4807.2   84.73    4835   84.65  4841.7   84.55
  4878.8   83.98 4896.69   83.78  4896.8   83.78 4896.91   83.78  4898.8   83.76
 4917.29   83.56 4928.06   81.75 4928.15   81.74 4934.37    80.7 4934.47   80.68
 4957.47   74.12 4970.32   66.61 4975.08   68.03 4976.14   69.03  4979.4   67.88
 4984.88   65.94 4985.66   67.22 4988.43    66.9 4989.99   65.66 4993.68   64.96
 5008.95   69.93 5011.57   66.96 5014.48   69.75 5040.75   75.94 5044.73   80.38
 5045.12   80.81 5045.23   80.93 5047.57   83.54  5063.7   84.41 5064.33   84.44
 5073.99   84.55  5074.1   84.55 5074.21   84.55  5096.4   84.79 5099.61   84.83
  5155.4   84.67 5156.91   84.67 5158.12   83.09  5203.8   83.52 5206.89   83.55
    5237   84.43  5261.9   84.37    5277   84.33    5317   85.03    5347   84.43
  5377.5   85.13  5404.9   85.13  5414.9   85.13  5417.5   85.13  5437.5   84.33
  5457.5   84.43  5497.5   86.53    5538   86.63    5858   88.53    5898   87.33
  5963.6   88.23  6113.6   87.83  6133.6   87.23  6173.6   89.93  6254.4   91.43
  6294.4   90.13  6324.4   90.53  6414.4   89.53  6634.4   89.43  6814.4   91.93
  7031.5   99.23
BR D #Mann= 8
  2499.4      .2  2499.4     .07  2628.7      .1  3850.6     .14  4807.2      .1
 4917.29    .035 5064.33      .1  7031.5      .2
BR D Banks=4917.29,5064.33
BC Design=,, 0 ,, 0 ,,,,,,
BC HTab HWMax=99.42
BC Use User HTab Curves=0
BC User HTab FreeFlow(D)= 0

Type RM Length L Ch R = 1 ,167658.6,843.8,843.8,843.8
BEGIN DESCRIPTION:
Downstream Section of Bridge/Culvert/Weir
END DESCRIPTION:
XS GIS Cut Line= 6
      3104539.42     13914567.92      3103977.87     13912899.81
      3103808.08     13912710.55      3103517.19      13912725.1
      3102873.08     13912445.42      3103094.94     13910967.94
#Sta/Elev= 30
  2499.4   91.52  2628.7   90.82  3850.6   86.29  4807.2   84.72 4917.29   83.55
 4934.47   80.67 4957.47   74.11 4970.32    66.6 4976.14   69.02 4984.88   65.93
 4993.68   64.95 5008.95   69.92 5011.57   66.95 5014.48   69.74 5040.75   75.93
 5047.57   83.53 5064.33   84.43 5156.91   84.66 5158.12   83.08    5317   85.02
  5457.5   84.42  5497.5   86.52    5858   88.52  6133.6   87.22  6173.6   89.92
  6254.4   91.42  6294.4   90.12  6634.4   89.42  6814.4   91.92  7031.5   99.22
#Mann= 8 , 1 , 0
  2499.4      .2       0  2499.4     .07       0  2628.7      .1       0
  3850.6     .14       0  4807.2      .1       0 4917.29    .035       0
 5064.33      .1       0  7031.5      .2       0
#XS Ineff= 2 , 0
       0    4922    84.7    5053       0    84.5
Permanent Ineff=
       F       F
Bank Sta=4917.29,5064.33
XS Rating Curve= 0 ,0
Exp/Cntr=0.5,0.3

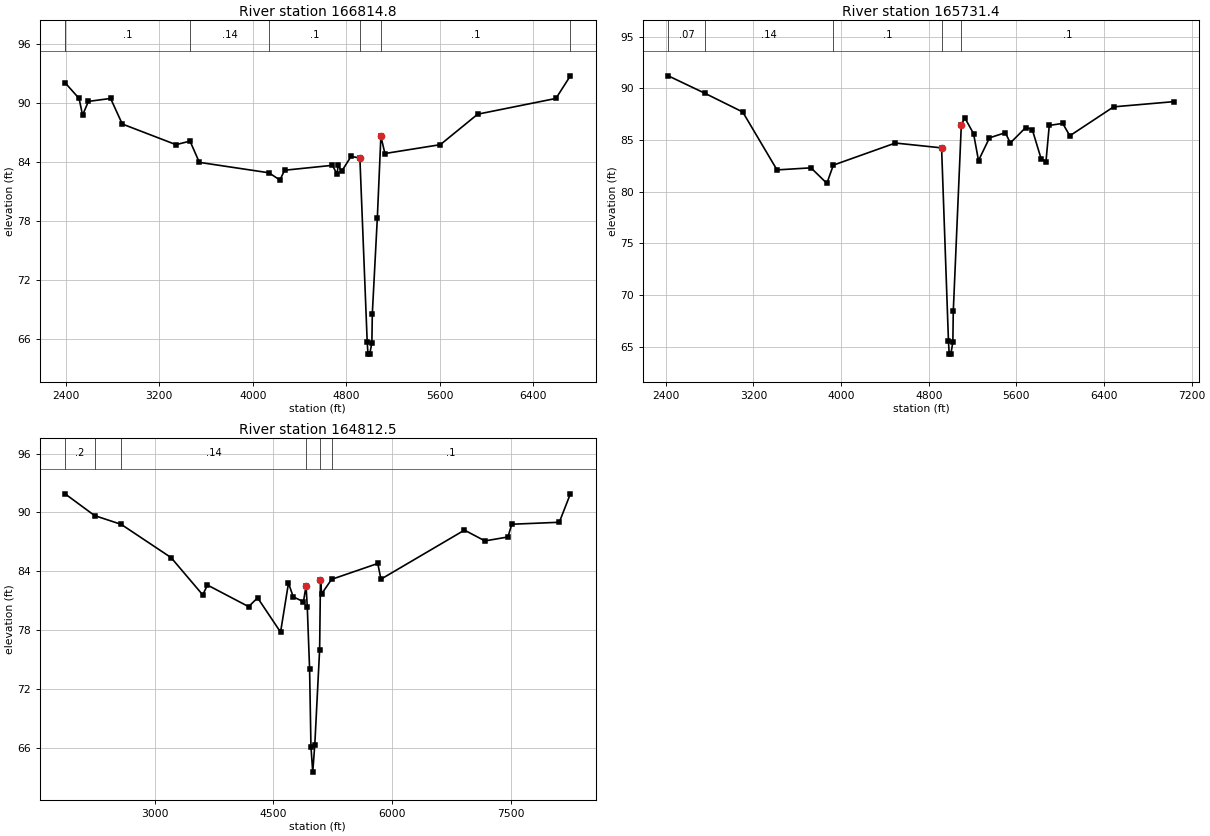
Type RM Length L Ch R = 1 ,166814.8,924.6,1083.4,1169
BEGIN DESCRIPTION:
Cross Section 166814.8-Interpolated
END DESCRIPTION:
XS GIS Cut Line= 4
      3105054.33     13914415.57      3104139.47     13912306.49
       3103821.5     13911864.44      3102890.87      13910708.9
#Sta/Elev= 30
  2392.7    92.1  2512.7    90.5  2542.7    88.8  2592.7    90.2  2782.7    90.5
  2882.7    87.9  3342.7    85.8  3462.8   86.16  3542.7      84  4138.7   82.94
  4232.7    82.2  4272.7    83.2  4682.7    83.7  4721.7    82.8  4731.7    83.7
  4761.7    83.1  4841.7    84.6  4917.3   84.45    4980   65.76  4986.4   64.56
  5001.7    64.5  5020.1   65.66  5023.9   68.63  5066.8   78.36  5097.2   86.64
  5131.7    84.9  5606.2    85.8  5926.2    88.9  6596.2    90.5  6719.9    92.8
#Mann= 7 , 1 , 0
  2392.7      .2       0  2392.7      .1       0  3462.8     .14       0
  4138.7      .1       0  4917.3    .035       0  5097.2      .1       0
  6719.9      .2       0
Bank Sta=4917.3,5097.2
XS Rating Curve= 0 ,0
Exp/Cntr=0.3,0.1

Type RM Length L Ch R = 1 ,165731.4,1016.4,918.9,722.2
BEGIN DESCRIPTION:
Cross Section 165731.4
END DESCRIPTION:
XS GIS Cut Line= 6
      3105577.08     13914322.79      3105531.49     13913541.15
      3105054.36     13912128.13      3104880.03     13911155.54
      3104246.92     13910577.48      3103761.01      13910514.7
#Sta/Elev= 30
  2422.4    91.2  2755.5   89.52  3102.4    87.7  3415.3    82.1  3725.3    82.3
  3870.3    80.8  3929.1   82.56  4495.3    84.7  4917.3   84.23    4980   65.54
  4986.4   64.34  5001.7   64.28  5020.1   65.44  5023.9   68.41  5097.2   86.42
  5128.5   87.15  5209.2    85.6  5254.2      83  5354.2    85.2  5499.2    85.7
  5544.2    84.7  5684.9    86.2  5744.9      86  5824.9    83.2  5869.9    82.9
  5899.9    86.4  6022.5    86.6  6087.5    85.4  6487.5    88.2  7034.1    88.7
#Mann= 5 , 1 , 0
  2422.4     .07       0  2755.5     .14       0  3929.1      .1       0
  4917.3    .035       0  5097.2      .1       0
Bank Sta=4917.3,5097.2
XS Rating Curve= 0 ,0
Exp/Cntr=0.3,0.1

Type RM Length L Ch R = 1 ,164812.5,907.1,659,543.7
BEGIN DESCRIPTION:
Cross Section 164812.5-Interpolated
END DESCRIPTION:
XS GIS Cut Line= 6
      3106593.51     13914684.48      3106162.05     13912289.14
      3106011.44     13911792.12      3105725.27     13911445.71
      3104670.98     13910692.64      3103023.18     13910366.24
#Sta/Elev= 30
  1867.7    91.9  2241.3   89.68  2576.5   88.79  3207.7    85.4  3607.7    81.6
  3667.7    82.6  4187.7    80.4  4301.6    81.3  4591.6    77.8  4691.6    82.8
  4751.6    81.4  4880.9    80.9  4913.7   82.51  4929.1    80.4  4958.4   74.08
  4975.7   66.14  4998.3   63.53  5024.4   66.34  5085.4   76.03  5095.9   83.15
  5110.9    81.7    5236   83.18  5820.3    84.8  5860.3    83.2  6915.9    88.2
  7174.7    87.1  7464.7    87.5  7514.7    88.8  8114.7      89  8254.7    91.9
#Mann= 6 , 1 , 0
  1867.7      .2       0  2241.3     .07       0  2576.5     .14       0
  4913.7    .035       0  5095.9     .14       0    5236      .1       0
Bank Sta=4913.7,5095.9
XS Rating Curve= 0 ,0
Exp/Cntr=0.3,0.1