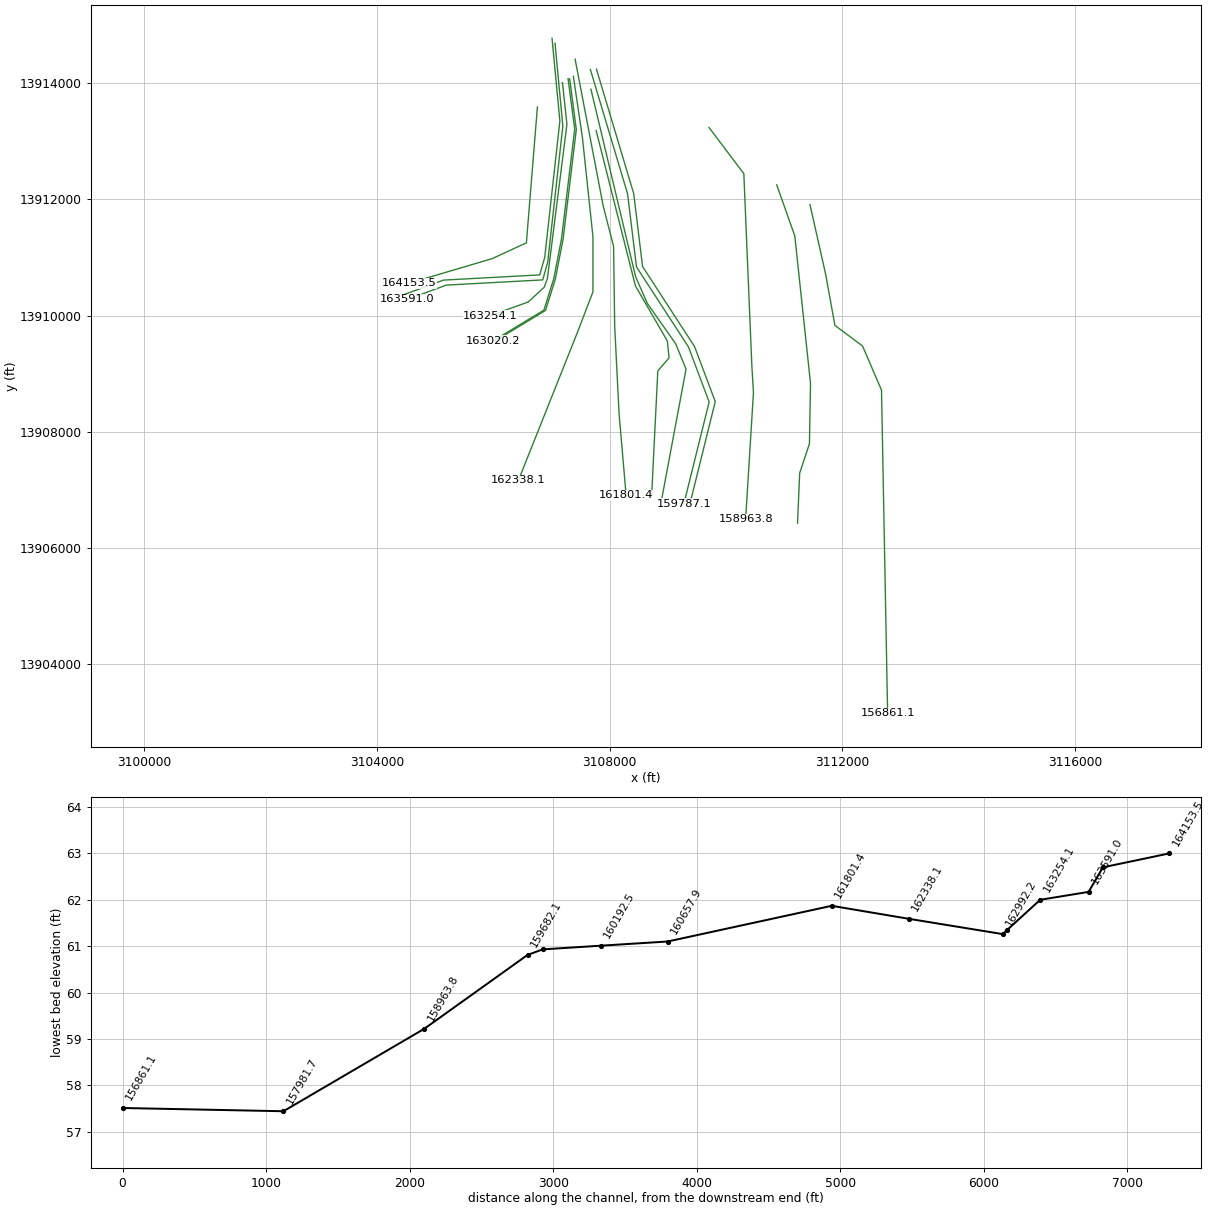
HEC-RAS study P100-00-00.prj: P100-00-00

--- P100-00-00.g01 (geometry) --- (continued)

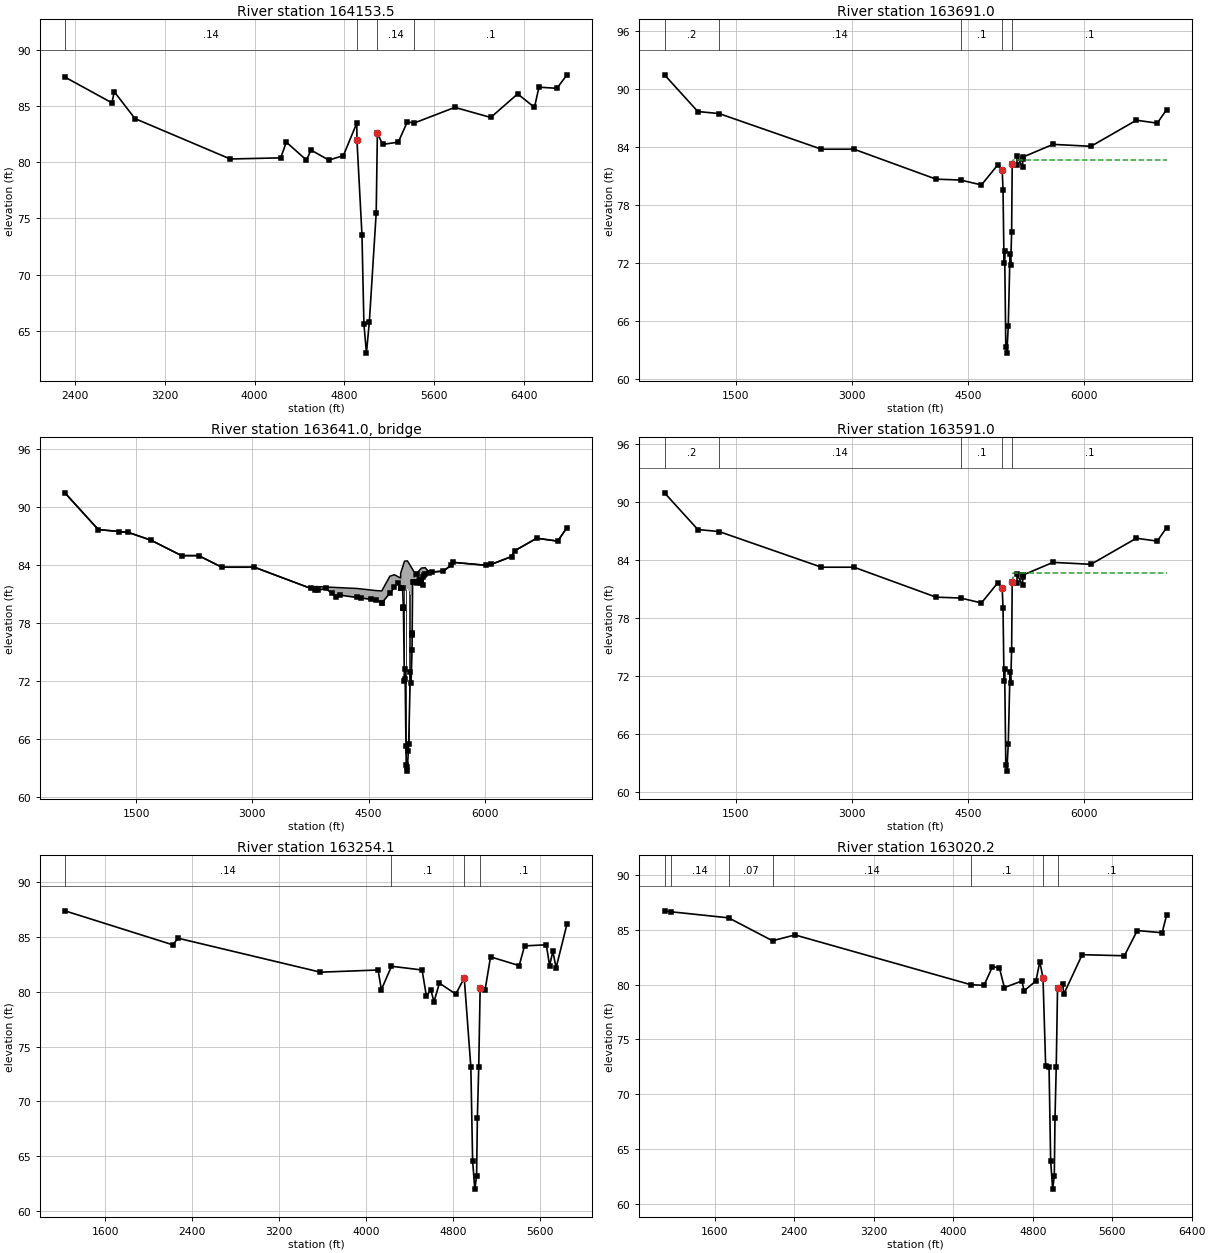
Type RM Length L Ch R = 1 ,164153.5,503.4,462.5,321.8
BEGIN DESCRIPTION:
Cross Section 164153.5-Interpolated
END DESCRIPTION:
XS GIS Cut Line= 4
      3106758.46     13913586.87       3106568.7     13911249.91
      3105981.31     13910978.81      3104556.03     13910556.19
#Sta/Elev= 30
  2308.8    87.6  2728.8    85.3  2748.8    86.3  2933.7    83.9  3783.7    80.3
  4233.7    80.4  4283.7    81.8  4463.7    80.2  4503.7    81.1  4662.4    80.2
  4792.4    80.6  4912.4    83.5  4913.7   81.98  4958.4   73.55  4975.7   65.61
  4998.3      63  5024.4   65.81  5085.4    75.5  5095.9   82.62  5142.4    81.6
  5282.4    81.8  5362.4    83.6  5425.8   83.51    5787    84.9    6107      84
    6347    86.1    6497    84.9    6537    86.7    6697    86.6    6787    87.8
#Mann= 4 , 1 , 0
  2308.8     .14       0  4913.7    .035       0  5095.9     .14       0
  5425.8      .1       0
Bank Sta=4913.7,5095.9
XS Rating Curve= 0 ,0
Exp/Cntr=0.5,0.3

Type RM Length L Ch R = 1 ,163691.0,100,100,100
BEGIN DESCRIPTION:
Upstream Section of Bridge/Culvert/Weir
END DESCRIPTION:
XS GIS Cut Line= 6
      3107009.93     13914766.69      3107144.51     13913343.94
      3106884.32     13911002.19      3106798.38     13910698.55
      3105141.47       13910609.      3104468.95      13910361.6
#Sta/Elev= 30
   579.5   91.51  1009.5   87.71  1284.2    87.5  2605.3   83.81  3025.3   83.81
  4085.3   80.71  4401.3   80.62  4670.8   80.11 4881.71   82.19 4938.73   81.68
 4949.66   79.57  4962.3   72.01 4970.46   73.25 4985.45   63.38 4998.79    62.7
 5017.32   65.51 5039.33   72.96 5048.28   71.86 5060.63    75.2 5068.09   82.32
 5129.15   82.14 5130.92   83.07 5203.27   81.92 5203.56   82.77  5210.8   83.01
  5594.9   84.31  6084.9   84.11    6671   86.81    6941   86.51    7061   87.91
#Mann= 5 , 1 , 0
   579.5      .2       0  1284.2     .14       0  4401.3      .1       0
 4938.73    .035       0 5068.09      .1       0
#XS Ineff= 2 , 0
       0    4939    80.5    5073       0   82.65
Permanent Ineff=
       F       F
Bank Sta=4938.73,5068.09
XS Rating Curve= 0 ,0
Exp/Cntr=0.5,0.3

Type RM Length L Ch R = 3 ,163641.0,,,
BEGIN DESCRIPTION:
GREENS ROAD - 45 degree skew
Structure ID: P00-55
END DESCRIPTION:
Bridge Culvert--1,0,-1,-1, 0
Deck Dist Width WeirC Skew NumUp NumDn MinLoCord MaxHiCord MaxSubmerge Is_Ogee
10,80,2.6,0, 52, 52, , , 0.95, 0, 1,1,,
   579.5  1009.5  1399.5  1689.5  2085.3  2305.3  2605.3  3025.3  3755.3  3808.6
  3845.3  3945.3  4085.3  4135.3  4348.6  4595.3  4670.7  4774.5  4833.3 4881.71
 4913.39  4913.5 4938.73 4949.29 4949.38    4964  5001.9 5062.37 5062.48 5068.09
    5088 5088.11 5129.15 5130.92 5160.46  5181.4 5203.27 5203.56  5210.8  5229.9
  5286.2  5324.9  5464.9  5564.9  5594.9  6014.9  6084.9  6344.9  6384.9    6671
    6941    7061
    91.5    87.7    87.4    86.6      85      85    83.8    83.8    81.6    81.8
   81.79   81.75    81.7   81.68    81.6   81.38   81.35   82.87   83.02   82.81
   82.68   83.18    83.8   84.06   84.07   84.43   84.45   83.65   83.65   83.57
   83.31   82.81   83.21   83.22   83.51   83.71   83.73   83.73   83.73   83.75
   83.25    83.3    83.4      84    84.3      84    84.1    84.9    85.5    86.8
    86.5    87.9
    91.5    87.7    87.4    86.6      85      85    83.8    83.8    81.6   81.48
    81.4    81.6    80.7    80.9   80.67    80.4    80.1   81.12    81.7   82.18
   81.68   81.68   81.67   79.63   81.17   81.53   81.55   80.75   76.96   82.31
   82.23   82.23   82.13   83.06   82.46   82.19   81.91   82.76      83   83.05
    83.2    83.3    83.4      84    84.3      84    84.1    84.9    85.5    86.8
    86.5    87.9
   579.5  1009.5  1399.5  1689.5  2085.3  2305.3  2605.3  3025.3  3755.3  3808.6
  3845.3  3945.3  4085.3  4135.3  4348.6  4595.3  4670.7  4774.5  4833.3 4881.71
 4913.39  4913.5 4938.73 4949.29 4949.38    4964  5001.9 5062.37 5062.48 5068.09
    5088 5088.11 5129.15 5130.92 5160.46  5181.4 5203.27 5203.56  5210.8  5229.9
  5286.2  5324.9  5464.9  5564.9  5594.9  6014.9  6084.9  6344.9  6384.9    6671
    6941    7061
    91.5    87.7    87.4    86.6      85      85    83.8    83.8    81.6    81.8
   81.79   81.75    81.7   81.68    81.6   81.38   81.35   82.87   83.02   82.81
   82.68   83.18    83.8   84.06   84.07   84.43   84.45   83.65   83.65   83.57
   83.31   82.81   83.21   83.22   83.51   83.71   83.73   83.73   83.73   83.75
   83.25    83.3    83.4      84    84.3      84    84.1    84.9    85.5    86.8
    86.5    87.9
   90.98   87.18   86.88   86.08   84.48   84.48   83.28   83.28   81.08   80.96
   80.88   81.08   80.18   80.38   80.15   79.88   79.58    80.6   81.18   81.66
   81.16   81.16   81.15   79.11   80.65   81.01   81.03   80.23   76.44   81.79
   81.71   81.71   81.61   82.54   81.94   81.67   81.39   82.24   82.48   82.53
   82.68   82.78   82.88   83.48   83.78   83.48   83.58   84.38   84.98   86.28
   85.98   87.38
Pier Skew, UpSta & Num, DnSta & Num=  ,4962.3, 2 ,4962.3, 2 , 0 , 0 , 0 ,,
       2       2
   71.15   82.51
       2       2
   70.63   81.99
Pier Skew, UpSta & Num, DnSta & Num=  ,4985.4, 2 ,4985.4, 2 , 0 , 0 , 0 ,,
       2       2
   62.32   82.54
       2       2
    61.8   82.02
Pier Skew, UpSta & Num, DnSta & Num=  ,5017.3, 2 ,5017.3, 2 , 0 , 0 , 0 ,,
       2       2
   64.34   82.36
       2       2
   63.82   81.84
Pier Skew, UpSta & Num, DnSta & Num=  ,5039.3, 2 ,5039.3, 2 , 0 , 0 , 0 ,,
       2       2
   71.61   82.06
       2       2
   71.09   81.54
BR Coef= 1 , 1 , 0 ,1.25, 0 ,,,0.8,0,2,0,
WSPro=,,,, 1 ,,,, 0 ,,,, 0 ,,,,-1 ,-1 ,-1 , 0 , 0 , 0 , 0 , 0
BR U #Sta/Elev= 76
   579.5    91.5  1009.5    87.7  1284.2   87.49  1399.5    87.4  1689.5    86.6
  2085.3      85  2305.3      85  2605.3    83.8  3025.3    83.8  3755.3    81.6
  3808.6   81.48  3845.3    81.4  3945.3    81.6  4025.3    81.1  4085.3    80.7
  4135.3    80.9  4348.6   80.67  4401.3   80.61  4534.7   80.47  4595.3    80.4
  4670.7    80.1  4670.8    80.1  4774.5   81.12  4833.3    81.7 4881.71   82.18
 4913.32   81.68 4913.39   81.68  4913.5   81.68 4913.61   81.68  4913.7   81.68
 4938.73   81.67 4949.29   79.63 4949.38   79.61 4949.45    79.6 4949.66   79.56
  4962.3      72    4964   72.26 4970.46   73.24 4982.75    65.3 4985.45   63.37
 4998.79   62.69  5001.9   63.15 5012.85   64.77 5017.32    65.5 5039.33   72.95
 5048.28   71.85 5060.63   75.19 5062.31   76.79 5062.37   76.85 5062.48   76.96
 5068.09   82.31  5087.8   82.24 5087.89   82.24    5088   82.23 5088.11   82.23
 5089.25   82.23 5129.15   82.13 5130.92   83.06 5160.46   82.46  5181.4   82.19
 5203.27   81.91 5203.56   82.76  5210.8      83  5229.9   83.05  5286.2    83.2
  5324.9    83.3  5464.9    83.4  5564.9      84  5594.9    84.3  6014.9      84
  6084.9    84.1  6344.9    84.9  6384.9    85.5    6671    86.8    6941    86.5
    7061    87.9
BR U #Mann= 5
   579.5      .2  1284.2     .14  4401.3      .1 4938.73    .035 5068.09      .1
BR U Banks=4938.73,5068.09
BR D #Sta/Elev= 76
   579.5   90.98  1009.5   87.18  1284.2   86.97  1399.5   86.88  1689.5   86.08
  2085.3   84.48  2305.3   84.48  2605.3   83.28  3025.3   83.28  3755.3   81.08
  3808.6   80.96  3845.3   80.88  3945.3   81.08  4025.3   80.58  4085.3   80.18
  4135.3   80.38  4348.6   80.15  4401.3   80.09  4534.7   79.95  4595.3   79.88
  4670.7   79.58  4670.8   79.58  4774.5    80.6  4833.3   81.18 4881.71   81.66
 4913.32   81.16 4913.39   81.16  4913.5   81.16 4913.61   81.16  4913.7   81.16
 4938.73   81.15 4949.29   79.11 4949.38   79.09 4949.45   79.08 4949.66   79.04
  4962.3   71.48    4964   71.74 4970.46   72.72 4982.75   64.78 4985.45   62.85
 4998.79   62.17  5001.9   62.63 5012.85   64.25 5017.32   64.98 5039.33   72.43
 5048.28   71.33 5060.63   74.67 5062.31   76.27 5062.37   76.33 5062.48   76.44
 5068.09   81.79  5087.8   81.72 5087.89   81.72    5088   81.71 5088.11   81.71
 5089.25   81.71 5129.15   81.61 5130.92   82.54 5160.46   81.94  5181.4   81.67
 5203.27   81.39 5203.56   82.24  5210.8   82.48  5229.9   82.53  5286.2   82.68
  5324.9   82.78  5464.9   82.88  5564.9   83.48  5594.9   83.78  6014.9   83.48
  6084.9   83.58  6344.9   84.38  6384.9   84.98    6671   86.28    6941   85.98
    7061   87.38
BR D #Mann= 5
   579.5      .2  1284.2     .14  4401.3      .1 4938.73    .035 5068.09      .1
BR D Banks=4938.73,5068.09
BC Design=,, 0 ,, 0 ,,,,,,
BC HTab HWMax=91.51
BC Use User HTab Curves=0
BC User HTab FreeFlow(D)= 0

Type RM Length L Ch R = 1 ,163591.0,336.9,336.9,336.9
BEGIN DESCRIPTION:
Downstream Section of Bridge/Culvert/Weir
END DESCRIPTION:
XS GIS Cut Line= 6
      3107061.07     13914680.76      3107195.65       13913258.
      3106935.46     13910916.25      3106849.52     13910612.61
      3105192.61     13910523.06      3104520.08     13910275.66
#Sta/Elev= 30
   579.5   90.98  1009.5   87.18  1284.2   86.97  2605.3   83.28  3025.3   83.28
  4085.3   80.18  4401.3   80.09  4670.8   79.58 4881.71   81.66 4938.73   81.15
 4949.66   79.04  4962.3   71.48 4970.46   72.72 4985.45   62.85 4998.79   62.17
 5017.32   64.98 5039.33   72.43 5048.28   71.33 5060.63   74.67 5068.09   81.79
 5129.15   81.61 5130.92   82.54 5203.27   81.39 5203.56   82.24  5210.8   82.48
  5594.9   83.78  6084.9   83.58    6671   86.28    6941   85.98    7061   87.38
#Mann= 5 , 1 , 0
   579.5      .2       0  1284.2     .14       0  4401.3      .1       0
 4938.73    .035       0 5068.09      .1       0
#XS Ineff= 2 , 0
       0    4939    80.5    5073       0   82.65
Permanent Ineff=
       F       F
Bank Sta=4938.73,5068.09
XS Rating Curve= 0 ,0
Exp/Cntr=0.5,0.3

Type RM Length L Ch R = 1 ,163254.1,82.2,233.9,241.9
BEGIN DESCRIPTION:
Cross Section 163254.1-Interpolated
END DESCRIPTION:
XS GIS Cut Line= 6
      3107189.31     13914004.55      3107265.95     13913287.28
      3106930.43      13910637.4      3106875.65     13910486.76
      3106601.76     13910233.41      3105952.65      13909999.4
#Sta/Elev= 30
  1229.8    87.4  2221.2    84.3  2271.2    84.9  3580.8    81.8  4110.8      82
  4140.8    80.2  4233.9   82.34  4515.4      82  4555.4    79.6  4595.4    80.2
  4624.9    79.1  4674.9    80.8  4825.2    79.8  4903.2   81.27    4964   73.14
  4980.3   64.58  5000.4      62  5016.9   63.19    5024   68.51  5036.5   73.14
  5049.6   80.36  5095.2    80.2  5145.2    83.2  5408.3    82.4  5458.3    84.2
  5658.3    84.3  5688.3    82.4  5718.3    83.7  5748.3    82.2  5848.3    86.2
#Mann= 4 , 1 , 0
  1229.8     .14       0  4233.9      .1       0  4903.2    .035       0
  5049.6      .1       0
Bank Sta=4903.2,5049.6
XS Rating Curve= 0 ,0
Exp/Cntr=0.5,0.3

Type RM Length L Ch R = 1 ,163020.2,28,28,28
BEGIN DESCRIPTION:
Upstream Section of Bridge/Culvert/Weir
END DESCRIPTION:
XS GIS Cut Line= 6
       3107285.7     13914073.32      3107399.68     13913203.79
      3107172.52     13911318.69      3107040.16      13910635.6
      3106870.07     13910092.21      3106002.19     13909567.35
#Sta/Elev= 30
  1092.3   86.73  1161.1   86.64  1737.6   86.09  2179.7      84  2406.2   84.53
  4176.8   79.99  4309.3   79.93  4394.3   81.63  4464.3   81.53  4514.3   79.73
  4691.7   80.33  4711.7   79.43  4832.4   80.33  4870.7   82.09  4903.2   80.61
  4929.9   72.61    4964   72.48  4980.2   63.92  5000.4   61.34  5016.9   62.53
    5024   67.85  5036.5   72.48  5049.6    79.7  5100.6   80.09  5112.5   79.13
  5297.5   82.73  5722.5   82.63  5852.5   84.93  6102.5   84.73  6147.5   86.33
#Mann= 7 , 1 , 0
  1092.3      .2       0  1161.1     .14       0  1737.6     .07       0
  2179.7     .14       0  4176.8      .1       0  4903.2    .035       0
  5049.6      .1       0
#XS Ineff= 2 , 0
       0    4885    79.5    5065       0   79.65
Permanent Ineff=
       F       F
Bank Sta=4903.2,5049.6
XS Rating Curve= 0 ,0
Exp/Cntr=0.5,0.3

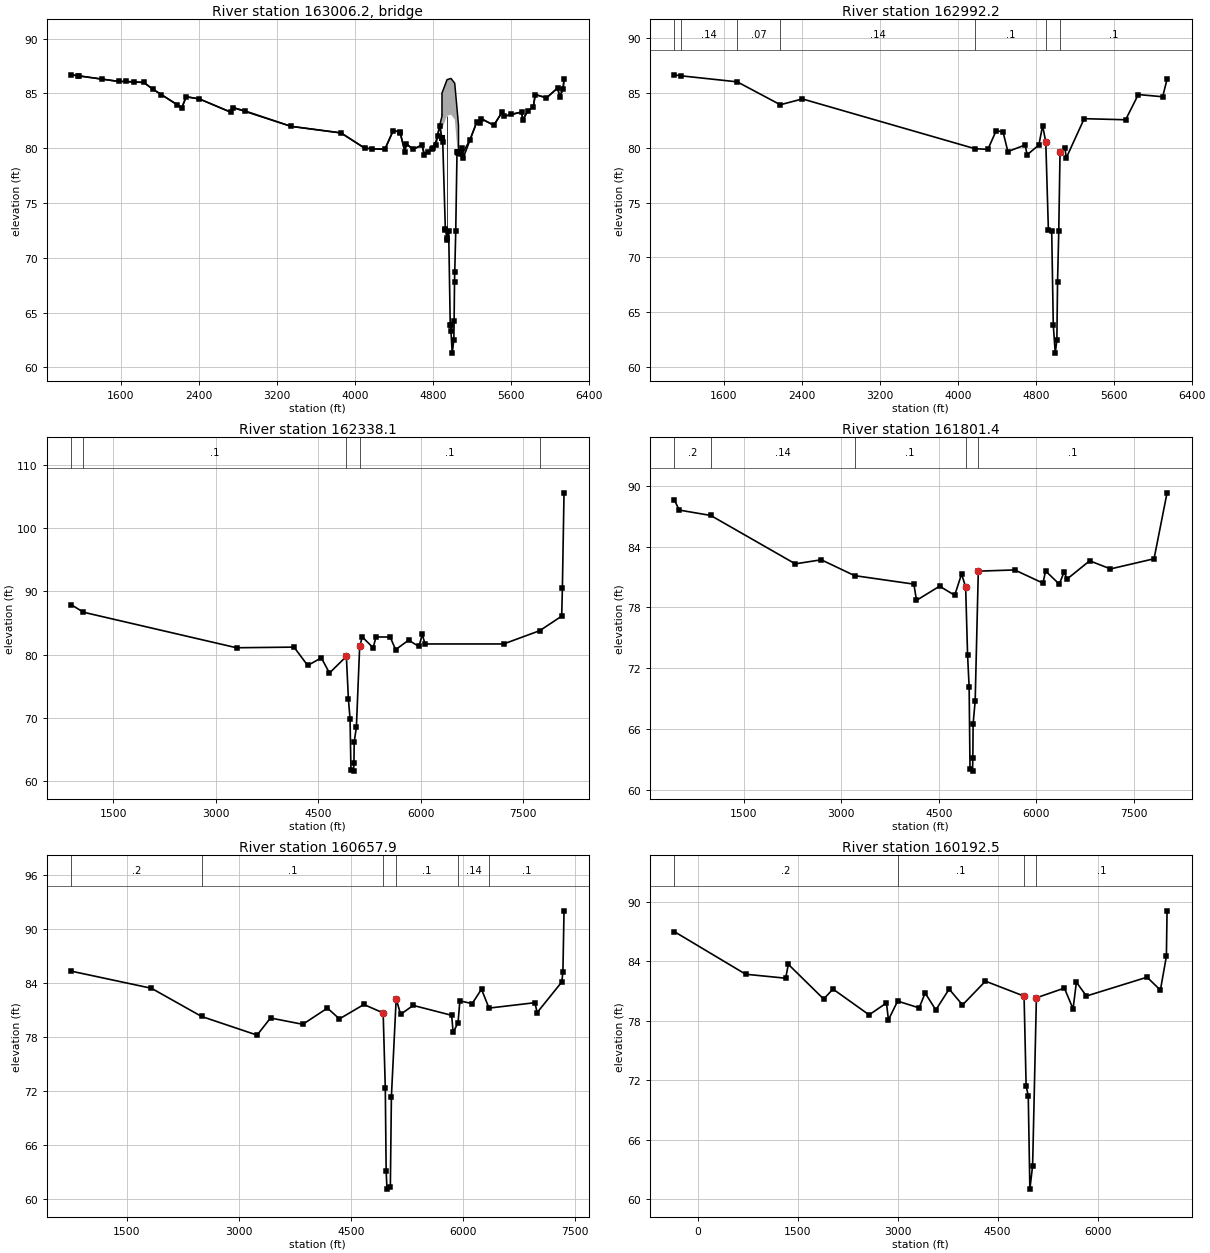
Type RM Length L Ch R = 3 ,163006.2,,,
BEGIN DESCRIPTION:
GREENS POINT PEDESTRIAN BRIDGE
Structure ID: P00-53
END DESCRIPTION:
Bridge Culvert--1,0,-1,-1, 0
Deck Dist Width WeirC Skew NumUp NumDn MinLoCord MaxHiCord MaxSubmerge Is_Ogee
10,8,2.6,0, 60, 60, , , 0.95, 0, 1,1,,
  1092.3  1577.3  1837.3  1926.2  2226.2  2271.2  2406.2  2726.2  2756.2  3346.2
  3859.3  4104.3  4309.3  4394.3  4464.3  4514.3  4529.3  4599.3  4691.7  4711.7
  4750.5  4792.8  4800.6  4832.4  4850.2  4870.7  4894.9 4895.19  4895.3  4895.4
  4895.7  4947.3  4987.7  5026.3 5054.69  5054.8  5064.8    5065 5065.11  5070.5
  5088.1  5100.6  5112.5  5183.3  5252.5  5287.5  5297.5  5427.5  5512.5  5527.5
  5712.5  5722.5  5777.5  5832.5  5852.5  5967.5  6082.5  6102.5  6137.5  6147.5
    86.7    86.1      86    85.4    83.7    84.7    84.5    83.3    83.7      82
    81.4      80    79.9    81.6    81.5   79.71   80.41   79.91   80.31   79.56
   79.68   79.97   80.04   80.62   81.12   82.07   82.91   83.05   83.05   84.95
   85.04   86.26   86.37   85.93   83.11   83.09    82.1   82.07   80.17   79.63
   79.64   80.07   79.66   80.78    82.4    82.3    82.7    82.1    83.3    82.9
    83.3    82.6    83.4    83.8    84.9    84.6    85.5    84.7    85.4    86.3
    86.7    86.1      86    85.4    83.7    84.7    84.5    83.3    83.7      82
    81.4      80    79.9    81.6    81.5    79.7    80.4    79.9    80.3    79.4
   79.67   79.96   80.03    80.3   81.12   82.06   80.96   80.94   81.65   81.65
   81.74   82.96   83.07   82.63   79.81   79.64   79.59   79.59   79.59   79.57
   79.48   80.06    79.1   80.77    82.4    82.3    82.7    82.1    83.3    82.9
    83.3    82.6    83.4    83.8    84.9    84.6    85.5    84.7    85.4    86.3
  1092.3  1577.3  1837.3  1926.2  2226.2  2271.2  2406.2  2726.2  2756.2  3346.2
  3859.3  4104.3  4309.3  4394.3  4464.3  4514.3  4529.3  4599.3  4691.7  4711.7
  4750.5  4792.8  4800.6  4832.4  4850.2  4870.7  4894.9 4895.19  4895.3  4895.4
  4895.7  4947.3  4987.7  5026.3 5054.69  5054.8  5064.8    5065 5065.11  5070.5
  5088.1  5100.6  5112.5  5183.3  5252.5  5287.5  5297.5  5427.5  5512.5  5527.5
  5712.5  5722.5  5777.5  5832.5  5852.5  5967.5  6082.5  6102.5  6137.5  6147.5
    86.7    86.1      86    85.4    83.7    84.7    84.5    83.3    83.7      82
    81.4      80    79.9    81.6    81.5   79.71   80.41   79.91   80.31   79.56
   79.68   79.97   80.04   80.62   81.12   82.07   82.91   83.05   83.05   84.95
   85.04   86.26   86.37   85.93   83.11   83.09    82.1   82.07   80.17   79.63
   79.64   80.07   79.66   80.78    82.4    82.3    82.7    82.1    83.3    82.9
    83.3    82.6    83.4    83.8    84.9    84.6    85.5    84.7    85.4    86.3
   86.64   86.04   85.94   85.34   83.64   84.64   84.44   83.24   83.64   81.94
   81.34   79.94   79.84   81.54   81.44   79.64   80.34   79.84   80.24   79.34
   79.61    79.9   79.97   80.24   81.06      82    80.9   80.88   81.59   81.59
   81.68    82.9   83.01   82.57   79.75   79.58   79.53   79.53   79.53   79.51
   79.42      80   79.04   80.71   82.34   82.24   82.64   82.04   83.24   82.84
   83.24   82.54   83.34   83.74   84.84   84.54   85.44   84.64   85.34   86.24
Pier Skew, UpSta & Num, DnSta & Num=  ,4950.5, 2 ,4950.5, 2 , 0 , 0 , 0 ,,
     1.2     1.2
   70.69   83.97
     1.2     1.2
   70.63   83.91
Abutment Skew #Up #Dn= , 2 , 2
  4895.1  4929.9
   81.65   72.58
  4895.1  4929.9
   81.59   72.52
BR Coef= 1 , 1 , 0 ,1.25, 0 ,,,0.8,0,2,0,
WSPro=,,,, 1 ,,,, 0 ,,,, 0 ,,,,-1 ,-1 ,-1 , 0 , 0 , 0 , 0 , 0
BR U #Sta/Elev= 88
  1092.3    86.7  1161.1   86.61  1172.3    86.6  1412.3    86.3  1577.3    86.1
  1657.3    86.1  1737.6   86.06  1837.3      86  1926.2    85.4  2016.2    84.9
  2179.7   83.97  2226.2    83.7  2271.2    84.7  2406.2    84.5  2726.2    83.3
  2756.2    83.7  2876.2    83.4  3346.2      82  3859.3    81.4  4104.3      80
  4176.8   79.96  4309.3    79.9  4394.3    81.6  4464.3    81.5    4468   81.37
  4514.3    79.7  4529.3    80.4  4599.3    79.9  4691.7    80.3  4711.7    79.4
  4750.5   79.67  4792.8   79.96  4800.6   80.03  4832.4    80.3  4850.2   81.12
  4870.7   82.06  4894.9   80.96 4895.11   80.95 4895.19   80.94  4895.3   80.94
  4895.4   80.94 4895.51   80.93  4895.7   80.92  4903.2   80.58  4929.8   72.61
  4929.9   72.58  4947.3    71.8  4950.5   71.66    4964   72.45  4980.2   63.89
  4983.9    63.9  4987.7    63.3  5000.4   61.31  5016.9    62.5  5019.7   64.26
    5024   67.82  5026.3   68.67  5036.5   72.45  5049.6   79.67  5054.6   79.65
 5054.69   79.64  5054.8   79.64  5064.8   79.59 5064.89   79.59    5065   79.59
 5065.11   79.59  5070.5   79.57  5088.1   79.48  5100.6   80.06  5112.5    79.1
  5183.3   80.77  5252.5    82.4  5287.5    82.3  5297.5    82.7  5427.5    82.1
  5512.5    83.3  5527.5    82.9  5602.5    83.1  5712.5    83.3  5722.5    82.6
  5777.5    83.4  5832.5    83.8  5852.5    84.9  5967.5    84.6  6082.5    85.5
  6102.5    84.7  6137.5    85.4  6147.5    86.3
BR U #Mann= 7
  1092.3      .2  1161.1     .14  1737.6     .07  2179.7     .14  4176.8      .1
  4903.2    .035  5049.6      .1
BR U Banks=4903.2,5049.6
BR D #Sta/Elev= 88
  1092.3   86.64  1161.1   86.55  1172.3   86.54  1412.3   86.24  1577.3   86.04
  1657.3   86.04  1737.6      86  1837.3   85.94  1926.2   85.34  2016.2   84.84
  2179.7   83.91  2226.2   83.64  2271.2   84.64  2406.2   84.44  2726.2   83.24
  2756.2   83.64  2876.2   83.34  3346.2   81.94  3859.3   81.34  4104.3   79.94
  4176.8    79.9  4309.3   79.84  4394.3   81.54  4464.3   81.44    4468   81.31
  4514.3   79.64  4529.3   80.34  4599.3   79.84  4691.7   80.24  4711.7   79.34
  4750.5   79.61  4792.8    79.9  4800.6   79.97  4832.4   80.24  4850.2   81.06
  4870.7      82  4894.9    80.9 4895.11   80.89 4895.19   80.88  4895.3   80.88
  4895.4   80.88 4895.51   80.87  4895.7   80.86  4903.2   80.52  4929.8   72.55
  4929.9   72.52  4947.3   71.74  4950.5    71.6    4964   72.39  4980.2   63.83
  4983.9   63.84  4987.7   63.24  5000.4   61.25  5016.9   62.44  5019.7    64.2
    5024   67.76  5026.3   68.61  5036.5   72.39  5049.6   79.61  5054.6   79.59
 5054.69   79.58  5054.8   79.58  5064.8   79.53 5064.89   79.53    5065   79.53
 5065.11   79.53  5070.5   79.51  5088.1   79.42  5100.6      80  5112.5   79.04
  5183.3   80.71  5252.5   82.34  5287.5   82.24  5297.5   82.64  5427.5   82.04
  5512.5   83.24  5527.5   82.84  5602.5   83.04  5712.5   83.24  5722.5   82.54
  5777.5   83.34  5832.5   83.74  5852.5   84.84  5967.5   84.54  6082.5   85.44
  6102.5   84.64  6137.5   85.34  6147.5   86.24
BR D #Mann= 7
  1092.3      .2  1161.1     .14  1737.6     .07  2179.7     .14  4176.8      .1
  4903.2    .035  5049.6      .1
BR D Banks=4903.2,5049.6
BC Design=,, 0 ,, 0 ,,,,,,
BC HTab HWMax=86.73
BC Use User HTab Curves=0
BC User HTab FreeFlow(D)= 0

Type RM Length L Ch R = 1 ,162992.2,654.1,654.1,654.1
BEGIN DESCRIPTION:
Downstream Section of Bridge/Culvert/Weir
END DESCRIPTION:
XS GIS Cut Line= 6
      3107313.27     13914068.44      3107427.26     13913198.91
       3107200.1     13911313.81      3107067.74     13910630.72
      3106897.65     13910087.33      3106029.76     13909562.47
#Sta/Elev= 30
  1092.3   86.65  1161.1   86.56  1737.6   86.01  2179.7   83.92  2406.2   84.45
  4176.8   79.91  4309.3   79.85  4394.3   81.55  4464.3   81.45  4514.3   79.65
  4691.7   80.25  4711.7   79.35  4832.4   80.25  4870.7   82.01  4903.2   80.53
  4929.9   72.53    4964    72.4  4980.2   63.84  5000.4   61.26  5016.9   62.45
    5024   67.77  5036.5    72.4  5049.6   79.62  5100.6   80.01  5112.5   79.05
  5297.5   82.65  5722.5   82.55  5852.5   84.85  6102.5   84.65  6147.5   86.25
#Mann= 7 , 1 , 0
  1092.3      .2       0  1161.1     .14       0  1737.6     .07       0
  2179.7     .14       0  4176.8      .1       0  4903.2    .035       0
  5049.6      .1       0
#XS Ineff= 2 , 0
       0    4885    79.5    5065       0   79.65
Permanent Ineff=
       F       F
Bank Sta=4903.2,5049.6
XS Rating Curve= 0 ,0
Exp/Cntr=0.5,0.3

Type RM Length L Ch R = 1 ,162338.1,400.5,536.7,838.5
BEGIN DESCRIPTION:
Cross Section 162338.1-Interpolated
END DESCRIPTION:
XS GIS Cut Line= 6
      3107376.84     13914113.17      3107532.63     13913057.27
      3107713.36     13911355.34      3107713.36     13910406.48
      3107442.26      13909698.6      3106433.15      13907168.3
#Sta/Elev= 30
   886.9    87.9  1063.7   86.72  3304.3    81.1  4145.8    81.2  4345.8    78.3
  4545.8    79.5  4664.6    77.1  4911.8   79.74  4941.6   73.02  4965.6   69.87
    4979   61.76  5017.8   61.59  5022.7    62.9  5026.5   66.24  5058.3    68.5
  5106.5    81.3  5144.6    82.8  5304.6    81.1  5344.6    82.8  5552.7    82.8
  5632.7    80.8  5822.7    82.3  5972.7    81.3  6022.7    83.2  6062.7    81.7
  7212.7    81.7  7741.4    83.8  8062.7    86.1  8072.7    90.5  8096.8   105.6
#Mann= 5 , 1 , 0
   886.9      .2       0  1063.7      .1       0  4911.8    .035       0
  5106.5      .1       0  7741.4      .2       0
Bank Sta=4911.8,5106.5
XS Rating Curve= 0 ,0
Exp/Cntr=0.3,0.1

Type RM Length L Ch R = 1 ,161801.4,948.6,1143.5,1272.5
BEGIN DESCRIPTION:
Cross Section 161801.4
END DESCRIPTION:
XS GIS Cut Line= 6
      3107406.64      13914409.1      3107890.53     13911880.03
      3108068.53     13911186.74      3108087.27      13909818.9
      3108162.22     13908319.89      3108283.58     13906910.17
#Sta/Elev= 30
   431.7    88.6   506.7    87.6   991.3   87.07  2291.7    82.3  2691.7    82.7
    3203   81.14  4115.9    80.3  4155.9    78.7  4510.9    80.1  4743.9    79.2
  4848.9    81.3  4911.8   80.02  4941.6    73.3  4965.6   70.15    4979   62.04
  5017.8   61.87  5022.7   63.18  5026.5   66.52  5058.3   68.78  5106.5   81.58
  5666.2    81.7  6101.2    80.4  6141.2    81.6  6351.4    80.3  6426.4    81.5
  6471.4    80.8  6819.3    82.6  7139.3    81.8  7809.3    82.8  8009.3    89.3
#Mann= 5 , 1 , 0
   431.7      .2       0   991.3     .14       0    3203      .1       0
  4911.8    .035       0  5106.5      .1       0
Bank Sta=4911.8,5106.5
XS Rating Curve= 0 ,0
Exp/Cntr=0.3,0.1

Type RM Length L Ch R = 1 ,160657.9,85,465.4,479.6
BEGIN DESCRIPTION:
Cross Section 160657.9
END DESCRIPTION:
XS GIS Cut Line= 6
      3107768.58     13913180.83       3108443.5     13910509.99
      3108993.81     13909559.45      3109021.99     13909271.72
      3108828.93     13909047.47       3108722.6     13906900.05
#Sta/Elev= 30
     755    85.3  1828.4    83.4    2500   80.27  3242.5    78.2  3422.5    80.1
  3854.9    79.4  4184.9    81.2  4344.9      80  4673.2    81.6    4931   80.66
  4959.6   72.31  4971.1   63.12  4982.2    61.1  5027.2   61.33  5041.3   71.37
  5105.3   82.25    5164    80.5  5332.9    81.5  5847.9    80.4  5867.9    78.5
  5933.6   79.57  5957.9      82  6122.9    81.7  6247.9    83.3    6348    81.2
  6962.9    81.8  6992.9    80.7  7322.9    84.1  7337.9    85.2  7352.9      92
#Mann= 6 , 1 , 0
     755      .2       0    2500      .1       0    4931    .035       0
  5105.3      .1       0  5933.6     .14       0    6348      .1       0
Bank Sta=4931,5105.3
XS Rating Curve= 0 ,0
Exp/Cntr=0.3,0.1

Type RM Length L Ch R = 1 ,160192.5,74.8,405.4,520.7
BEGIN DESCRIPTION:
Cross Section 160192.5-Interpolated
END DESCRIPTION:
XS GIS Cut Line= 6
      3107678.69     13913891.82      3108446.15     13910669.54
      3108646.82     13910211.49      3109137.56     13909511.83
      3109314.43     13909077.68      3108899.65     13906861.47
#Sta/Elev= 30
  -349.9      87   720.1    82.7  1320.1    82.3  1360.1    83.7  1890.1    80.2
  2030.1    81.2    2572    78.6    2832    79.8    2862    78.1    3000   79.99
  3322.5    79.3  3412.5    80.8  3572.6    79.1  3772.6    81.2  3972.6    79.6
  4317.2      82  4896.3   80.49  4927.5   71.41  4959.2   70.43  4983.4   61.01
  5024.7   63.38  5081.4   80.32  5501.3    81.3  5631.3    79.2  5681.3    81.9
  5831.3    80.5  6741.3    82.4  6941.3    81.1  7031.3    84.5  7041.3    89.1
#Mann= 4 , 1 , 0
  -349.9      .2       0    3000      .1       0  4896.3    .035       0
  5081.4      .1       0
#XS Ineff= 2 , 0
       0  1360.1    83.7  6741.3       0    82.4
Permanent Ineff=
       F       F
Bank Sta=4896.3,5081.4
XS Rating Curve= 0 ,0
Exp/Cntr=0.5,0.3

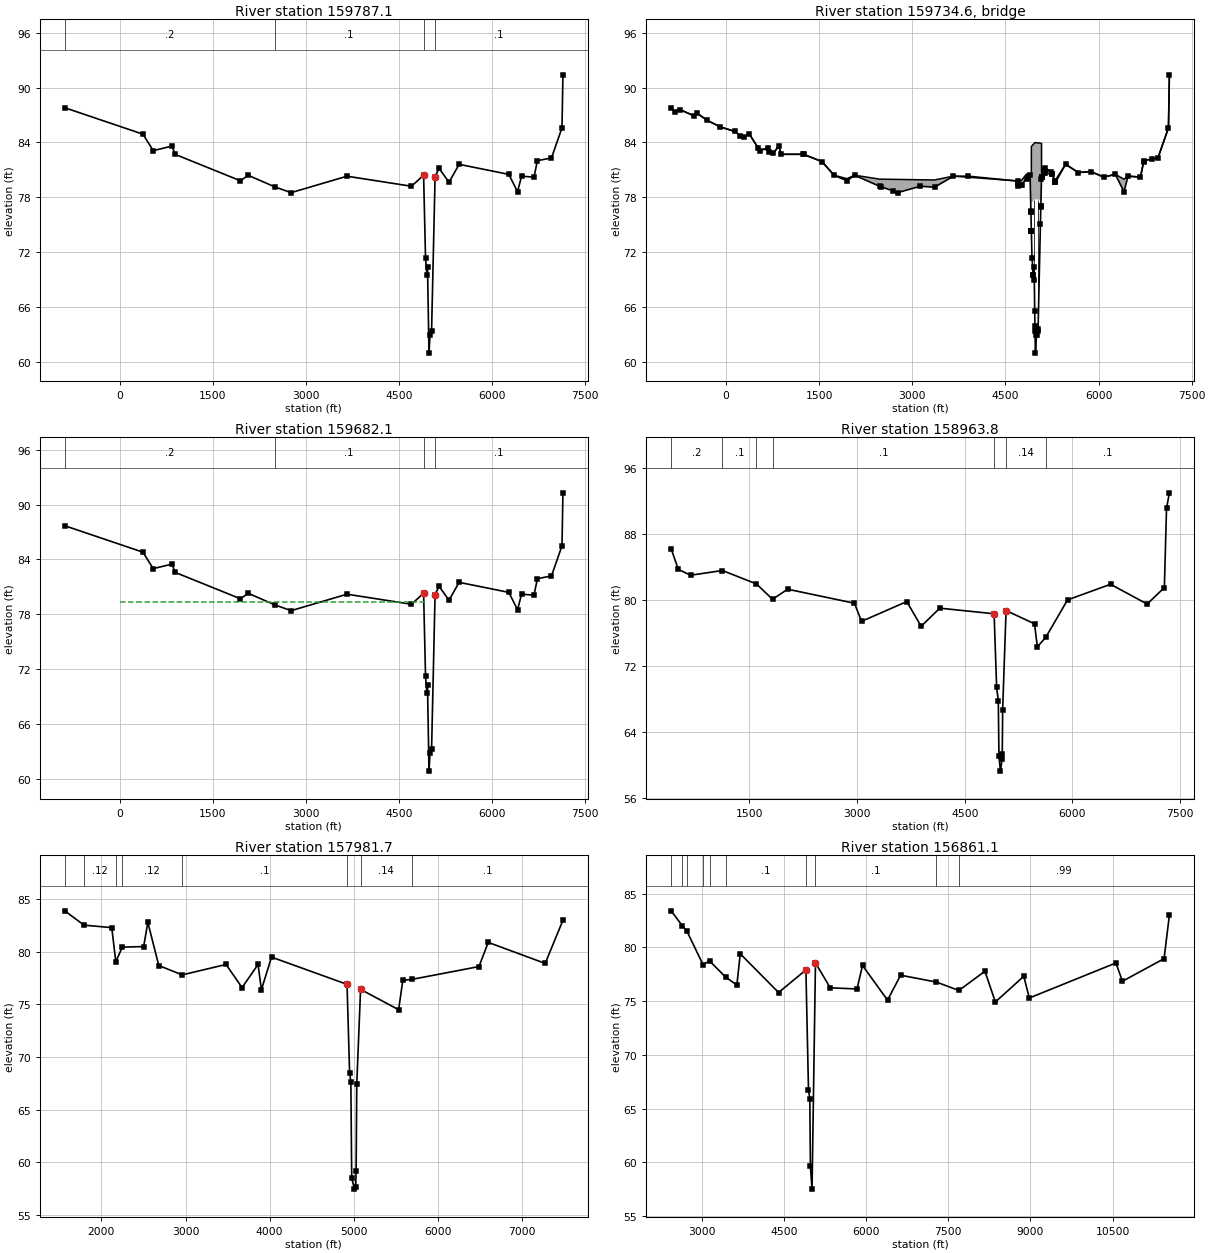
Type RM Length L Ch R = 1 ,159787.1,105,105,105
BEGIN DESCRIPTION:
Upstream Section of Bridge/Culvert/Weir
END DESCRIPTION:
XS GIS Cut Line= 6
      3107669.31     13914230.63      3108308.79     13912093.13
      3108462.17     13910836.06      3109355.85     13909459.98
      3109711.86     13908513.73      3109277.35     13906761.07
#Sta/Elev= 30
  -886.2    87.8     375    84.9     540    83.1     845    83.6     890    82.7
  1945.3    79.8  2070.3    80.4    2500   79.13  2761.8    78.5  3662.6    80.3
  4700.8    79.2  4896.3   80.41  4927.5   71.33  4949.5   69.52  4959.2   70.35
  4983.4   60.93  4999.5   62.94  5024.7    63.3  5081.2   80.24  5144.9   81.17
  5305.7   79.64    5469    81.6  6269.9    80.5  6409.9    78.6  6474.9    80.3
  6674.9    80.2  6729.9      82  6956.9    82.3  7126.2    85.6  7141.2    91.4
#Mann= 4 , 1 , 0
  -886.2      .2       0    2500      .1       0  4896.3    .035       0
  5081.2      .1       0
#XS Ineff= 2 , 0
       0    4900    79.3    5080       0    79.3
Permanent Ineff=
       F       F
Bank Sta=4896.3,5081.2
XS Rating Curve= 0 ,0
Exp/Cntr=0.5,0.3

Type RM Length L Ch R = 3 ,159734.6,,,
BEGIN DESCRIPTION:
IMPERIAL VALLEY DRIVE
Structure ID: P00-52
END DESCRIPTION:
Bridge Culvert--1,0,-1,-1, 0
Deck Dist Width WeirC Skew NumUp NumDn MinLoCord MaxHiCord MaxSubmerge Is_Ogee
10,85,2.6,0, 60, 60, , , 0.95, 0, 1,1,,
  -886.2  -826.2  -746.2  -516.2  -471.2  -301.2     -95     140     230     280
     375     540     675     690     760     845     890    1245  1543.5  1738.5
  1945.3  2070.3  2471.8  2761.8  3127.7  3357.7  3662.6  4695.8  4700.8  4756.8
  4841.8  4896.3 4910.01  4910.1 4917.19  4917.3  4975.3 5069.79  5069.9  5081.4
 5081.51  5116.3  5117.8  5142.1  5144.9  5236.9  5297.3  5305.7    5469    5674
  5874.9  6084.9  6269.9  6409.9  6474.9  6674.9  6729.9  6956.9  7126.2  7141.2
    87.8    87.3    87.6    86.9    87.2    86.4    85.7    85.2    84.7    84.6
    84.9    83.1    83.4      83    82.8    83.6    82.7    82.7   81.91   80.41
   80.03   80.41   79.98   79.95   79.91   79.89   80.31   79.78   79.76   79.83
   80.55   80.42   80.31   80.31   80.36   83.56   83.98   83.91   83.91    83.9
    80.7   81.01   80.93   80.95   81.18   80.78   79.73   79.88   81.61   80.71
   80.81   80.21   80.51   79.97   80.31   80.21   82.01    82.3    85.6    91.4
    87.8    87.3    87.6    86.9    87.2    86.4    85.7    85.2    84.7    84.6
    84.9    83.1    83.4      83    82.8    83.6    82.7    82.7    81.9    80.4
    79.8    80.4    79.2    78.5    79.2    79.1    80.3   79.77    79.2   79.34
   80.04   80.41   76.42   77.31   77.36   77.36   77.78   77.71   77.02   80.24
   80.25      81   80.62   80.74   81.17   80.77   79.72   79.64    81.6    80.7
    80.8    80.2    80.5    78.6    80.3    80.2      82    82.3    85.6    91.4
  -886.2  -826.2  -746.2  -516.2  -471.2  -301.2     -95     140     230     280
     375     540     675     690     760     845     890    1245  1543.5  1738.5
  1945.3  2070.3  2471.8  2761.8  3127.7  3357.7  3662.6  4695.8  4700.8  4756.8
  4841.8  4896.3 4910.01  4910.1 4917.19  4917.3  4975.3 5069.79  5069.9  5081.4
 5081.51  5116.3  5117.8  5142.1  5144.9  5236.9  5297.3  5305.7    5469    5674
  5874.9  6084.9  6269.9  6409.9  6474.9  6674.9  6729.9  6956.9  7126.2  7141.2
    87.8    87.3    87.6    86.9    87.2    86.4    85.7    85.2    84.7    84.6
    84.9    83.1    83.4      83    82.8    83.6    82.7    82.7   81.91   80.41
   80.03   80.41   79.98   79.95   79.91   79.89   80.31   79.78   79.76   79.83
   80.55   80.42   80.31   80.31   80.36   83.56   83.98   83.91   83.91    83.9
    80.7   81.01   80.93   80.95   81.18   80.78   79.73   79.88   81.61   80.71
   80.81   80.21   80.51   79.97   80.31   80.21   82.01    82.3    85.6    91.4
    87.7    87.2    87.5    86.8    87.1    86.3    85.6    85.1    84.6    84.5
    84.8      83    83.3    82.9    82.7    83.5    82.6    82.6    81.8    80.3
    79.7    80.3    79.1    78.4    79.1      79    80.2   79.67    79.1   79.24
   79.94   80.31   76.32   77.21   77.26   77.26   77.68   77.61   76.92   80.14
   80.15    80.9   80.52   80.64   81.07   80.67   79.62   79.54    81.5    80.6
    80.7    80.1    80.4    78.5    80.2    80.1    81.9    82.2    85.5    91.3
Pier Skew, UpSta & Num, DnSta & Num=  ,4964.6, 2 ,4964.6, 2 , 0 , 0 , 0 ,,
     1.4     1.4
   67.54   78.74
     1.4     1.4
   67.44   78.64
Pier Skew, UpSta & Num, DnSta & Num=  ,5019.9, 2 ,5019.9, 2 , 0 , 0 , 0 ,,
     1.4     1.4
   62.52   78.74
     1.4     1.4
   62.42   78.64
Abutment Skew #Up #Dn= , 2 , 2
  4909.9  4949.6
   77.31   69.53
  4909.9  4949.6
   77.21   69.43
BR Coef= 1 , 1 , 0 ,1.25, 0 ,,,0.8,0,2,0,
WSPro=,,,, 1 ,,,, 0 ,,,, 0 ,,,,-1 ,-1 ,-1 , 0 , 0 , 0 , 0 , 0
BR U #Sta/Elev= 94
  -886.2    87.8  -826.2    87.3  -746.2    87.6  -516.2    86.9  -471.2    87.2
  -301.2    86.4     -95    85.7     140    85.2     230    84.7     280    84.6
     375    84.9     515    83.4     540    83.1     675    83.4     690      83
     760    82.8     845    83.6     890    82.7    1245    82.7  1252.2   82.68
  1543.5    81.9  1738.5    80.4  1945.3    79.8  2070.3    80.4  2471.8    79.2
    2500   79.13  2686.8    78.7  2761.8    78.5  3127.7    79.2  3357.7    79.1
  3662.6    80.3  3902.6    80.3  4695.8   79.77  4698.5   79.46  4700.8    79.2
  4756.8   79.34  4758.8   79.34  4841.8   80.04  4858.2   80.18  4896.3   80.41
  4909.9   76.45 4910.01   76.42  4910.1   76.39 4917.19   74.33  4917.3    74.3
 4917.41   74.27  4927.5   71.33  4949.5   69.52  4949.6   69.53  4959.2   70.35
  4964.6    68.9  4971.2   65.54  4974.4   63.91  4975.3   63.35  4983.4   60.93
  4999.5   62.94  5013.5   62.91  5019.9    63.6  5024.7    63.3  5062.9   75.02
  5069.7   76.96 5069.79   76.99  5069.9   77.02  5080.4   80.01  5081.2   80.24
 5081.29   80.24  5081.4   80.24 5081.51   80.25  5116.3      81  5117.8   80.62
  5132.6   80.69  5142.1   80.74  5144.9   81.17  5236.9   80.77  5250.2   80.54
  5251.6   80.51    5296   79.73  5297.3   79.72  5301.3   79.68  5305.7   79.64
    5469    81.6    5674    80.7  5874.9    80.8  6084.9    80.2  6269.9    80.5
  6409.9    78.6  6474.9    80.3  6674.9    80.2  6727.2   81.91  6729.9      82
  6859.5   82.17  6956.9    82.3  7126.2    85.6  7141.2    91.4
BR U #Mann= 4
  -886.2      .2    2500      .1  4896.3    .035  5081.2      .1
BR U Banks=4896.3,5081.2
BR D #Sta/Elev= 94
  -886.2    87.7  -826.2    87.2  -746.2    87.5  -516.2    86.8  -471.2    87.1
  -301.2    86.3     -95    85.6     140    85.1     230    84.6     280    84.5
     375    84.8     515    83.3     540      83     675    83.3     690    82.9
     760    82.7     845    83.5     890    82.6    1245    82.6  1252.2   82.58
  1543.5    81.8  1738.5    80.3  1945.3    79.7  2070.3    80.3  2471.8    79.1
    2500   79.03  2686.8    78.6  2761.8    78.4  3127.7    79.1  3357.7      79
  3662.6    80.2  3902.6    80.2  4695.8   79.67  4698.5   79.36  4700.8    79.1
  4756.8   79.24  4758.8   79.24  4841.8   79.94  4858.2   80.08  4896.3   80.31
  4909.9   76.35 4910.01   76.32  4910.1   76.29 4917.19   74.23  4917.3    74.2
 4917.41   74.17  4927.5   71.23  4949.5   69.42  4949.6   69.43  4959.2   70.25
  4964.6    68.8  4971.2   65.44  4974.4   63.81  4975.3   63.25  4983.4   60.83
  4999.5   62.84  5013.5   62.81  5019.9    63.5  5024.7    63.2  5062.9   74.92
  5069.7   76.86 5069.79   76.89  5069.9   76.92  5080.4   79.91  5081.2   80.14
 5081.29   80.14  5081.4   80.14 5081.51   80.15  5116.3    80.9  5117.8   80.52
  5132.6   80.59  5142.1   80.64  5144.9   81.07  5236.9   80.67  5250.2   80.44
  5251.6   80.41    5296   79.63  5297.3   79.62  5301.3   79.58  5305.7   79.54
    5469    81.5    5674    80.6  5874.9    80.7  6084.9    80.1  6269.9    80.4
  6409.9    78.5  6474.9    80.2  6674.9    80.1  6727.2   81.81  6729.9    81.9
  6859.5   82.07  6956.9    82.2  7126.2    85.5  7141.2    91.3
BR D #Mann= 4
  -886.2      .2    2500      .1  4896.3    .035  5081.2      .1
BR D Banks=4896.3,5081.2
BC Design=,, 0 ,, 0 ,,,,,,
BC HTab HWMax=91.4
BC Use User HTab Curves=0
BC User HTab FreeFlow(D)= 0

Type RM Length L Ch R = 1 ,159682.1,718.3,718.3,718.3
BEGIN DESCRIPTION:
Downstream Section of Bridge/Culvert/Weir
END DESCRIPTION:
XS GIS Cut Line= 6
      3107774.15     13914236.45      3108413.63     13912098.95
      3108567.01     13910841.88      3109460.69      13909465.8
       3109816.7     13908519.55      3109382.19     13906766.89
#Sta/Elev= 30
  -886.2   87.68     375   84.78     540   82.98     845   83.48     890   82.58
  1945.3   79.68  2070.3   80.28    2500   79.01  2761.8   78.38  3662.6   80.18
  4700.8   79.08  4896.3   80.29  4927.5   71.21  4949.5    69.4  4959.2   70.23
  4983.4   60.81  4999.5   62.82  5024.7   63.18  5081.2   80.12  5144.9   81.05
  5305.7   79.52    5469   81.48  6269.9   80.38  6409.9   78.48  6474.9   80.18
  6674.9   80.08  6729.9   81.88  6956.9   82.18  7126.2   85.48  7141.2   91.28
#Mann= 4 , 1 , 0
  -886.2      .2       0    2500      .1       0  4896.3    .035       0
  5081.2      .1       0
#XS Ineff= 2 , 0
       0    4900    79.3    5080       0    79.3
Permanent Ineff=
       F       F
Bank Sta=4896.3,5081.2
XS Rating Curve= 0 ,0
Exp/Cntr=0.5,0.3

Type RM Length L Ch R = 1 ,158963.8,937.8,982.1,995.6
BEGIN DESCRIPTION:
Cross Section 158963.8
END DESCRIPTION:
XS GIS Cut Line= 5
      3109709.64     13913233.24      3110308.14     13912439.88
      3110445.87     13909142.42      3110473.71     13908673.62
      3110339.16     13906497.73
#Sta/Elev= 30
   408.8    86.2   508.8    83.7   678.8      83  1123.2   83.57  1597.9   81.94
  1821.3   80.08  2032.6    81.3  2962.6    79.6  3062.6    77.4  3692.6    79.8
  3892.6    76.8  4152.6      79 4909.57   78.32 4944.67    69.4 4968.07   67.73
 4977.17   61.02 4998.27   59.22 5020.77   60.66 5023.37   61.32 5028.77   66.67
 5076.17   78.71  5472.6    77.1  5512.6    74.3  5631.9   75.49  5932.6      80
  6532.6    81.9  7042.6    79.5  7282.6    81.5  7312.6    91.1  7352.6      93
#Mann= 7 , 1 , 0
   408.8      .2       0  1123.2      .1       0  1597.9     .07       0
  1821.3      .1       0 4909.57    .035       0 5076.17     .14       0
  5631.9      .1       0
Bank Sta=4909.57,5076.17
XS Rating Curve= 0 ,0
Exp/Cntr=0.3,0.1

Type RM Length L Ch R = 1 ,157981.7,669.5,1120.6,1357.8
BEGIN DESCRIPTION:
Cross Section 157981.7
END DESCRIPTION:
XS GIS Cut Line= 6
       3110873.9     13912246.98      3111184.74     13911367.73
      3111455.02     13908832.77      3111436.38     13907793.61
      3111268.62     13907290.35      3111231.92     13906430.27
#Sta/Elev= 30
  1563.4    83.9  1793.1   82.54  2122.9    82.3  2170.6   79.07  2248.8   80.45
  2501.9    80.5  2551.9    82.8  2681.9    78.7  2959.8   77.81  3481.9    78.8
  3671.9    76.6  3861.9    78.8  3901.9    76.4  4021.9    79.5  4919.8   76.91
  4950.4    68.5  4965.1   67.65  4975.6    58.5  5008.3   57.44  5022.4   57.64
  5027.7    59.2  5035.3   67.41  5080.8   76.43  5533.1    74.5  5583.1    77.3
  5689.5   77.38  6488.4    78.6  6598.4    80.9  7275.3    78.9  7486.4      83
#Mann= 8 , 1 , 0
  1563.4      .1       0  1793.1     .12       0  2170.6      .1       0
  2248.8     .12       0  2959.8      .1       0  4919.8    .035       0
  5080.8     .14       0  5689.5      .1       0
Bank Sta=4919.8,5080.8
XS Rating Curve= 0 ,0
Exp/Cntr=0.3,0.1

Type RM Length L Ch R = 1 ,156861.1,599.1,579.5,452.6
BEGIN DESCRIPTION:
Cross Section 156861.1
END DESCRIPTION:
XS GIS Cut Line= 6
      3111445.71     13911908.23      3111715.97     13910706.03
       3111874.4     13909829.98      3112349.71     13909475.83
       3112675.9     13908716.27      3112781.11     13903157.71
#Sta/Elev= 30
  2437.6    83.4  2642.4      82  2723.7   81.52  3019.9   78.39  3139.3   78.74
  3431.4   77.24  3637.6    76.5  3699.8    79.4  4399.8    75.8  4898.9    77.9
  4946.2   66.74  4970.5   65.94  4980.9   59.65  5010.9   57.51  5073.8   78.56
  5342.8   76.24  5832.8   76.13  5932.8   78.32  6389.5   75.09  6629.5   77.41
  7284.3   76.77    7693   75.99  8169.5   77.78  8359.5   74.92  8879.5   77.31
  8979.5   75.29 10561.8   78.55 10681.8   76.85 11441.8   78.95 11539.1      83
#Mann= 10 , 1 , 0
  2437.6     .12       0  2642.4      .1       0  2723.7     .12       0
  3019.9      .1       0  3139.3     .12       0  3431.4      .1       0
  4898.9    .035       0  5073.8      .1       0  7284.3     .12       0
    7693     .99       0
Bank Sta=4898.9,5073.8
XS Rating Curve= 0 ,0
Exp/Cntr=0.3,0.1