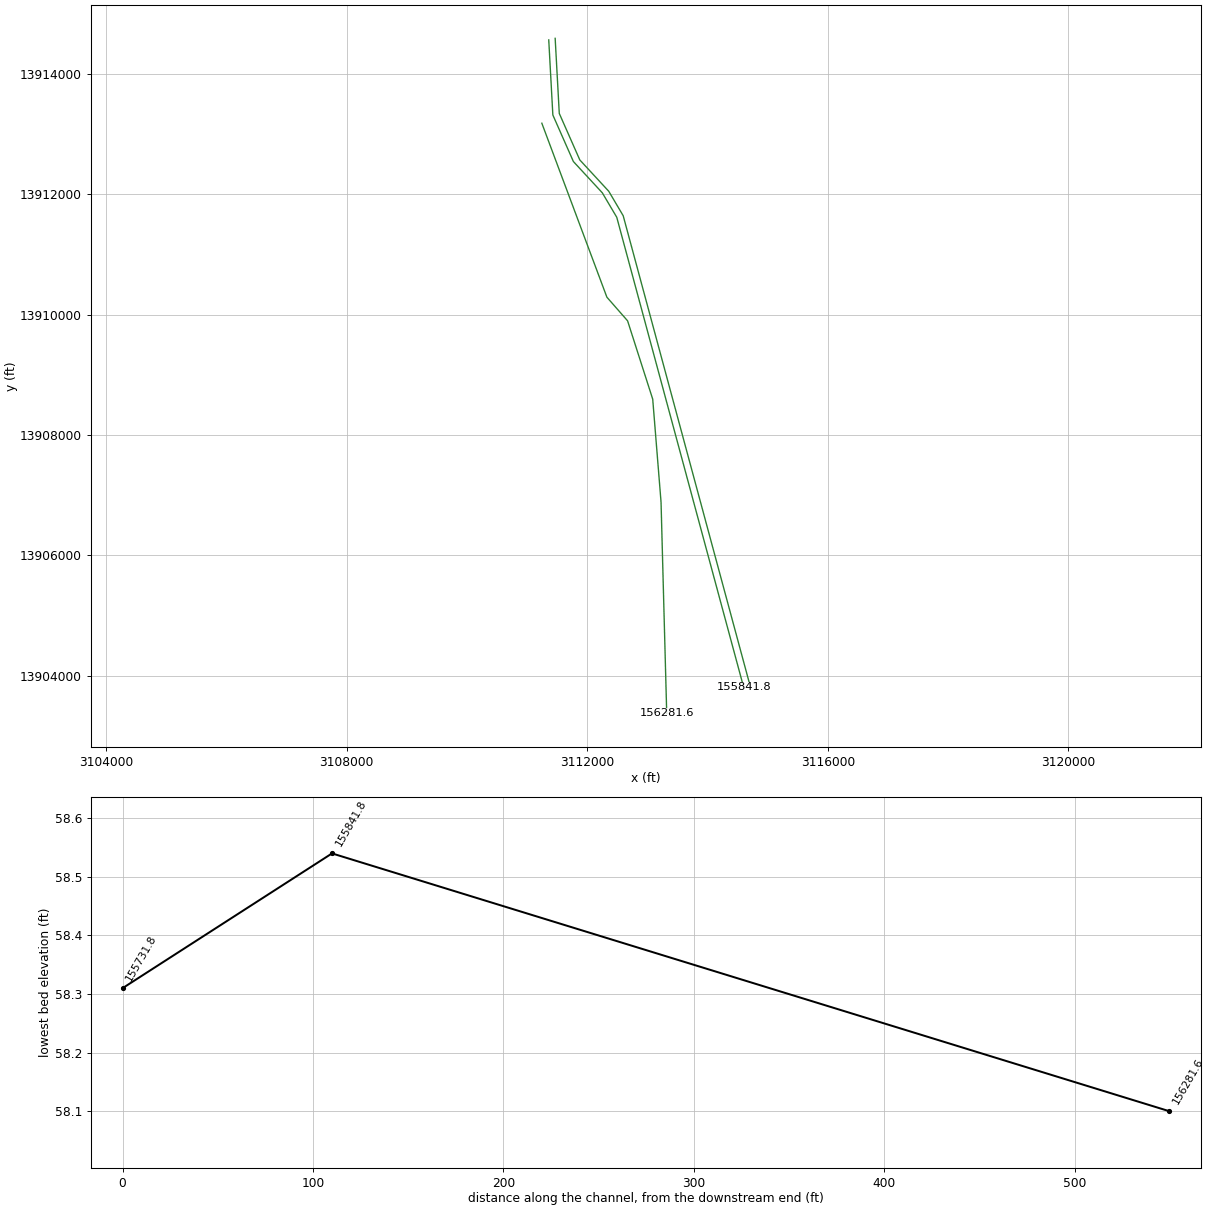
HEC-RAS study P100-00-00.prj: P100-00-00

--- P100-00-00.g01 (geometry) --- (continued)

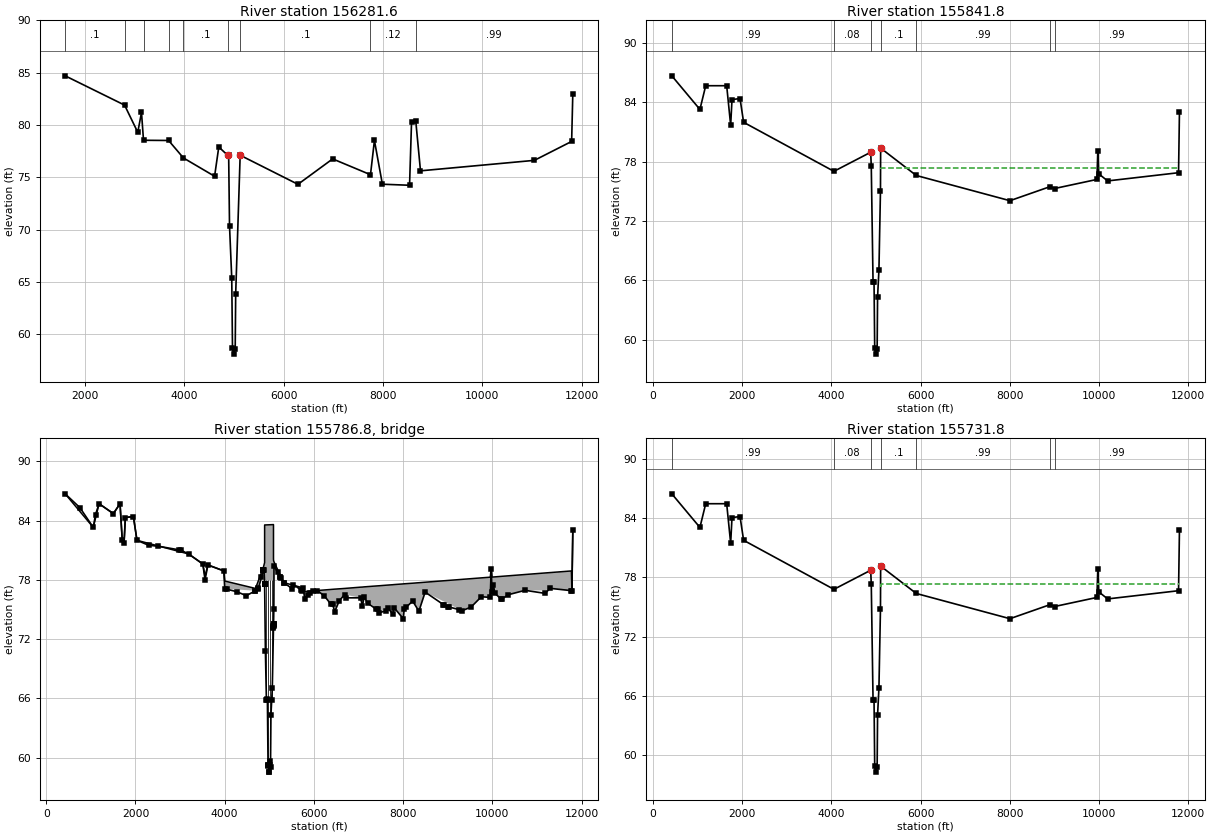
Type RM Length L Ch R = 1 ,156281.6,507.8,439.8,298.3
BEGIN DESCRIPTION:
Cross Section 156281.6-Interpolated
END DESCRIPTION:
XS GIS Cut Line= 6
      3111245.19     13913183.07       3112326.6     13910291.22
      3112670.69     13909897.97      3113088.52     13908595.34
      3113226.88     13906884.56      3113321.14      13903372.2
#Sta/Elev= 30
  1607.5    84.7  2802.5    81.9  3067.5    79.3  3142.6    81.2  3182.9   78.54
  3687.7   78.52  3986.1   76.85  4612.6    75.1    4697    77.9    4877    77.1
  4895.7   77.13    4913   70.35  4957.7   65.37  4972.7   58.71  4995.4    58.1
  5027.4   58.63  5037.1   63.88    5127   77.11  6289.5   74.33  6987.5   76.76
  7748.1   75.25  7827.5   78.52  7987.5   74.34  8533.9   74.24  8573.9   80.29
  8659.5   80.35  8753.9   75.62 11043.9   76.62 11793.9   78.43 11817.5      83
#Mann= 9 , 1 , 0
  1607.5      .1       0  2802.5     .12       0  3182.9      .1       0
  3687.7     .12       0  3986.1      .1       0    4877    .035       0
    5127      .1       0  7748.1     .12       0  8659.5     .99       0
#XS Ineff= 2 , 0
       0                  8659.5       0   80.35
Permanent Ineff=
       F       F
Bank Sta=4877,5127
XS Rating Curve= 0 ,0
Exp/Cntr=0.5,0.3

Type RM Length L Ch R = 1 ,155841.8,110,110,110
BEGIN DESCRIPTION:
Upstream Section of Bridge/Culvert/Weir
END DESCRIPTION:
XS GIS Cut Line= 6
      3111359.94     13914568.22      3111428.24     13913319.68
      3111769.56      13912546.6      3112250.51     13912026.17
      3112490.71     13911619.61      3114601.19     13903802.54
#Sta/Elev= 30
   424.3   86.69  1054.3   83.29  1184.3   85.69  1654.3   85.69  1743.7   81.69
  1773.7   84.29  1953.7   84.39  2033.7   81.99  4058.6   77.03  4882.8   78.96
  4895.7   77.57  4935.5   65.84  4957.7   65.81  4972.7   59.15  4995.4   58.54
  5027.4   59.07  5037.1   64.32  5067.3   67.02  5102.1   75.08  5105.8   79.38
    5904   76.61  8004.2   74.06  8903.3   75.48  9003.3   75.29  9954.2   76.21
  9974.2   79.13  9994.2   76.78 10194.2   76.06 11784.2   76.89 11804.3   82.99
#Mann= 7 , 1 , 0
   424.3     .99       0  4058.6     .08       0  4882.8    .032       0
  5105.8      .1       0    5904     .99       0  8903.3     .08       0
  9003.3     .99       0
#XS Ineff= 2 , 0
       0    4886   77.35    5104       0   77.35
Permanent Ineff=
       F       F
Bank Sta=4882.8,5105.8
XS Rating Curve= 0 ,0
Exp/Cntr=0.5,0.3

Type RM Length L Ch R = 3 ,155786.8,,,
BEGIN DESCRIPTION:
WEST HARDY ROAD
Structure ID: P00-49
END DESCRIPTION:
Bridge Culvert--1,0,-1,-1, 0
Deck Dist Width WeirC Skew NumUp NumDn MinLoCord MaxHiCord MaxSubmerge Is_Ogee
10,90,2.6,0, 60, 60, , , 0.95, 0, 1,1,,
   424.3  1054.3  1184.3  1504.3  1654.3  1703.7  1743.7  1773.7  1953.7  2033.7
  3195.4    3510    3560  3623.3  3981.6  4001.6  4690.3  4751.5 4868.91  4882.8
  4895.3 4895.39  4895.5  4895.8  5093.7  5094.4 5094.51 5095.24 5095.35  5102.1
  5105.8  5324.2  5762.8  5792.8  6077.7  6467.7  6687.7  7046.6  7086.6  7126.6
  7456.6  7654.2  7774.2  7794.2  8004.2  8024.2  8214.2  8354.2  8494.2  9324.2
  9954.2  9974.2  9994.2 10024.2 10054.2 10194.2 10734.2   11773 11784.2 11804.3
    86.7    83.3    85.7    84.7    85.7      82    81.7    84.3    84.4      82
   80.61   79.61   78.36   79.51   78.91   77.88   77.13   77.86   79.29   79.53
   79.74   79.99   83.29   83.55   83.59   83.44   80.14   80.01   79.99   79.87
   79.82   77.72   77.18   76.82   76.92   77.06   77.13   77.26   77.27   77.29
    77.4   77.47   77.51   77.52   77.59    77.6   77.66   77.71   77.76   78.05
   78.27   79.15   78.28   78.29    78.3   78.35   78.54    78.9    76.9      83
    86.7    83.3    85.7    84.7    85.7      82    81.7    84.3    84.4      82
    80.6    79.6      78    79.5    78.9    77.1    76.9   77.04   79.02   78.97
   77.62   77.69   77.69   77.95   77.99   77.84   77.84   77.71   73.53   75.09
   79.39   77.71   77.17    76.1   76.91   74.79   76.51   76.18   75.37   76.23
   74.66   75.18    74.5    75.2   74.07   75.02   75.85   74.83   76.76   74.88
   76.22   79.14   76.79    77.5   76.65   76.07   76.94   76.91    76.9      83
   424.3  1054.3  1184.3  1504.3  1654.3  1703.7  1743.7  1773.7  1953.7  2033.7
  3195.4    3510    3560  3623.3  3981.6  4001.6  4690.3  4751.5 4868.91  4882.8
  4895.3 4895.39  4895.5  4895.8  5093.7  5094.4 5094.51 5095.24 5095.35  5102.1
  5105.8  5324.2  5762.8  5792.8  6077.7  6467.7  6687.7  7046.6  7086.6  7126.6
  7456.6  7654.2  7774.2  7794.2  8004.2  8024.2  8214.2  8354.2  8494.2  9324.2
  9954.2  9974.2  9994.2 10024.2 10054.2 10194.2 10734.2   11773 11784.2 11804.3
    86.7    83.3    85.7    84.7    85.7      82    81.7    84.3    84.4      82
   80.61   79.61   78.36   79.51   78.91   77.88   77.13   77.86   79.29   79.53
   79.74   79.99   83.29   83.55   83.59   83.44   80.14   80.01   79.99   79.87
   79.82   77.72   77.18   76.82   76.92   77.06   77.13   77.26   77.27   77.29
    77.4   77.47   77.51   77.52   77.59    77.6   77.66   77.71   77.76   78.05
   78.27   79.15   78.28   78.29    78.3   78.35   78.54    78.9    76.9      83
   86.49   83.09   85.49   84.49   85.49   81.79   81.49   84.09   84.19   81.79
   80.39   79.39   77.79   79.29   78.69   76.89   76.69   76.83   78.81   78.76
   77.41   77.48   77.48   77.74   77.78   77.63   77.63    77.5   73.32   74.88
   79.18    77.5   76.96   75.89    76.7   74.58    76.3   75.97   75.16   76.02
   74.45   74.97   74.29   74.99   73.86   74.81   75.64   74.62   76.55   74.67
   76.01   78.93   76.58   77.29   76.44   75.86   76.73    76.7   76.69   82.79
Pier Skew, UpSta & Num, DnSta & Num=  ,4935.4, 2 ,4935.4, 2 , 0 , 0 , 0 ,,
     1.3     1.3
   64.86   78.99
     1.3     1.3
   64.65   78.78
Pier Skew, UpSta & Num, DnSta & Num=  ,4975.6, 2 ,4975.6, 2 , 0 , 0 , 0 ,,
     1.3     1.3
   58.27   79.04
     1.3     1.3
   58.06   78.83
Pier Skew, UpSta & Num, DnSta & Num=  ,5014.8, 2 ,5014.8, 2 , 0 , 0 , 0 ,,
     1.3     1.3
    58.6   79.05
     1.3     1.3
   58.39   78.84
Pier Skew, UpSta & Num, DnSta & Num=  ,5055.4, 2 ,5055.4, 2 , 0 , 0 , 0 ,,
     1.3     1.3
   64.79   79.02
     1.3     1.3
   64.58   78.81
BR Coef= 1 , 1 , 0 ,1.25, 0 ,,,0.8,0,2,0,
WSPro=,,,, 1 ,,,, 0 ,,,, 0 ,,,,-1 ,-1 ,-1 , 0 , 0 , 0 , 0 , 0
BR U #Sta/Elev= 128
   424.3    86.7   754.3    85.3  1054.3    83.3  1104.3    84.6  1184.3    85.7
  1504.3    84.7  1654.3    85.7  1703.7      82  1743.7    81.7  1773.7    84.3
  1953.7    84.4  2033.7      82  2293.7    81.5  2511.1    81.4  2964.9   81.04
  3021.1      81  3195.4    80.6    3510    79.6    3560      78  3623.3    79.5
  3981.6    78.9  4001.6    77.1  4058.6   77.04  4271.6    76.8  4483.9    76.4
  4690.3    76.9  4690.9    76.9  4751.5   77.04  4756.9   77.13  4823.8   78.26
 4868.91   79.02    4869   79.02  4869.1   79.02  4869.2   79.02  4882.8   78.97
  4895.3   77.62 4895.39   77.61  4895.5    77.6 4895.61   77.59  4895.7   77.58
  4895.8   77.54    4913    70.8  4935.5   65.85  4943.7   65.93  4957.7   65.82
  4972.7   59.16  4975.7    59.3  4980.3   59.28  4995.1   58.56  4995.4   58.55
  5010.5   59.29  5014.9   59.66  5027.4   59.08  5037.1   64.33  5055.5   65.85
  5067.3   67.03  5093.7   73.14 5094.29   73.28  5094.4   73.31 5094.51   73.33
 5095.15   73.48 5095.24    73.5 5095.35   73.53  5095.5   73.56  5102.1   75.09
  5105.8   79.39  5184.8   78.78  5248.9   78.29  5249.1   78.29  5258.1   78.22
  5324.2   77.71  5324.8   77.71  5511.6   77.12  5541.6   77.52  5721.6   76.94
  5742.8   76.85  5762.8   77.17  5792.8    76.1  5872.8   76.49    5904   76.62
  5972.8   76.92  6077.7   76.91  6237.7   76.36  6377.7   75.55  6417.7   75.52
  6467.7   74.79  6567.7   75.87  6687.7   76.51  6717.7   76.18  7046.6   76.18
  7086.6   75.37  7126.6   76.23  7216.6   75.61  7396.6   75.03  7436.6   75.09
  7456.6   74.66  7624.2   74.88  7654.2   75.18  7774.2    74.5  7794.2    75.2
  8004.2   74.07  8024.2   75.02  8074.2   75.25  8214.2   75.85  8354.2   74.83
  8494.2   76.76  8903.3   75.49  8924.2   75.43  9003.3    75.3  9024.2   75.26
  9254.2   74.99  9324.2   74.88  9524.2   75.25  9754.2   76.29  9954.2   76.22
  9974.2   79.14  9994.2   76.79 10024.2    77.5 10054.2   76.65 10194.2   76.07
 10224.2   76.08 10354.2   76.49 10734.2   76.94 11184.2   76.63 11294.2   77.14
   11773   76.91 11784.2    76.9 11804.3      83
BR U #Mann= 7
   424.3     .99  4058.6     .08  4882.8    .032  5105.8      .1    5904     .99
  8903.3     .08  9003.3     .99
BR U Banks=4882.8,5105.8
BR D #Sta/Elev= 128
   424.3   86.49   754.3   85.09  1054.3   83.09  1104.3   84.39  1184.3   85.49
  1504.3   84.49  1654.3   85.49  1703.7   81.79  1743.7   81.49  1773.7   84.09
  1953.7   84.19  2033.7   81.79  2293.7   81.29  2511.1   81.19  2964.9   80.83
  3021.1   80.79  3195.4   80.39    3510   79.39    3560   77.79  3623.3   79.29
  3981.6   78.69  4001.6   76.89  4058.6   76.83  4271.6   76.59  4483.9   76.19
  4690.3   76.69  4690.9   76.69  4751.5   76.83  4756.9   76.92  4823.8   78.05
 4868.91   78.81    4869   78.81  4869.1   78.81  4869.2   78.81  4882.8   78.76
  4895.3   77.41 4895.39    77.4  4895.5   77.39 4895.61   77.38  4895.7   77.37
  4895.8   77.33    4913   70.59  4935.5   65.64  4943.7   65.72  4957.7   65.61
  4972.7   58.95  4975.7   59.09  4980.3   59.07  4995.1   58.35  4995.4   58.34
  5010.5   59.08  5014.9   59.45  5027.4   58.87  5037.1   64.12  5055.5   65.64
  5067.3   66.82  5093.7   72.93 5094.29   73.07  5094.4    73.1 5094.51   73.12
 5095.15   73.27 5095.24   73.29 5095.35   73.32  5095.5   73.35  5102.1   74.88
  5105.8   79.18  5184.8   78.57  5248.9   78.08  5249.1   78.08  5258.1   78.01
  5324.2    77.5  5324.8    77.5  5511.6   76.91  5541.6   77.31  5721.6   76.73
  5742.8   76.64  5762.8   76.96  5792.8   75.89  5872.8   76.28    5904   76.41
  5972.8   76.71  6077.7    76.7  6237.7   76.15  6377.7   75.34  6417.7   75.31
  6467.7   74.58  6567.7   75.66  6687.7    76.3  6717.7   75.97  7046.6   75.97
  7086.6   75.16  7126.6   76.02  7216.6    75.4  7396.6   74.82  7436.6   74.88
  7456.6   74.45  7624.2   74.67  7654.2   74.97  7774.2   74.29  7794.2   74.99
  8004.2   73.86  8024.2   74.81  8074.2   75.04  8214.2   75.64  8354.2   74.62
  8494.2   76.55  8903.3   75.28  8924.2   75.22  9003.3   75.09  9024.2   75.05
  9254.2   74.78  9324.2   74.67  9524.2   75.04  9754.2   76.08  9954.2   76.01
  9974.2   78.93  9994.2   76.58 10024.2   77.29 10054.2   76.44 10194.2   75.86
 10224.2   75.87 10354.2   76.28 10734.2   76.73 11184.2   76.42 11294.2   76.93
   11773    76.7 11784.2   76.69 11804.3   82.79
BR D #Mann= 7
   424.3     .99  4058.6     .08  4882.8    .032  5105.8      .1    5904     .99
  8903.3     .08  9003.3     .99
BR D Banks=4882.8,5105.8
BC Design=,, 0 ,, 0 ,,,,,,
BC HTab HWMax=86.69
BC Use User HTab Curves=0
BC User HTab FreeFlow(D)= 0

Type RM Length L Ch R = 1 ,155731.8,353,353,353
BEGIN DESCRIPTION:
Downstream Section of Bridge/Culvert/Weir
END DESCRIPTION:
XS GIS Cut Line= 6
      3111466.78     13914594.38      3111535.08     13913345.84
       3111876.4     13912572.76      3112357.35     13912052.33
      3112597.55     13911645.77      3114708.03      13903828.7
#Sta/Elev= 30
   424.3   86.46  1054.3   83.06  1184.3   85.46  1654.3   85.46  1743.7   81.46
  1773.7   84.06  1953.7   84.16  2033.7   81.76  4058.6    76.8  4882.8   78.73
  4895.7   77.34  4935.5   65.61  4957.7   65.58  4972.7   58.92  4995.4   58.31
  5027.4   58.84  5037.1   64.09  5067.3   66.79  5102.1   74.85  5105.8   79.15
    5904   76.38  8004.2   73.83  8903.3   75.25  9003.3   75.06  9954.2   75.98
  9974.2    78.9  9994.2   76.55 10194.2   75.83 11784.2   76.66 11804.3   82.76
#Mann= 7 , 1 , 0
   424.3     .99       0  4058.6     .08       0  4882.8    .032       0
  5105.8      .1       0    5904     .99       0  8903.3     .08       0
  9003.3     .99       0
#XS Ineff= 2 , 0
       0    4886   77.35    5104       0   77.35
Permanent Ineff=
       F       F
Bank Sta=4882.8,5105.8
XS Rating Curve= 0 ,0
Exp/Cntr=0.5,0.3