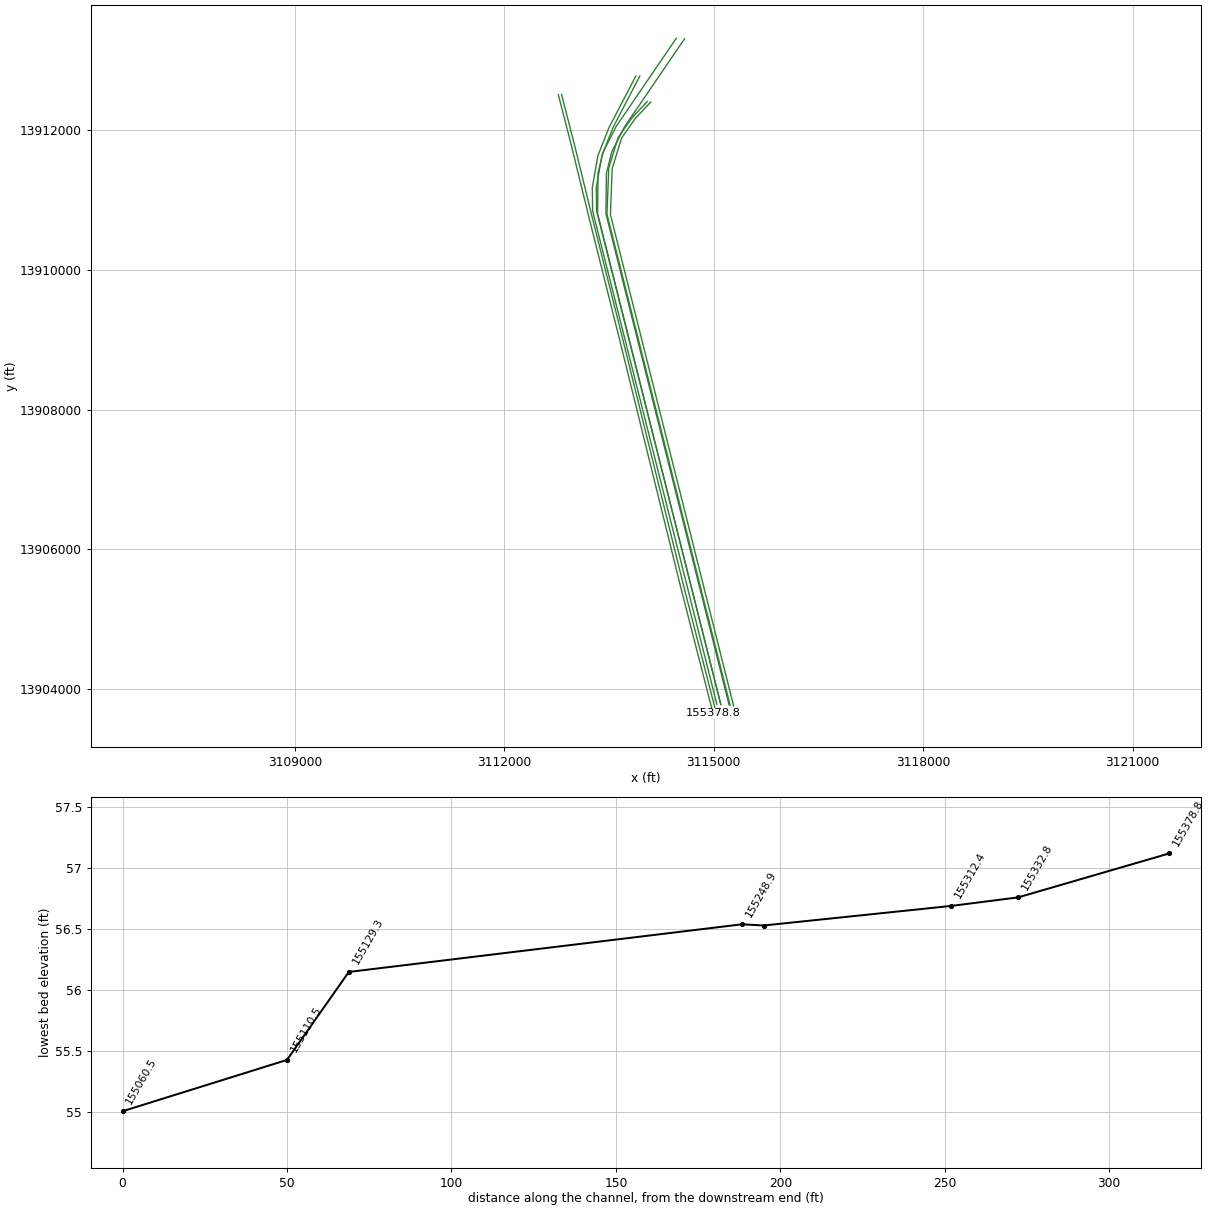
HEC-RAS study P100-00-00.prj: P100-00-00

--- P100-00-00.g01 (geometry) --- (continued)

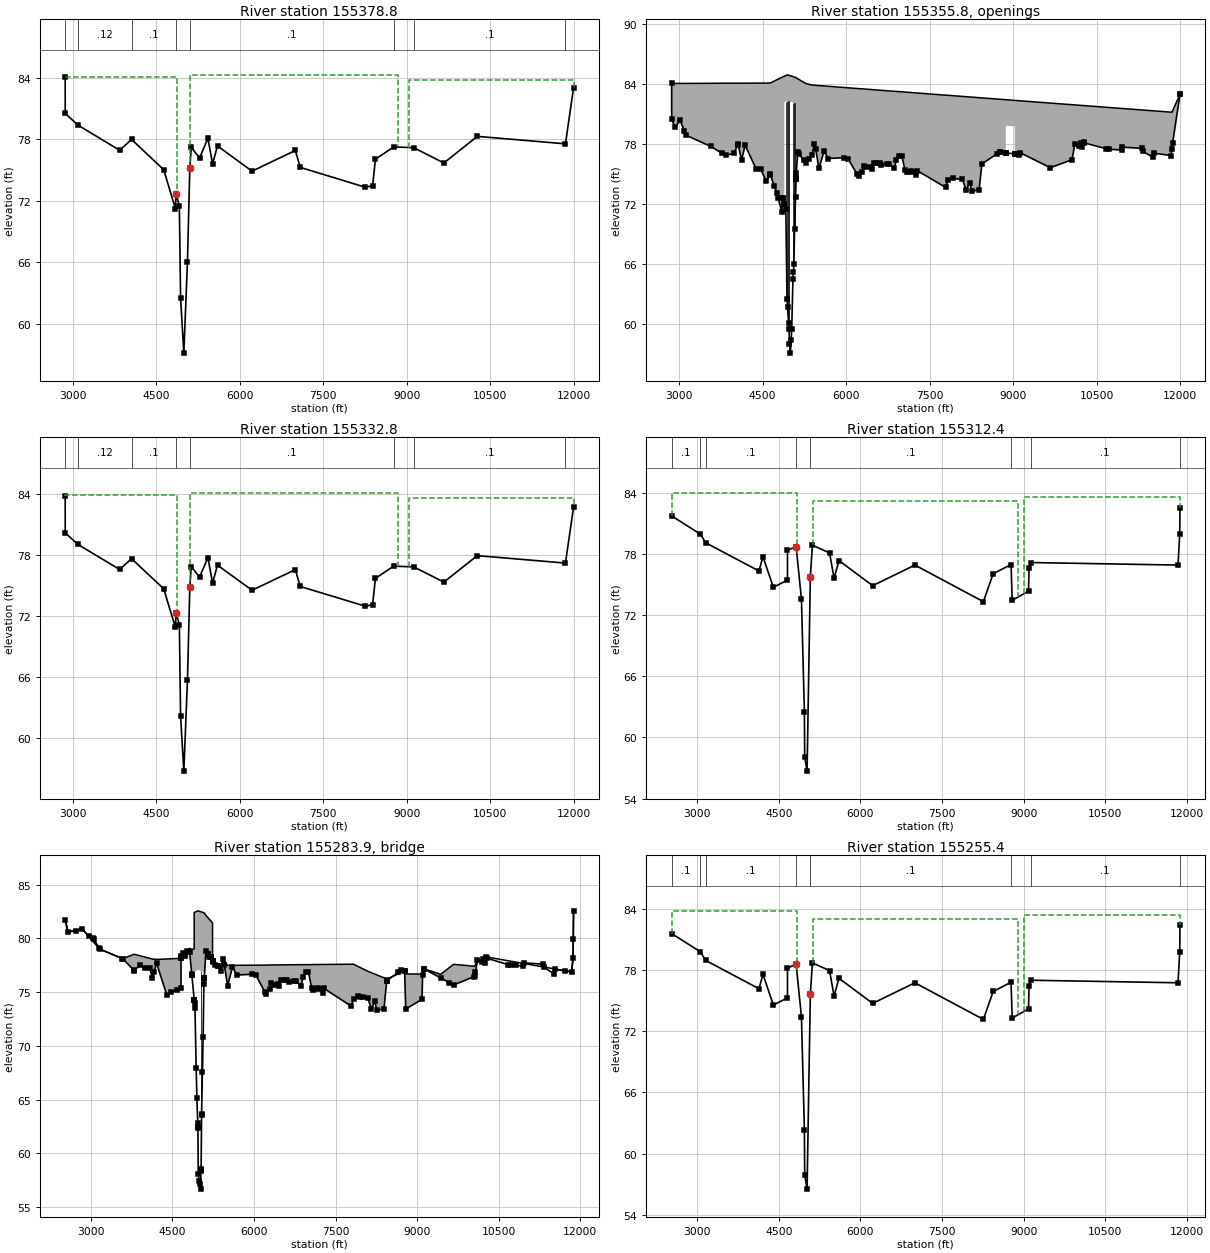
Type RM Length L Ch R = 1 ,155378.8,46,46,46
BEGIN DESCRIPTION:
Upstream Section of Bridge/Culvert/Weir
END DESCRIPTION:
XS GIS Cut Line= 6
       3112774.7     13912512.84      3112958.24     13911799.08
      3113213.86      13910753.9      3113655.83     13908989.63
      3114529.19     13905451.55      3114990.51     13903652.51
#Sta/Elev= 30
  2866.7   84.13  2866.8   80.53  3095.5   79.39    3845   76.93  4058.6   77.99
  4636.9   75.03  4846.9   71.23  4858.2   72.67  4917.7   71.51  4939.5   62.52
  4998.1   57.12  5063.1   66.05  5105.4   75.16    5131   77.22    5281   76.18
    5431    78.1  5513.8   75.62  5603.8   77.35  6223.9   74.89  7000.3   76.91
  7090.3   75.26  8260.3   73.32  8390.3   73.48  8440.3   76.06  8769.3   77.26
  9130.3   77.18  9670.3   75.69 10270.3   78.29 11854.7   77.56   12000   83.03
#Mann= 8 , 1 , 0
  2866.7      .1       0  3095.5     .12       0  4058.6      .1       0
  4858.2    .032       0  5105.4      .1       0  8769.3     .08       0
  9130.3      .1       0 11854.7      .2       0
#XS Ineff= 3 ,-1
    2866    4881    84.1    5113    8840    84.3    9041   12000    83.8
Permanent Ineff=
       F       F       F
Bank Sta=4858.2,5105.4
XS Rating Curve= 0 ,0
Exp/Cntr=0.5,0.3

Type RM Length L Ch R = 4 ,155355.8,,,
BEGIN DESCRIPTION:
MISSOURI PACIFIC RAILROAD
Structure ID: P00-47
END DESCRIPTION:
Bridge Culvert--1,0,-1,-1, 0
Deck Dist Width WeirC Skew NumUp NumDn MinLoCord MaxHiCord MaxSubmerge Is_Ogee
10,26,2.6,0, 60, 60, , , 0.95, 0, 1,1,,
  2866.7  2866.8  2926.8  3016.8  3130.1    3845  3981.8  4061.8  4121.8  4186.7
  4386.7  4466.7  4566.9  4636.9  4846.9  4858.2 4890.81  4890.9  4949.1 5102.29
  5102.4    5131    5281    5391    5431  5513.8  5603.8  5683.8  6033.9  6223.9
  6313.9  6464.8  6494.8  6864.8  7000.3  7090.3  7280.3  7790.3  7830.3  8090.3
  8160.3  8220.3  8260.3  8390.3  8440.3 8870.03  8870.1 9030.99  9031.1  9670.3
 10060.3 10110.3 10240.3 10270.3 10720.3 11320.3 11510.3 11840.3 11854.7   12000
    84.1    84.1    84.1    84.1    84.1   84.12   84.12   84.12   84.12   84.12
   84.13   84.13   84.13   84.14   84.71   84.74   84.82   84.82   84.96   84.68
   84.68   84.57   84.08   83.94   83.92   83.88   83.85   83.81   83.66   83.58
   83.55   83.48   83.47   83.31   83.26   83.22   83.14   82.92   82.91    82.8
   82.77   82.74   82.73   82.67   82.65   82.47   82.47    82.4    82.4   82.13
   81.97   81.95   81.89   81.88   81.69   81.44   81.36   81.22   81.21      83
    84.1    80.5    79.7    80.4    78.9    76.9    77.1      78    76.4    77.9
    75.5    75.5    74.3      75    71.2   72.64      72   82.22   82.36   82.08
   74.55   77.19   76.15   76.95   78.07   75.59   77.32   76.58   76.57   74.86
   75.86   75.52   76.12   75.61   76.88   75.23   75.36   73.68    74.4   74.48
   73.41   74.16   73.29   73.45   76.03   77.15   79.87    79.8   77.03   75.66
   76.46   78.02   77.72   78.26   77.51   77.59   76.71   76.88   77.53      83
  2866.7  2866.8  2926.8  3016.8  3130.1    3845  3981.8  4061.8  4121.8  4186.7
  4386.7  4466.7  4566.9  4636.9  4846.9  4858.2 4890.81  4890.9  4949.1 5102.29
  5102.4    5131    5281    5391    5431  5513.8  5603.8  5683.8  6033.9  6223.9
  6313.9  6464.8  6494.8  6864.8  7000.3  7090.3  7280.3  7790.3  7830.3  8090.3
  8160.3  8220.3  8260.3  8390.3  8440.3 8870.03  8870.1 9030.99  9031.1  9670.3
 10060.3 10110.3 10240.3 10270.3 10720.3 11320.3 11510.3 11840.3 11854.7   12000
    84.1    84.1    84.1    84.1    84.1   84.12   84.12   84.12   84.12   84.12
   84.13   84.13   84.13   84.14   84.71   84.74   84.82   84.82   84.96   84.68
   84.68   84.57   84.08   83.94   83.92   83.88   83.85   83.81   83.66   83.58
   83.55   83.48   83.47   83.31   83.26   83.22   83.14   82.92   82.91    82.8
   82.77   82.74   82.73   82.67   82.65   82.47   82.47    82.4    82.4   82.13
   81.97   81.95   81.89   81.88   81.69   81.44   81.36   81.22   81.21      83
    83.8    80.2    79.4    80.1    78.6    76.6    76.8    77.7    76.1    77.6
    75.2    75.2      74    74.7    70.9   72.34    71.7   81.92   82.06   81.78
   74.25   76.89   75.85   76.65   77.77   75.29   77.02   76.28   76.27   74.56
   75.56   75.22   75.82   75.31   76.58   74.93   75.06   73.38    74.1   74.18
   73.11   73.86   72.99   73.15   75.73   76.85   79.57    79.5   76.73   75.36
   76.16   77.72   77.42   77.96   77.21   77.29   76.41   76.58   77.23    82.7
Pier Skew, UpSta & Num, DnSta & Num=  ,4917.7, 2 ,4917.7, 2 , 0 , 0 , 0 ,,
       2       2
   70.07   83.28
       2       2
   69.77   82.98
Pier Skew, UpSta & Num, DnSta & Num=  ,4939.5, 2 ,4939.5, 2 , 0 , 0 , 0 ,,
       2       2
   61.41   83.34
       2       2
   61.11   83.04
Pier Skew, UpSta & Num, DnSta & Num=  ,4968.4, 2 ,4968.4, 2 , 0 , 0 , 0 ,,
       6       6
   58.87   83.34
       6       6
   58.57   83.04
Pier Skew, UpSta & Num, DnSta & Num=  ,5046.2, 2 ,5046.2, 2 , 0 , 0 , 0 ,,
       6       6
   62.88   83.27
       6       6
   62.58   82.97
Pier Skew, UpSta & Num, DnSta & Num=  ,5074.2, 2 ,5074.2, 2 , 0 , 0 , 0 ,,
       2       2
   68.21   83.18
       2       2
   67.91   82.88
BR Coef= 1 , 1 , 0 ,1.25, 0 ,,,0.8,0,2,0,
WSPro=,,,, 1 ,,,, 0 ,,,, 0 ,,,,-1 ,-1 ,-1 , 0 , 0 , 0 , 0 , 0
BR Coef= 1 , 1 , 0 ,1.25, 0 ,,,0.8,0,2,0,
WSPro=,,,, 1 ,,,, 0 ,,,, 0 ,,,,-1 ,-1 ,-1 , 0 , 0 , 0 , 0 , 0
BC Mult= 3 ,1866.7,7614.2,1866.7,7614.2
BC Mult= 3 ,6358.3,13000,6358.3,13000
BR U #Sta/Elev= 125
  2866.7    84.1  2866.8    80.5  2926.8    79.7  3016.8    80.4  3095.5   79.36
  3130.1    78.9    3565    77.8    3775    77.1    3845    76.9  3981.8    77.1
  4058.6   77.96  4061.8      78  4121.8    76.4  4186.7    77.9  4386.7    75.5
  4466.7    75.5  4566.9    74.3  4631.9   74.95  4636.9      75  4713.4   73.79
  4756.9    73.1  4781.6   72.58  4846.9    71.2  4858.2   72.64  4858.3   72.64
 4890.81      72  4890.9      72    4891      72  4917.7   71.48  4939.5   62.49
  4949.1   61.69  4968.4   60.09  4976.5   59.49    4983   57.97  4998.1   57.09
  5013.8   58.38  5023.5   59.54  5046.2   64.54  5053.5   65.18  5063.1   66.02
  5074.2   69.53  5093.1   72.77  5102.2   74.52 5102.29   74.53  5102.4   74.55
  5103.1   74.69  5105.4   75.13    5131   77.19  5158.3      77  5238.9   76.44
    5281   76.15  5332.7   76.53    5391   76.95    5431   78.07  5453.8    77.5
  5513.8   75.59  5603.8   77.32  5683.8   76.58  5963.9   76.66  6033.9   76.57
  6193.9   75.05  6223.9   74.86  6293.9   75.26  6313.9   75.86  6364.8   75.68
  6444.8   75.71  6464.8   75.52  6494.8   76.12  6564.8   76.12  6614.8   76.09
  6634.8   75.92  6734.8   76.03  6764.8   76.02  6864.8   75.61  6904.8   76.42
  6950.3   76.84  7000.3   76.88  7060.3    75.4  7090.3   75.23  7120.3   75.25
  7170.3   75.35  7210.3   75.24  7260.3   74.94  7280.3   75.36  7790.3   73.68
  7830.3    74.4  7920.3    74.6  8090.3   74.48  8160.3   73.41  8220.3   74.16
  8260.3   73.29  8390.3   73.45  8440.3   76.03  8710.3   77.05  8769.3   77.23
  8770.3   77.23 8869.91   77.15 8870.03   77.15  8870.1   77.15 9030.87   77.03
 9030.99   77.03  9031.1   77.03  9100.3   76.98  9130.3   77.15  9670.3   75.66
 10060.3   76.46 10110.3   78.02 10190.3   77.82 10220.3   78.09 10240.3   77.72
 10270.3   78.26 10280.3   78.15 10670.3   77.56 10720.3   77.51 10950.3   77.43
 10960.3   77.72 11320.3   77.59 11330.3   77.32 11510.3   76.71 11530.3   77.11
 11840.3   76.88 11854.7   77.53 11868.7   78.16 11999.9      83   12000      83
BR U #Mann= 8
  2866.7      .1  3095.5     .12  4058.6      .1  4858.2    .032  5105.4      .1
  8769.3     .08  9130.3      .1 11854.7      .2
BR U Banks=4858.2,5105.4
BR D #Sta/Elev= 125
  2866.7    83.8  2866.8    80.2  2926.8    79.4  3016.8    80.1  3095.5   79.06
  3130.1    78.6    3565    77.5    3775    76.8    3845    76.6  3981.8    76.8
  4058.6   77.66  4061.8    77.7  4121.8    76.1  4186.7    77.6  4386.7    75.2
  4466.7    75.2  4566.9      74  4631.9   74.65  4636.9    74.7  4713.4   73.49
  4756.9    72.8  4781.6   72.28  4846.9    70.9  4858.2   72.34  4858.3   72.34
 4890.81    71.7  4890.9    71.7    4891    71.7  4917.7   71.18  4939.5   62.19
  4949.1   61.39  4968.4   59.79  4976.5   59.19    4983   57.67  4998.1   56.79
  5013.8   58.08  5023.5   59.24  5046.2   64.24  5053.5   64.88  5063.1   65.72
  5074.2   69.23  5093.1   72.47  5102.2   74.22 5102.29   74.23  5102.4   74.25
  5103.1   74.39  5105.4   74.83    5131   76.89  5158.3    76.7  5238.9   76.14
    5281   75.85  5332.7   76.23    5391   76.65    5431   77.77  5453.8    77.2
  5513.8   75.29  5603.8   77.02  5683.8   76.28  5963.9   76.36  6033.9   76.27
  6193.9   74.75  6223.9   74.56  6293.9   74.96  6313.9   75.56  6364.8   75.38
  6444.8   75.41  6464.8   75.22  6494.8   75.82  6564.8   75.82  6614.8   75.79
  6634.8   75.62  6734.8   75.73  6764.8   75.72  6864.8   75.31  6904.8   76.12
  6950.3   76.54  7000.3   76.58  7060.3    75.1  7090.3   74.93  7120.3   74.95
  7170.3   75.05  7210.3   74.94  7260.3   74.64  7280.3   75.06  7790.3   73.38
  7830.3    74.1  7920.3    74.3  8090.3   74.18  8160.3   73.11  8220.3   73.86
  8260.3   72.99  8390.3   73.15  8440.3   75.73  8710.3   76.75  8769.3   76.93
  8770.3   76.93 8869.91   76.85 8870.03   76.85  8870.1   76.85 9030.87   76.73
 9030.99   76.73  9031.1   76.73  9100.3   76.68  9130.3   76.85  9670.3   75.36
 10060.3   76.16 10110.3   77.72 10190.3   77.52 10220.3   77.79 10240.3   77.42
 10270.3   77.96 10280.3   77.85 10670.3   77.26 10720.3   77.21 10950.3   77.13
 10960.3   77.42 11320.3   77.29 11330.3   77.02 11510.3   76.41 11530.3   76.81
 11840.3   76.58 11854.7   77.23 11868.7   77.86 11999.9    82.7   12000    82.7
BR D #Mann= 8
  2866.7      .1  3095.5     .12  4058.6      .1  4858.2    .032  5105.4      .1
  8769.3     .08  9130.3      .1 11854.7      .2
BR D Banks=4858.2,5105.4
BC Design=,, 0 ,, 0 ,,,,,,
BC HTab HWMax=84.13
BC Use User HTab Curves=0
BC User HTab FreeFlow(D)= 0

Type RM Length L Ch R = 1 ,155332.8,20.4,20.4,20.4
BEGIN DESCRIPTION:
Downstream Section of Bridge/Culvert/Weir
END DESCRIPTION:
XS GIS Cut Line= 6
      3112820.53     13912516.86      3113004.06      13911803.1
      3113259.68     13910757.92      3113701.65     13908993.65
      3114575.01     13905455.57      3115036.34     13903656.54
#Sta/Elev= 30
  2866.7   83.77  2866.8   80.17  3095.5   79.03    3845   76.57  4058.6   77.63
  4636.9   74.67  4846.9   70.87  4858.2   72.31  4917.7   71.15  4939.5   62.16
  4998.1   56.76  5063.1   65.69  5105.4    74.8    5131   76.86    5281   75.82
    5431   77.74  5513.8   75.26  5603.8   76.99  6223.9   74.53  7000.3   76.55
  7090.3    74.9  8260.3   72.96  8390.3   73.12  8440.3    75.7  8769.3    76.9
  9130.3   76.82  9670.3   75.33 10270.3   77.93 11854.7    77.2   12000   82.67
#Mann= 8 , 1 , 0
  2866.7      .1       0  3095.5     .12       0  4058.6      .1       0
  4858.2    .032       0  5105.4      .1       0  8769.3     .08       0
  9130.3      .1       0 11854.7      .2       0
#XS Ineff= 3 ,-1
    2866    4881    83.9    5113    8840    84.1    9041   12000    83.6
Permanent Ineff=
       F       F       F
Bank Sta=4858.2,5105.4
XS Rating Curve= 0 ,0
Exp/Cntr=0.5,0.3

Type RM Length L Ch R = 1 ,155312.4,57,57,57
BEGIN DESCRIPTION:
Upstream Section of Bridge/Culvert/Weir
END DESCRIPTION:
XS GIS Cut Line= 6
      3113884.52     13912778.78      3113501.07     13912042.43
      3113341.24     13911638.64      3113261.32     13911184.39
      3113265.61     13910847.88      3115045.39     13903781.48
#Sta/Elev= 30
  2526.8   81.73  3056.7   79.94    3152    79.1  4131.8   76.33  4206.7   77.73
  4396.7   74.73  4656.9   75.43  4657.1   78.35    4816   78.73  4913.7   73.57
    4968    62.5  4973.6   58.06  5017.2   56.69  5077.5   75.78  5115.4   78.86
    5431    78.1  5513.8   75.62  5603.8   77.35  6223.9   74.89  7000.3   76.91
  8260.3   73.32  8440.3   76.06  8769.3   76.96  8790.3   73.45  9090.3   74.35
  9100.3   76.61  9129.3   77.16 11840.3   76.91   11872   79.96 11876.8   82.53
#Mann= 8 , 1 , 0
  2526.8      .1       0  3056.7     .12       0    3152      .1       0
    4816    .032       0  5077.5      .1       0  8769.3     .08       0
  9129.3      .1       0   11872      .2       0
#XS Ineff= 3 ,-1
    2510    4831      84    5125    8898    83.2    9000   11877    83.6
Permanent Ineff=
       F       F       F
Bank Sta=4816,5077.5
XS Rating Curve= 0 ,0
Exp/Cntr=0.5,0.3

Type RM Length L Ch R = 3 ,155283.9,,,
BEGIN DESCRIPTION:
HARDY TOLLWAY FEEDER
Structure ID: P00-46
END DESCRIPTION:
Bridge Culvert--1,0,-1,-1, 0
Deck Dist Width WeirC Skew NumUp NumDn MinLoCord MaxHiCord MaxSubmerge Is_Ogee
10,37,2.6,0, 60, 60, , , 0.95, 0, 1,1,,
  2526.8  2576.8  2836.8  3160.1    3585    3795  4081.8  4131.8  4206.7  4396.7
  4656.9  4657.1  4689.1    4816 4855.11 4899.29  4899.4  4968.1 5084.69  5084.8
  5115.4  5236.9 5237.01  5332.3    5391    5431  5513.8  5603.8  5683.8  6033.9
  6223.9  6313.9  6464.8  6494.8  6864.8  7000.3  7090.3  7280.3  7790.3  7830.3
  8090.3  8160.3  8220.3  8260.3  8390.3  8443.2  8770.3  8790.3  9090.3  9100.3
  9130.3  9433.2  9670.3 10060.3 10110.3 10240.3 10270.3 11840.3 11868.7 11876.8
    81.7    80.6    80.9      79   78.11   78.52   78.14   78.07   78.04   78.08
   78.14   78.33   78.62   79.07   78.98      79    82.4   82.56   82.37   82.37
   82.13   81.44   78.04   77.47   77.47   78.08   77.48   77.48   77.49    77.5
   77.51   77.52   77.53   77.53   77.55   77.55   77.56   77.57   77.59   77.59
   76.94    76.8   76.68   76.59   76.33   76.22   76.94   76.69   76.67   76.67
   77.16   76.65   77.58    77.4   78.03   77.73   78.27   76.88   78.16    82.5
    81.7    80.6    80.9      79    78.1      77    77.2    76.3    77.7    74.7
    75.4   78.32   78.61    78.7   76.63    76.9    76.9   77.06   76.87   76.34
   78.83   77.86   77.86   77.46   76.95   78.07   75.59   77.32   76.58   76.57
   74.86   75.86   75.52   76.12   75.61   76.88   75.23   75.36   73.68    74.4
   74.48   73.41   74.16   73.29   73.45   76.04   76.93   73.42   74.32   76.58
   77.15   76.31   75.66   76.46   78.02   77.72   78.26   76.88   78.16    82.5
  2526.8  2576.8  2836.8  3160.1    3585    3795  4081.8  4131.8  4206.7  4396.7
  4656.9  4657.1  4689.1    4816 4855.11 4899.29  4899.4  4968.1 5084.69  5084.8
  5115.4  5236.9 5237.01  5332.3    5391    5431  5513.8  5603.8  5683.8  6033.9
  6223.9  6313.9  6464.8  6494.8  6864.8  7000.3  7090.3  7280.3  7790.3  7830.3
  8090.3  8160.3  8220.3  8260.3  8390.3  8443.2  8770.3  8790.3  9090.3  9100.3
  9130.3  9433.2  9670.3 10060.3 10110.3 10240.3 10270.3 11840.3 11868.7 11876.8
    81.7    80.6    80.9      79   78.11   78.52   78.14   78.07   78.04   78.08
   78.14   78.33   78.62   79.07   78.98      79    82.4   82.56   82.37   82.37
   82.13   81.44   78.04   77.47   77.47   78.08   77.48   77.48   77.49    77.5
   77.51   77.52   77.53   77.53   77.55   77.55   77.56   77.57   77.59   77.59
   76.94    76.8   76.68   76.59   76.33   76.22   76.94   76.69   76.67   76.67
   77.16   76.65   77.58    77.4   78.03   77.73   78.27   76.88   78.16    82.5
   81.55   80.45   80.75   78.85   77.95   76.85   77.05   76.15   77.55   74.55
   75.25   78.17   78.46   78.55   76.48   76.75   76.75   76.91   76.72   76.19
   78.68   77.71   77.71   77.31    76.8   77.92   75.44   77.17   76.43   76.42
   74.71   75.71   75.37   75.97   75.46   76.73   75.08   75.21   73.53   74.25
   74.33   73.26   74.01   73.14    73.3   75.89   76.78   73.27   74.17   76.43
      77   76.16   75.51   76.31   77.87   77.57   78.11   76.73   78.01   82.35
Pier Skew, UpSta & Num, DnSta & Num=  ,5023.5, 2 ,5023.5, 2 , 0 , 0 , 0 ,,
     1.4     1.4
   57.36   77.97
     1.4     1.4
   57.21   77.82
Abutment Skew #Up #Dn= , 2 , 2
    4855  4968.1
   76.88   62.39
    4855  4968.1
   76.73   62.24
Abutment Skew #Up #Dn= , 2 , 2
    5035 5084.89
   63.63   76.87
    5035 5084.89
   63.48   76.72
BR Coef= 1 , 1 , 0 ,1.25, 0 ,,,0.8,0,2,0,
WSPro=,,,, 1 ,,,, 0 ,,,, 0 ,,,,-1 ,-1 ,-1 , 0 , 0 , 0 , 0 , 0
BR U #Sta/Elev= 153
  2526.8    81.7  2576.8    80.6  2726.8    80.7  2836.8    80.9  2956.8    80.2
  3046.8      80  3056.7   79.91    3152   79.07  3160.1      79    3577   78.12
    3585    78.1  3791.3   77.02    3795      77    3905    77.5  4001.8    77.2
  4081.8    77.2  4131.8    76.3  4163.9    76.9  4206.7    77.7  4396.7    74.7
  4476.7      75  4586.9    75.2  4656.9    75.4  4657.1   78.32  4657.9   78.15
    4658   78.13  4689.1   78.61    4734   78.41  4736.9    78.4  4771.5   78.84
  4810.4   78.72    4816    78.7    4855   76.64 4855.11   76.63  4855.2   76.63
 4899.29    74.3  4899.4    74.3 4899.51   74.29  4905.2   73.99  4913.7   73.54
  4935.4   67.97  4948.8   65.16  4965.7   62.79    4968   62.47  4968.1   62.39
  4973.6   58.03  4990.7   57.44  5004.8   57.18  5017.2   56.66  5023.5   58.57
  5025.2   58.44  5026.4   58.34  5034.9   63.57    5035   63.63    5051   67.57
  5063.8   70.82  5077.5   75.75 5084.69   76.33  5084.8   76.34  5084.9   76.35
  5115.4   78.83  5145.2   78.55  5145.5   78.55  5174.7   78.22  5207.4   78.27
  5208.3   78.27 5236.79   77.86  5236.9   77.86 5237.01   77.86  5244.1   77.76
  5283.1   77.54  5332.3   77.46  5332.4   77.46    5391   76.95    5431   78.07
  5453.8    77.5  5513.8   75.59  5603.8   77.32  5683.8   76.58  5963.9   76.66
  6033.9   76.57  6193.9   75.05  6223.9   74.86  6293.9   75.26  6313.9   75.86
  6364.8   75.68  6444.8   75.71  6464.8   75.52  6494.8   76.12  6564.8   76.12
  6614.8   76.09  6634.8   75.92  6734.8   76.03  6764.8   76.02  6864.8   75.61
  6904.8   76.42  6950.3   76.84  7000.3   76.88  7060.3    75.4  7090.3   75.23
  7120.3   75.25  7170.3   75.35  7210.3   75.24  7260.3   74.94  7280.3   75.36
  7790.3   73.68  7830.3    74.4  7920.3    74.6  7953.2   74.58  8013.2   74.53
  8090.3   74.48  8160.3   73.41  8220.3   74.16  8260.3   73.29  8390.3   73.45
  8440.3   76.03  8443.2   76.04  8452.3   76.08  8652.3   76.83  8710.3   77.05
  8769.3   76.93  8770.3   76.93  8790.3   73.42  9090.3   74.32  9100.3   76.58
  9129.3   77.13  9130.3   77.15  9433.2   76.31  9593.2   75.87  9670.3   75.66
 10043.2   76.42 10060.3   76.46 10073.2   76.86 10110.3   78.02 10190.3   77.82
 10220.3   78.09 10240.3   77.72 10270.3   78.26 10280.3   78.15 10670.3   77.56
 10720.3   77.51 10813.2   77.48 10950.3   77.43 10960.3   77.72 11320.3   77.59
 11330.3   77.32 11510.3   76.71 11530.3   77.11 11723.2   76.97 11840.3   76.88
 11868.7   78.16   11872   79.93 11876.8    82.5
BR U #Mann= 8
  2526.8      .1  3056.7     .12    3152      .1    4816    .032  5077.5      .1
  8769.3     .08  9129.3      .1   11872      .2
BR U Banks=4816,5077.5
BR D #Sta/Elev= 153
  2526.8   81.55  2576.8   80.45  2726.8   80.55  2836.8   80.75  2956.8   80.05
  3046.8   79.85  3056.7   79.76    3152   78.92  3160.1   78.85    3577   77.97
    3585   77.95  3791.3   76.87    3795   76.85    3905   77.35  4001.8   77.05
  4081.8   77.05  4131.8   76.15  4163.9   76.75  4206.7   77.55  4396.7   74.55
  4476.7   74.85  4586.9   75.05  4656.9   75.25  4657.1   78.17  4657.9      78
    4658   77.98  4689.1   78.46    4734   78.26  4736.9   78.25  4771.5   78.69
  4810.4   78.57    4816   78.55    4855   76.49 4855.11   76.48  4855.2   76.48
 4899.29   74.15  4899.4   74.15 4899.51   74.14  4905.2   73.84  4913.7   73.39
  4935.4   67.82  4948.8   65.01  4965.7   62.64    4968   62.32  4968.1   62.24
  4973.6   57.88  4990.7   57.29  5004.8   57.03  5017.2   56.51  5023.5   58.42
  5025.2   58.29  5026.4   58.19  5034.9   63.42    5035   63.48    5051   67.42
  5063.8   70.67  5077.5    75.6 5084.69   76.18  5084.8   76.19  5084.9    76.2
  5115.4   78.68  5145.2    78.4  5145.5    78.4  5174.7   78.07  5207.4   78.12
  5208.3   78.12 5236.79   77.71  5236.9   77.71 5237.01   77.71  5244.1   77.61
  5283.1   77.39  5332.3   77.31  5332.4   77.31    5391    76.8    5431   77.92
  5453.8   77.35  5513.8   75.44  5603.8   77.17  5683.8   76.43  5963.9   76.51
  6033.9   76.42  6193.9    74.9  6223.9   74.71  6293.9   75.11  6313.9   75.71
  6364.8   75.53  6444.8   75.56  6464.8   75.37  6494.8   75.97  6564.8   75.97
  6614.8   75.94  6634.8   75.77  6734.8   75.88  6764.8   75.87  6864.8   75.46
  6904.8   76.27  6950.3   76.69  7000.3   76.73  7060.3   75.25  7090.3   75.08
  7120.3    75.1  7170.3    75.2  7210.3   75.09  7260.3   74.79  7280.3   75.21
  7790.3   73.53  7830.3   74.25  7920.3   74.45  7953.2   74.43  8013.2   74.38
  8090.3   74.33  8160.3   73.26  8220.3   74.01  8260.3   73.14  8390.3    73.3
  8440.3   75.88  8443.2   75.89  8452.3   75.93  8652.3   76.68  8710.3    76.9
  8769.3   76.78  8770.3   76.78  8790.3   73.27  9090.3   74.17  9100.3   76.43
  9129.3   76.98  9130.3      77  9433.2   76.16  9593.2   75.72  9670.3   75.51
 10043.2   76.27 10060.3   76.31 10073.2   76.71 10110.3   77.87 10190.3   77.67
 10220.3   77.94 10240.3   77.57 10270.3   78.11 10280.3      78 10670.3   77.41
 10720.3   77.36 10813.2   77.33 10950.3   77.28 10960.3   77.57 11320.3   77.44
 11330.3   77.17 11510.3   76.56 11530.3   76.96 11723.2   76.82 11840.3   76.73
 11868.7   78.01   11872   79.78 11876.8   82.35
BR D #Mann= 8
  2526.8      .1  3056.7     .12    3152      .1    4816    .032  5077.5      .1
  8769.3     .08  9129.3      .1   11872      .2
BR D Banks=4816,5077.5
BC Design=,, 0 ,, 0 ,,,,,,
BC HTab HWMax=82.53
BC Use User HTab Curves=0
BC User HTab FreeFlow(D)= 0

Type RM Length L Ch R = 1 ,155255.4,6.5,6.5,6.5
BEGIN DESCRIPTION:
Downstream Section of Bridge/Culvert/Weir
END DESCRIPTION:
XS GIS Cut Line= 6
      3113941.52     13912778.78      3113558.07     13912042.43
      3113398.24     13911638.64      3113318.32     13911184.39
      3113322.61     13910847.88      3115102.39     13903781.48
#Sta/Elev= 30
  2526.8   81.57  3056.7   79.78    3152   78.94  4131.8   76.17  4206.7   77.57
  4396.7   74.57  4656.9   75.27  4657.1   78.19    4816   78.57  4913.7   73.41
    4968   62.34  4973.6    57.9  5017.2   56.53  5077.5   75.62  5115.4    78.7
    5431   77.94  5513.8   75.46  5603.8   77.19  6223.9   74.73  7000.3   76.75
  8260.3   73.16  8440.3    75.9  8769.3    76.8  8790.3   73.29  9090.3   74.19
  9100.3   76.45  9129.3      77 11840.3   76.75   11872    79.8 11876.8   82.37
#Mann= 8 , 1 , 0
  2526.8      .1       0  3056.7     .12       0    3152      .1       0
    4816    .032       0  5077.5      .1       0  8769.3     .08       0
  9129.3      .1       0   11872      .2       0
#XS Ineff= 3 ,-1
    2510    4831    83.8    5125    8898      83    9000   11877    83.4
Permanent Ineff=
       F       F       F
Bank Sta=4816,5077.5
XS Rating Curve= 0 ,0
Exp/Cntr=0.5,0.3

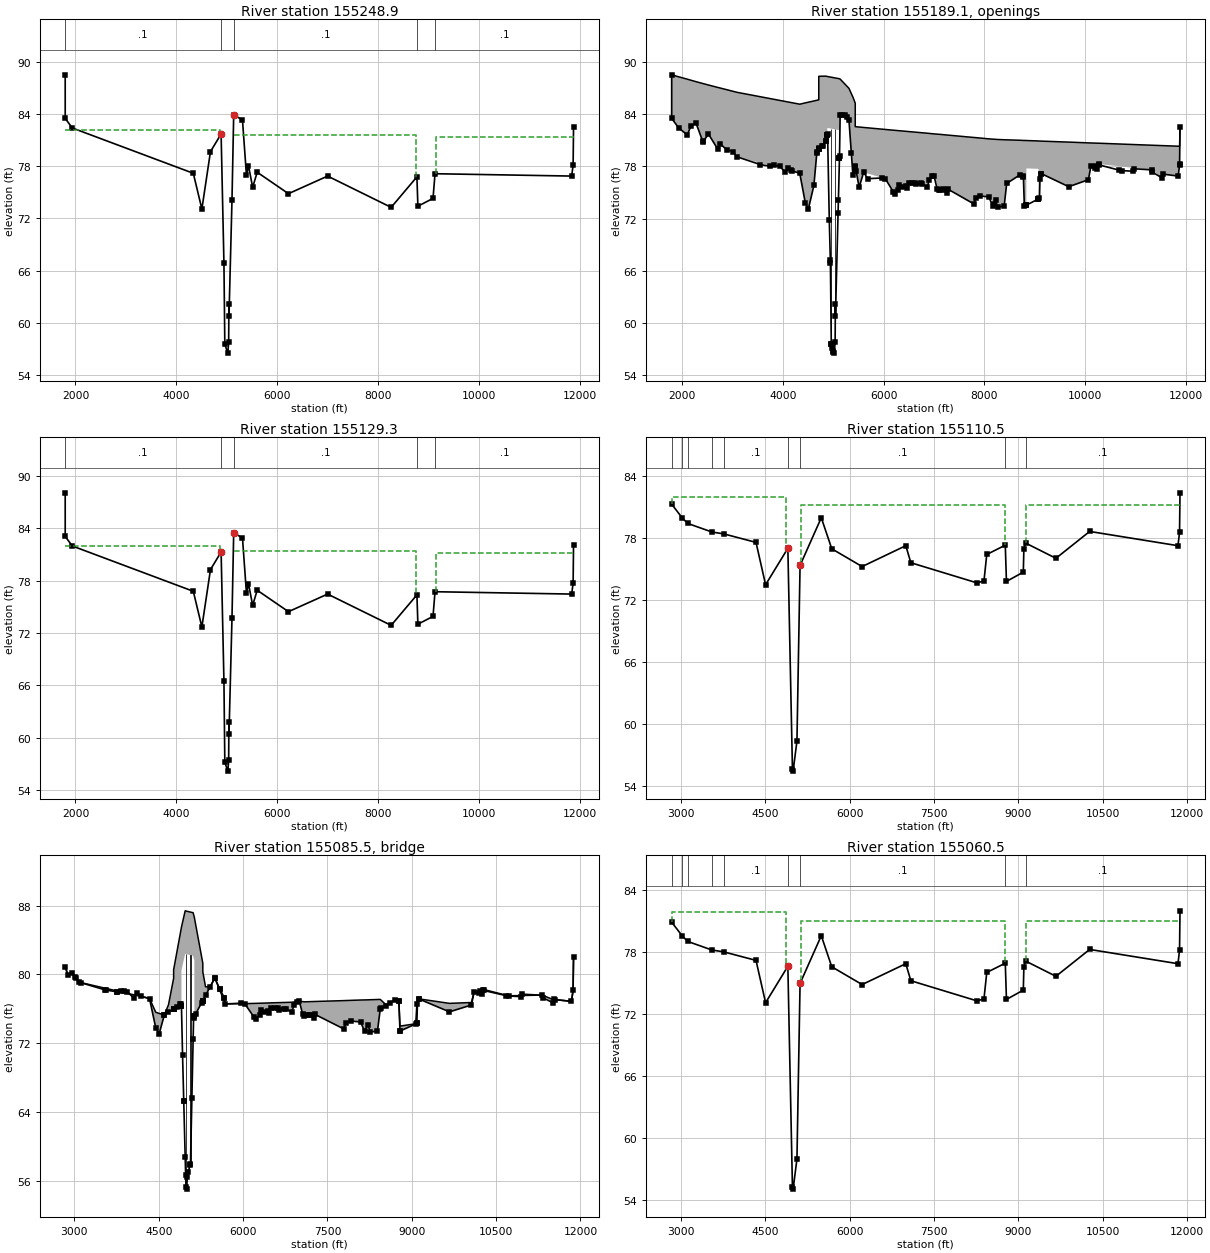
Type RM Length L Ch R = 1 ,155248.9,119.6,119.6,119.6
BEGIN DESCRIPTION:
Upstream Section of Bridge/Culvert/Weir
END DESCRIPTION:
XS GIS Cut Line= 6
      3114463.28     13913319.49      3113600.23     13912053.63
      3113419.37     13911696.11      3113343.66     13911393.27
      3113337.11     13910812.45      3115100.44     13903779.45
#Sta/Elev= 30
  1796.7   88.48  1796.8   83.48  1936.8   82.38  4336.7   77.18  4506.9   73.08
  4677.3   79.67  4888.3   81.69  4944.3   66.88  4961.8   57.57  5020.9   56.54
  5038.1   57.76  5042.6   62.22  5044.5   60.78  5103.9    74.1  5137.8   83.89
  5312.1   83.29    5391   76.93    5431   78.05  5513.8   75.57  5603.8    77.3
  6223.9   74.84  7000.3   76.86  8260.3   73.27  8771.1   76.77  8790.3    73.4
  9090.3    74.3  9130.1   77.13 11840.3   76.86 11868.7   78.14 11876.8   82.48
#Mann= 5 , 1 , 0
  1796.7      .1       0  4888.3    .032       0  5137.8      .1       0
  8771.1     .06       0  9130.1      .1       0
#XS Ineff= 3 ,-1
    1800    4873    82.2    5144    8760    81.6    9141   12900    81.4
Permanent Ineff=
       F       F       F
Bank Sta=4888.3,5137.8
XS Rating Curve= 0 ,0
Exp/Cntr=0.5,0.3

Type RM Length L Ch R = 4 ,155189.1,,,
BEGIN DESCRIPTION:
HARDY TOLL ROAD
Structure ID: P00-45
END DESCRIPTION:
Bridge Culvert--1,0,-1,-1, 0
Deck Dist Width WeirC Skew NumUp NumDn MinLoCord MaxHiCord MaxSubmerge Is_Ogee
10,99.6,2.6,0, 60, 60, , , 0.95, 0, 1,1,,
  1796.7  1796.8  1936.8  2106.8  2276.8  2416.8  2526.8  2706.8  2756.8  3086.8
  4336.7  4446.7  4506.9  4616.9  4677.3 4713.69  4713.8  4847.4 4883.71  4883.8
 5124.09  5124.2  5137.8  5312.1    5391    5437 5437.11  5513.8  5603.8  6033.9
  6223.9  6494.8  6864.8  7000.3  7090.3  7790.3  7830.3  8090.3  8260.3  8390.3
  8440.3  8710.3  8770.3  8790.3 8830.23  8830.3 9070.19  9070.3  9090.3  9100.3
  9130.1  9670.3 10060.3 10110.3 10270.3 11320.3 11510.3 11840.3 11868.7 11876.8
    88.5    88.5   88.27      88   87.72    87.5   87.33   87.06   86.99    86.5
   85.13   85.28   85.36    85.5   85.58   85.63   88.33   88.35   88.31   88.31
   88.05   88.05   88.01   86.95   85.94   85.25   82.55   82.51   82.46   82.23
   82.13   81.99    81.8   81.72   81.68   81.31   81.29   81.15   81.08   81.05
   81.04   80.99   80.97   80.97   80.96   80.96   80.91   80.91    80.9    80.9
   80.89   80.78   80.69   80.68   80.65   80.42   80.38   80.31    80.3    82.5
    88.5    83.5    82.4    81.6      83    80.8    81.7      80    80.6    79.1
    77.2    73.8    73.1    75.8   79.69   80.02   80.02   80.91   81.62   82.41
   82.15   78.99   83.91   83.31   76.95   77.92   77.92   75.59   77.32   76.57
   74.86   76.12   75.61   76.88   75.23   73.68    74.4   74.48   73.29   73.45
   76.03   77.05   76.93   73.42   73.54   77.76   77.71   74.26   74.32   76.58
   77.15   75.66   76.46   78.02   78.26   77.59   76.71   76.88   78.16    82.5
  1796.7  1796.8  1936.8  2106.8  2276.8  2416.8  2526.8  2706.8  2756.8  3086.8
  4336.7  4446.7  4506.9  4616.9  4677.3 4713.69  4713.8  4847.4 4883.71  4883.8
 5124.09  5124.2  5137.8  5312.1    5391    5437 5437.11  5513.8  5603.8  6033.9
  6223.9  6494.8  6864.8  7000.3  7090.3  7790.3  7830.3  8090.3  8260.3  8390.3
  8440.3  8710.3  8770.3  8790.3 8830.23  8830.3 9070.19  9070.3  9090.3  9100.3
  9130.1  9670.3 10060.3 10110.3 10270.3 11320.3 11510.3 11840.3 11868.7 11876.8
    88.5    88.5   88.27      88   87.72    87.5   87.33   87.06   86.99    86.5
   85.13   85.28   85.36    85.5   85.58   85.63   88.33   88.35   88.31   88.31
   88.05   88.05   88.01   86.95   85.94   85.25   82.55   82.51   82.46   82.23
   82.13   81.99    81.8   81.72   81.68   81.31   81.29   81.15   81.08   81.05
   81.04   80.99   80.97   80.97   80.96   80.96   80.91   80.91    80.9    80.9
   80.89   80.78   80.69   80.68   80.65   80.42   80.38   80.31    80.3    82.5
   88.48   83.48   82.38   81.58   82.98   80.78   81.68   79.98   80.58   79.08
   77.18   73.78   73.08   75.78   79.67      80      80   80.89    81.6   82.39
   82.13   78.97   83.89   83.29   76.93    77.9    77.9   75.57    77.3   76.55
   74.84    76.1   75.59   76.86   75.21   73.66   74.38   74.46   73.27   73.43
   76.01   77.03   76.91    73.4   73.52   77.74   77.69   74.24    74.3   76.56
   77.13   75.64   76.44      78   78.24   77.57   76.69   76.86   78.14   82.48
Pier Skew, UpSta & Num, DnSta & Num=  ,4964.2, 2 ,4964.2, 2 , 0 , 0 , 0 ,,
     1.3     1.3
   56.56   83.34
     1.3     1.3
   56.54   83.32
Pier Skew, UpSta & Num, DnSta & Num=  ,5044.5, 2 ,5044.5, 2 , 0 , 0 , 0 ,,
     1.3     1.3
   59.95   83.28
     1.3     1.3
   59.93   83.26
BR Coef= 1 , 1 , 0 ,1.25, 0 ,,,0.8,0,2,0,
WSPro=,,,, 1 ,,,, 0 ,,,, 0 ,,,,-1 ,-1 ,-1 , 0 , 0 , 0 , 0 , 0
BR Coef= 1 , 1 , 0 ,1.25, 0 ,,,0.8,0,2,0,
WSPro=,,,, 1 ,,,, 0 ,,,, 0 ,,,,-1 ,-1 ,-1 , 0 , 0 , 0 , 0 , 0
BC Mult= 3 ,796.7,7594.93,796.7,7594.93
BC Mult= 3 ,6359.57,12876.8,6359.57,12876.8
BR U #Sta/Elev= 144
  1796.7    88.5  1796.8    83.5  1936.8    82.4  2106.8    81.6  2176.8    82.6
  2276.8      83  2413.7   80.85  2416.8    80.8  2526.8    81.7  2706.8      80
  2756.8    80.6  2886.8    79.9  3006.8    79.7  3086.8    79.1    3555    78.2
    3755      78    3825    78.1  3941.8      78  4051.8    77.3  4111.8    77.8
  4163.4   77.56  4176.7    77.5  4336.7    77.2  4446.7    73.8  4506.9    73.1
  4616.9    75.8  4675.9   79.57  4677.3   79.69 4713.69   80.02  4713.8   80.02
 4713.91   80.02  4724.3   80.11    4781   80.31  4788.3   80.38  4847.4   80.91
  4848.8   80.94 4883.71   81.62  4883.8   81.62  4883.9   81.62  4888.3   81.71
  4922.3   71.83  4942.6   67.28  4944.3    66.9  4961.8   57.59  4964.2   57.58
  4978.6   57.13  4994.8   56.86  5005.3   56.68  5020.9   56.56  5038.1   57.78
  5042.6   62.24  5044.5    60.8  5097.4   72.66  5103.9   74.12    5124   78.94
 5124.09   78.96  5124.2   78.99    5125   79.18  5137.8   83.91  5182.5    83.9
  5236.5   83.88  5272.5   83.61  5312.1   83.31  5359.5   79.49    5391   76.95
    5431   78.07 5436.89   77.92    5437   77.92 5437.11   77.92  5437.5   77.91
  5453.8    77.5  5513.8   75.59  5603.8   77.32  5683.8   76.58  5963.9   76.66
  6033.9   76.57  6193.9   75.05  6223.9   74.86  6293.9   75.26  6313.9   75.86
  6364.8   75.68  6444.8   75.71  6464.8   75.52  6494.8   76.12  6564.8   76.12
  6614.8   76.09  6634.8   75.92  6734.8   76.03  6764.8   76.02  6864.8   75.61
  6904.8   76.42  6950.3   76.84  7000.3   76.88  7060.3    75.4  7090.3   75.23
  7120.3   75.25  7170.3   75.35  7210.3   75.24  7260.3   74.94  7280.3   75.36
  7790.3   73.68  7830.3    74.4  7920.3    74.6  8090.3   74.48  8160.3   73.41
  8180.6   73.66  8220.3   74.16  8260.3   73.29  8390.3   73.45  8440.3   76.03
  8710.3   77.05  8770.3   76.93  8771.1   76.79  8790.3   73.42 8830.11   73.54
 8830.23   73.54  8830.3   73.54 9070.07   74.26 9070.19   74.26  9070.3   74.26
  9090.3   74.32  9100.3   76.58  9130.1   77.15  9130.3   77.15  9670.3   75.66
 10060.3   76.46 10110.3   78.02 10190.3   77.82 10220.3   78.09 10240.3   77.72
 10270.3   78.26 10280.3   78.15 10670.3   77.56 10720.3   77.51 10950.3   77.43
 10960.3   77.72 11320.3   77.59 11330.3   77.32 11510.3   76.71 11530.3   77.11
 11840.3   76.88 11868.7   78.16 11868.9   78.27 11876.8    82.5
BR U #Mann= 5
  1796.7      .1  4888.3    .032  5137.8      .1  8771.1     .06  9130.1      .1
BR U Banks=4888.3,5137.8
BR D #Sta/Elev= 144
  1796.7   88.48  1796.8   83.48  1936.8   82.38  2106.8   81.58  2176.8   82.58
  2276.8   82.98  2413.7   80.83  2416.8   80.78  2526.8   81.68  2706.8   79.98
  2756.8   80.58  2886.8   79.88  3006.8   79.68  3086.8   79.08    3555   78.18
    3755   77.98    3825   78.08  3941.8   77.98  4051.8   77.28  4111.8   77.78
  4163.4   77.54  4176.7   77.48  4336.7   77.18  4446.7   73.78  4506.9   73.08
  4616.9   75.78  4675.9   79.55  4677.3   79.67 4713.69      80  4713.8      80
 4713.91      80  4724.3   80.09    4781   80.29  4788.3   80.36  4847.4   80.89
  4848.8   80.92 4883.71    81.6  4883.8    81.6  4883.9    81.6  4888.3   81.69
  4922.3   71.81  4942.6   67.26  4944.3   66.88  4961.8   57.57  4964.2   57.56
  4978.6   57.11  4994.8   56.84  5005.3   56.66  5020.9   56.54  5038.1   57.76
  5042.6   62.22  5044.5   60.78  5097.4   72.64  5103.9    74.1    5124   78.92
 5124.09   78.94  5124.2   78.97    5125   79.16  5137.8   83.89  5182.5   83.88
  5236.5   83.86  5272.5   83.59  5312.1   83.29  5359.5   79.47    5391   76.93
    5431   78.05 5436.89    77.9    5437    77.9 5437.11    77.9  5437.5   77.89
  5453.8   77.48  5513.8   75.57  5603.8    77.3  5683.8   76.56  5963.9   76.64
  6033.9   76.55  6193.9   75.03  6223.9   74.84  6293.9   75.24  6313.9   75.84
  6364.8   75.66  6444.8   75.69  6464.8    75.5  6494.8    76.1  6564.8    76.1
  6614.8   76.07  6634.8    75.9  6734.8   76.01  6764.8      76  6864.8   75.59
  6904.8    76.4  6950.3   76.82  7000.3   76.86  7060.3   75.38  7090.3   75.21
  7120.3   75.23  7170.3   75.33  7210.3   75.22  7260.3   74.92  7280.3   75.34
  7790.3   73.66  7830.3   74.38  7920.3   74.58  8090.3   74.46  8160.3   73.39
  8180.6   73.64  8220.3   74.14  8260.3   73.27  8390.3   73.43  8440.3   76.01
  8710.3   77.03  8770.3   76.91  8771.1   76.77  8790.3    73.4 8830.11   73.52
 8830.23   73.52  8830.3   73.52 9070.07   74.24 9070.19   74.24  9070.3   74.24
  9090.3    74.3  9100.3   76.56  9130.1   77.13  9130.3   77.13  9670.3   75.64
 10060.3   76.44 10110.3      78 10190.3    77.8 10220.3   78.07 10240.3    77.7
 10270.3   78.24 10280.3   78.13 10670.3   77.54 10720.3   77.49 10950.3   77.41
 10960.3    77.7 11320.3   77.57 11330.3    77.3 11510.3   76.69 11530.3   77.09
 11840.3   76.86 11868.7   78.14 11868.9   78.25 11876.8   82.48
BR D #Mann= 5
  1796.7      .1  4888.3    .032  5137.8      .1  8771.1     .06  9130.1      .1
BR D Banks=4888.3,5137.8
BC Design=,, 0 ,, 0 ,,,,,,
BC HTab HWMax=88.48
BC Use User HTab Curves=0
BC User HTab FreeFlow(D)= 0

Type RM Length L Ch R = 1 ,155129.3,18.8,18.8,18.8
BEGIN DESCRIPTION:
Downstream Section of Bridge/Culvert/Weir
END DESCRIPTION:
XS GIS Cut Line= 6
      3114582.75     13913313.91      3113719.69     13912048.05
      3113538.83     13911690.53      3113463.12     13911387.69
      3113456.57     13910806.87      3115219.91     13903773.87
#Sta/Elev= 30
  1796.7   88.09  1796.8   83.09  1936.8   81.99  4336.7   76.79  4506.9   72.69
  4677.3   79.28  4888.3    81.3  4944.3   66.49  4961.8   57.18  5020.9   56.15
  5038.1   57.37  5042.6   61.83  5044.5   60.39  5103.9   73.71  5137.8    83.5
  5312.1    82.9    5391   76.54    5431   77.66  5513.8   75.18  5603.8   76.91
  6223.9   74.45  7000.3   76.47  8260.3   72.88  8771.1   76.38  8790.3   73.01
  9090.3   73.91  9130.1   76.74 11840.3   76.47 11868.7   77.75 11876.8   82.09
#Mann= 5 , 1 , 0
  1796.7      .1       0  4888.3    .032       0  5137.8      .1       0
  8771.1     .06       0  9130.1      .1       0
#XS Ineff= 3 ,-1
    1800    4873      82    5144    8760    81.4    9141   12900    81.2
Permanent Ineff=
       F       F       F
Bank Sta=4888.3,5137.8
XS Rating Curve= 0 ,0
Exp/Cntr=0.5,0.3

Type RM Length L Ch R = 1 ,155110.5,50,50,50
BEGIN DESCRIPTION:
Upstream Section of Bridge/Culvert/Weir
END DESCRIPTION:
XS GIS Cut Line= 6
       3114048.5     13912414.96       3113828.7     13912180.65
      3113631.01     13911898.84      3113496.42     13911461.41
      3113471.32     13910802.32      3115234.94     13903768.58
#Sta/Elev= 30
  2836.8   81.28    3022   79.97  3120.3   79.42  3550.1   78.59    3766    78.4
  4336.7   77.58  4506.9   73.48  4902.9   77.01  4984.3   55.66  4996.5   55.43
  5064.6   58.34  5120.1   75.35  5497.5   79.97  5683.8   76.96  6223.9   75.24
  7000.3   77.26  7090.3   75.61  8260.3   73.67  8390.3   73.83  8440.3   76.41
  8769.7   77.31  8790.3    73.8  9090.3    74.7  9100.3   76.96  9129.7   77.52
  9670.3   76.04 10270.3   78.64 11840.3   77.26 11868.7   78.54 11876.8   82.38
#Mann= 9 , 1 , 0
  2836.8     .14       0    3022     .05       0  3120.3      .1       0
  3550.1     .06       0    3766      .1       0  4902.9    .032       0
  5120.1      .1       0  8769.7     .06       0  9129.7      .1       0
#XS Ineff= 3 ,-1
    2830    4862      82    5143    8760    81.2    9141   11875    81.2
Permanent Ineff=
       F       F       F
Bank Sta=4902.9,5120.1
XS Rating Curve= 0 ,0
Exp/Cntr=0.5,0.3

Type RM Length L Ch R = 3 ,155085.5,,,
BEGIN DESCRIPTION:
EAST HARDY FRONTAGE ROAD
Structure ID: P00-44
END DESCRIPTION:
Bridge Culvert--1,0,-1,-1, 0
Deck Dist Width WeirC Skew NumUp NumDn MinLoCord MaxHiCord MaxSubmerge Is_Ogee
10,30,2.6,0, 60, 60, , , 0.95, 0, 1,1,,
  2836.8  2886.8  2956.8  3086.8  4336.7  4446.7  4506.9  4599.1  4673.7 4764.89
    4765 4903.91    4904  4970.2  5111.7 5133.79  5133.9  5284.2 5284.31  5332.7
  5414.7  5497.5  5683.8  6033.9  6223.9  6313.9  6464.8  6494.8  6864.8  7000.3
  7090.3  7280.3  7790.3  7830.3  8090.3  8160.3  8220.3  8260.3  8390.3  8440.3
  8536.2  8710.3  8770.3  8790.3  8796.2  9069.6  9090.3  9100.3  9130.3  9670.3
 10060.3 10110.3 10240.3 10270.3 10720.3 11320.3 11510.3 11840.3 11868.7 11876.8
    80.9    79.9    80.2    79.1   77.21   75.61   75.47   75.29   76.48   79.55
   80.55   85.49    85.5    87.4   87.18   86.63   86.62    81.3    80.3   78.56
   78.59    79.6   76.59   76.61   76.64   76.66   76.69    76.7   76.77   76.89
   76.82   76.86   76.96   76.97   77.03   77.04   77.05   77.06   77.09    77.1
    76.5   77.06   76.94   74.08      74   74.27    76.5   76.59   77.16   76.64
   76.74   78.03   77.73   78.27   77.52    77.6   77.09   76.88   78.16      82
   80.89   79.89   80.19   79.09   77.19   73.79   73.09   75.27    75.6   76.01
   76.01   76.33   80.49   82.39   82.17   81.62   75.13   76.97   76.97   77.56
   78.57   79.58   76.57   76.56   74.85   75.85   75.51   76.11    75.6   76.87
   75.22   75.35   73.67   74.39   74.47    73.4   74.15   73.28   73.44   76.02
   76.38   77.04   76.92   73.41   73.43   74.25   74.31   76.57   77.14   75.65
   76.45   78.01   77.71   78.25    77.5   77.58    76.7   76.87   78.15   81.99
  2836.8  2886.8  2956.8  3086.8  4336.7  4446.7  4506.9  4599.1  4673.7 4764.89
    4765 4903.91    4904  4970.2  5111.7 5133.79  5133.9  5284.2 5284.31  5332.7
  5414.7  5497.5  5683.8  6033.9  6223.9  6313.9  6464.8  6494.8  6864.8  7000.3
  7090.3  7280.3  7790.3  7830.3  8090.3  8160.3  8220.3  8260.3  8390.3  8440.3
  8536.2  8710.3  8770.3  8790.3  8796.2  9069.6  9090.3  9100.3  9130.3  9670.3
 10060.3 10110.3 10240.3 10270.3 10720.3 11320.3 11510.3 11840.3 11868.7 11876.8
    80.9    79.9    80.2    79.1   77.21   75.61   75.47   75.29   76.48   79.55
   80.55   85.49    85.5    87.4   87.18   86.63   86.62    81.3    80.3   78.56
   78.59    79.6   76.59   76.61   76.64   76.66   76.69    76.7   76.77   76.89
   76.82   76.86   76.96   76.97   77.03   77.04   77.05   77.06   77.09    77.1
    76.5   77.06   76.94   74.08      74   74.27    76.5   76.59   77.16   76.64
   76.74   78.03   77.73   78.27   77.52    77.6   77.09   76.88   78.16      82
   80.87   79.87   80.17   79.07   77.17   73.77   73.07   75.25   75.58   75.99
   75.99   76.31   80.47   82.37   82.15    81.6   75.11   76.95   76.95   77.54
   78.55   79.56   76.55   76.54   74.83   75.83   75.49   76.09   75.58   76.85
    75.2   75.33   73.65   74.37   74.45   73.38   74.13   73.26   73.42      76
   76.36   77.02    76.9   73.39   73.41   74.23   74.29   76.55   77.12   75.63
   76.43   77.99   77.69   78.23   77.48   77.56   76.68   76.85   78.13   81.97
Pier Skew, UpSta & Num, DnSta & Num=  ,4984.2, 2 ,4984.2, 2 , 0 , 0 , 0 ,,
     1.4     1.4
   54.26   83.37
     1.4     1.4
   54.24   83.35
Pier Skew, UpSta & Num, DnSta & Num=  ,5064.5, 2 ,5064.5, 2 , 0 , 0 , 0 ,,
     1.4     1.4
   56.93   83.24
     1.4     1.4
   56.91   83.22
Abutment Skew #Up #Dn= , 2 , 2
  4903.8  4944.2
   80.49   65.31
  4903.8  4944.2
   80.47   65.29
Abutment Skew #Up #Dn= , 2 , 2
  5061.8 5133.99
   57.89   81.62
  5061.8 5133.99
   57.87    81.6
BR Coef= 1 , 1 , 0 ,1.25, 0 ,,,0.8,0,2,0,
WSPro=,,,, 1 ,,,, 0 ,,,, 0 ,,,,-1 ,-1 ,-1 , 0 , 0 , 0 , 0 , 0
BR U #Sta/Elev= 132
  2836.8   80.89  2886.8   79.89  2956.8   80.19  3006.8   79.69    3022   79.58
  3086.8   79.09  3120.3   79.03  3550.1    78.2    3555   78.19    3755   77.99
    3766   78.01    3825   78.09  3882.5   78.04  3941.8   77.99  4051.8   77.29
  4111.8   77.79  4176.7   77.49  4336.7   77.19  4446.7   73.79  4506.9   73.09
  4598.6   75.27  4599.1   75.27  4673.7    75.6  4764.8   76.01 4764.89   76.01
    4765   76.01 4765.11   76.01  4819.9   76.25  4885.9   76.54  4902.9   76.62
  4903.8   76.36 4903.91   76.33    4904    76.3  4923.6   70.66  4944.2   65.31
  4944.3   65.28  4970.2   58.76  4978.2   56.74  4984.3   55.27  4996.5   55.04
  5007.6   56.43  5021.9   57.02  5061.8   57.89  5064.6   57.95  5088.6   65.59
  5111.7   72.46  5120.1   74.96 5133.79   75.13  5133.9   75.13  5160.7   75.46
  5265.1   76.74 5284.09   76.97  5284.2   76.97 5284.31   76.97  5332.7   77.56
  5414.7   78.57  5496.9   79.57  5497.5   79.58  5583.1   78.34    5584   78.33
  5666.7   77.28  5666.9   77.28  5683.8   76.57  5963.9   76.65  6033.9   76.56
  6193.9   75.04  6223.9   74.85  6293.9   75.25  6313.9   75.85  6364.8   75.67
  6444.8    75.7  6464.8   75.51  6494.8   76.11  6564.8   76.11  6614.8   76.08
  6634.8   75.91  6734.8   76.02  6764.8   76.01  6864.8    75.6  6904.8   76.41
  6950.3   76.83  7000.3   76.87  7060.3   75.39  7090.3   75.22  7120.3   75.24
  7170.3   75.34  7210.3   75.23  7260.3   74.93  7280.3   75.35  7790.3   73.67
  7830.3   74.39  7920.3   74.59  8090.3   74.47  8160.3    73.4  8220.3   74.15
  8260.3   73.28  8390.3   73.44  8440.3   76.02  8456.2   76.08  8536.2   76.38
  8616.2   76.68  8710.3   77.04  8769.7   76.92  8770.3   76.92  8790.3   73.41
  8796.2   73.43  9069.6   74.25  9086.2    74.3  9090.3   74.31  9100.3   76.57
  9129.7   77.13  9130.3   77.14  9670.3   75.65 10060.3   76.45 10110.3   78.01
 10190.3   77.81 10220.3   78.08 10240.3   77.71 10270.3   78.25 10280.3   78.14
 10670.3   77.55 10720.3    77.5 10950.3   77.42 10960.3   77.71 11320.3   77.58
 11330.3   77.31 11510.3    76.7 11530.3    77.1   11551   77.08 11840.3   76.87
 11868.7   78.15 11876.8   81.99
BR U #Mann= 9
  2836.8     .14    3022     .05  3120.3      .1  3550.1     .06    3766      .1
  4902.9    .032  5120.1      .1  8769.7     .06  9129.7      .1
BR U Banks=4902.9,5120.1
BR D #Sta/Elev= 132
  2836.8   80.87  2886.8   79.87  2956.8   80.17  3006.8   79.67    3022   79.56
  3086.8   79.07  3120.3   79.01  3550.1   78.18    3555   78.17    3755   77.97
    3766   77.99    3825   78.07  3882.5   78.02  3941.8   77.97  4051.8   77.27
  4111.8   77.77  4176.7   77.47  4336.7   77.17  4446.7   73.77  4506.9   73.07
  4598.6   75.25  4599.1   75.25  4673.7   75.58  4764.8   75.99 4764.89   75.99
    4765   75.99 4765.11   75.99  4819.9   76.23  4885.9   76.52  4902.9    76.6
  4903.8   76.34 4903.91   76.31    4904   76.28  4923.6   70.64  4944.2   65.29
  4944.3   65.26  4970.2   58.74  4978.2   56.72  4984.3   55.25  4996.5   55.02
  5007.6   56.41  5021.9      57  5061.8   57.87  5064.6   57.93  5088.6   65.57
  5111.7   72.44  5120.1   74.94 5133.79   75.11  5133.9   75.11  5160.7   75.44
  5265.1   76.72 5284.09   76.95  5284.2   76.95 5284.31   76.95  5332.7   77.54
  5414.7   78.55  5496.9   79.55  5497.5   79.56  5583.1   78.32    5584   78.31
  5666.7   77.26  5666.9   77.26  5683.8   76.55  5963.9   76.63  6033.9   76.54
  6193.9   75.02  6223.9   74.83  6293.9   75.23  6313.9   75.83  6364.8   75.65
  6444.8   75.68  6464.8   75.49  6494.8   76.09  6564.8   76.09  6614.8   76.06
  6634.8   75.89  6734.8      76  6764.8   75.99  6864.8   75.58  6904.8   76.39
  6950.3   76.81  7000.3   76.85  7060.3   75.37  7090.3    75.2  7120.3   75.22
  7170.3   75.32  7210.3   75.21  7260.3   74.91  7280.3   75.33  7790.3   73.65
  7830.3   74.37  7920.3   74.57  8090.3   74.45  8160.3   73.38  8220.3   74.13
  8260.3   73.26  8390.3   73.42  8440.3      76  8456.2   76.06  8536.2   76.36
  8616.2   76.66  8710.3   77.02  8769.7    76.9  8770.3    76.9  8790.3   73.39
  8796.2   73.41  9069.6   74.23  9086.2   74.28  9090.3   74.29  9100.3   76.55
  9129.7   77.11  9130.3   77.12  9670.3   75.63 10060.3   76.43 10110.3   77.99
 10190.3   77.79 10220.3   78.06 10240.3   77.69 10270.3   78.23 10280.3   78.12
 10670.3   77.53 10720.3   77.48 10950.3    77.4 10960.3   77.69 11320.3   77.56
 11330.3   77.29 11510.3   76.68 11530.3   77.08   11551   77.06 11840.3   76.85
 11868.7   78.13 11876.8   81.97
BR D #Mann= 9
  2836.8     .14    3022     .05  3120.3      .1  3550.1     .06    3766      .1
  4902.9    .032  5120.1      .1  8769.7     .06  9129.7      .1
BR D Banks=4902.9,5120.1
BC Design=,, 0 ,, 0 ,,,,,,
BC HTab HWMax=82.38
BC Use User HTab Curves=0
BC User HTab FreeFlow(D)= 0

Type RM Length L Ch R = 1 ,155060.5,1052,1052,1052
BEGIN DESCRIPTION:
Downstream Section of Bridge/Culvert/Weir
END DESCRIPTION:
XS GIS Cut Line= 6
      3114097.97      13912407.7      3113878.18     13912173.39
      3113680.49     13911891.58       3113545.9     13911454.15
       3113520.8     13910795.06      3115284.41     13903761.32
#Sta/Elev= 30
  2836.8   80.86    3022   79.55  3120.3      79  3550.1   78.17    3766   77.98
  4336.7   77.16  4506.9   73.06  4902.9   76.59  4984.3   55.24  4996.5   55.01
  5064.6   57.92  5120.1   74.93  5497.5   79.55  5683.8   76.54  6223.9   74.82
  7000.3   76.84  7090.3   75.19  8260.3   73.25  8390.3   73.41  8440.3   75.99
  8769.7   76.89  8790.3   73.38  9090.3   74.28  9100.3   76.54  9129.7    77.1
  9670.3   75.62 10270.3   78.22 11840.3   76.84 11868.7   78.12 11876.8   81.96
#Mann= 9 , 1 , 0
  2836.8     .14       0    3022     .05       0  3120.3      .1       0
  3550.1     .06       0    3766      .1       0  4902.9    .032       0
  5120.1      .1       0  8769.7     .06       0  9129.7      .1       0
#XS Ineff= 3 ,-1
    2830    4862    81.8    5143    8760      81    9141   11875      81
Permanent Ineff=
       F       F       F
Bank Sta=4902.9,5120.1
XS Rating Curve= 0 ,0
Exp/Cntr=0.5,0.3