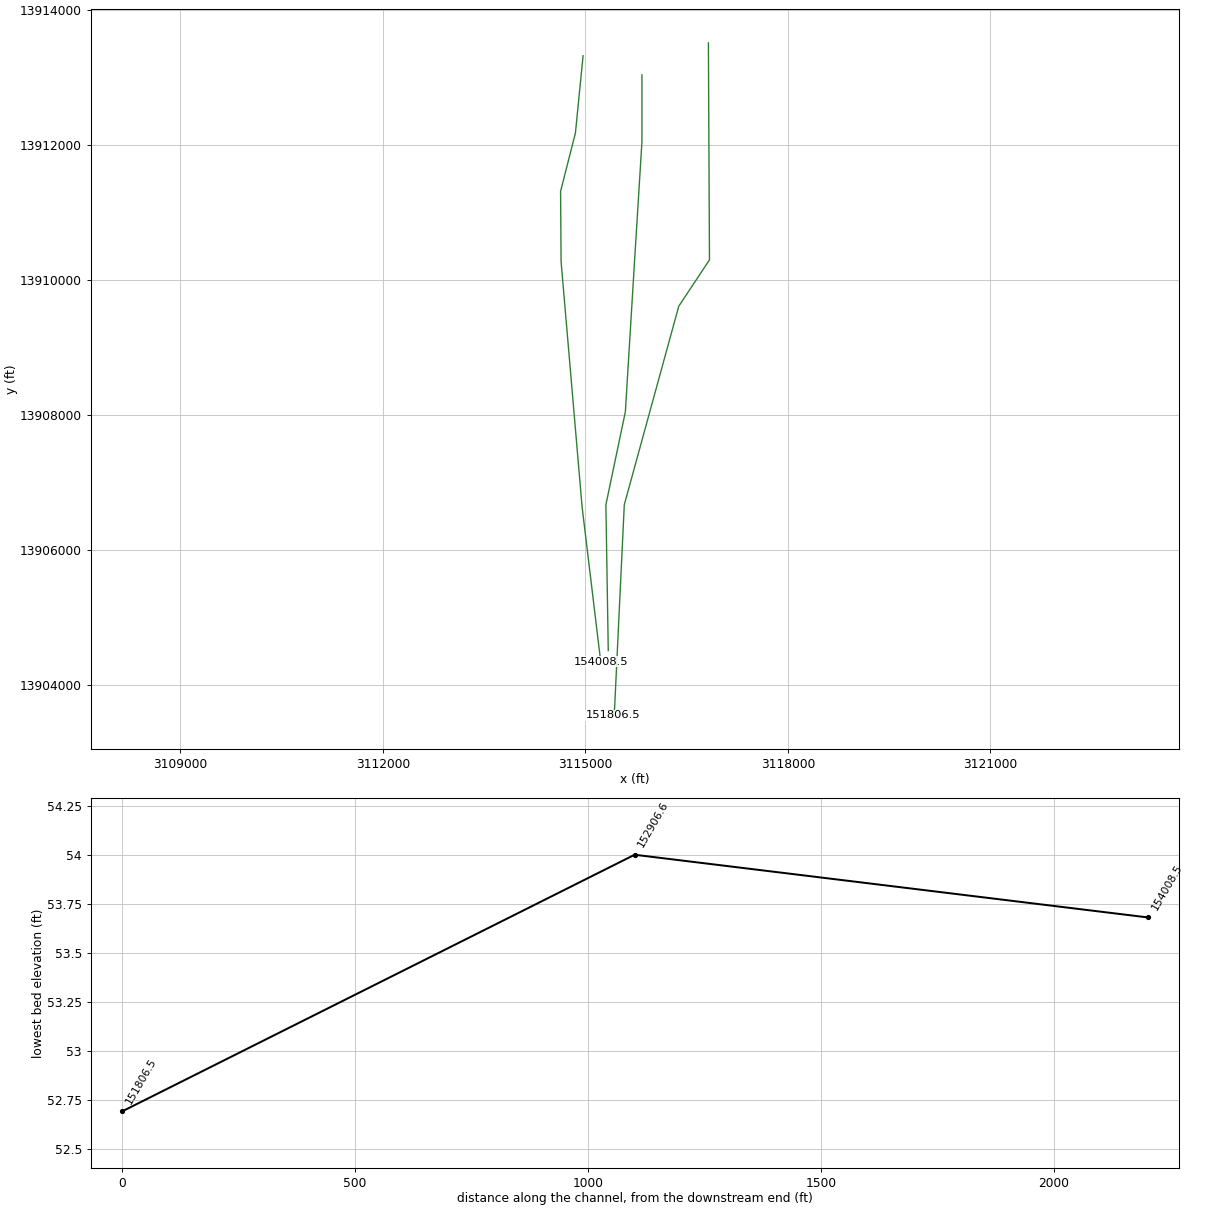
HEC-RAS study P100-00-00.prj: P100-00-00

--- P100-00-00.g01 (geometry) --- (continued)

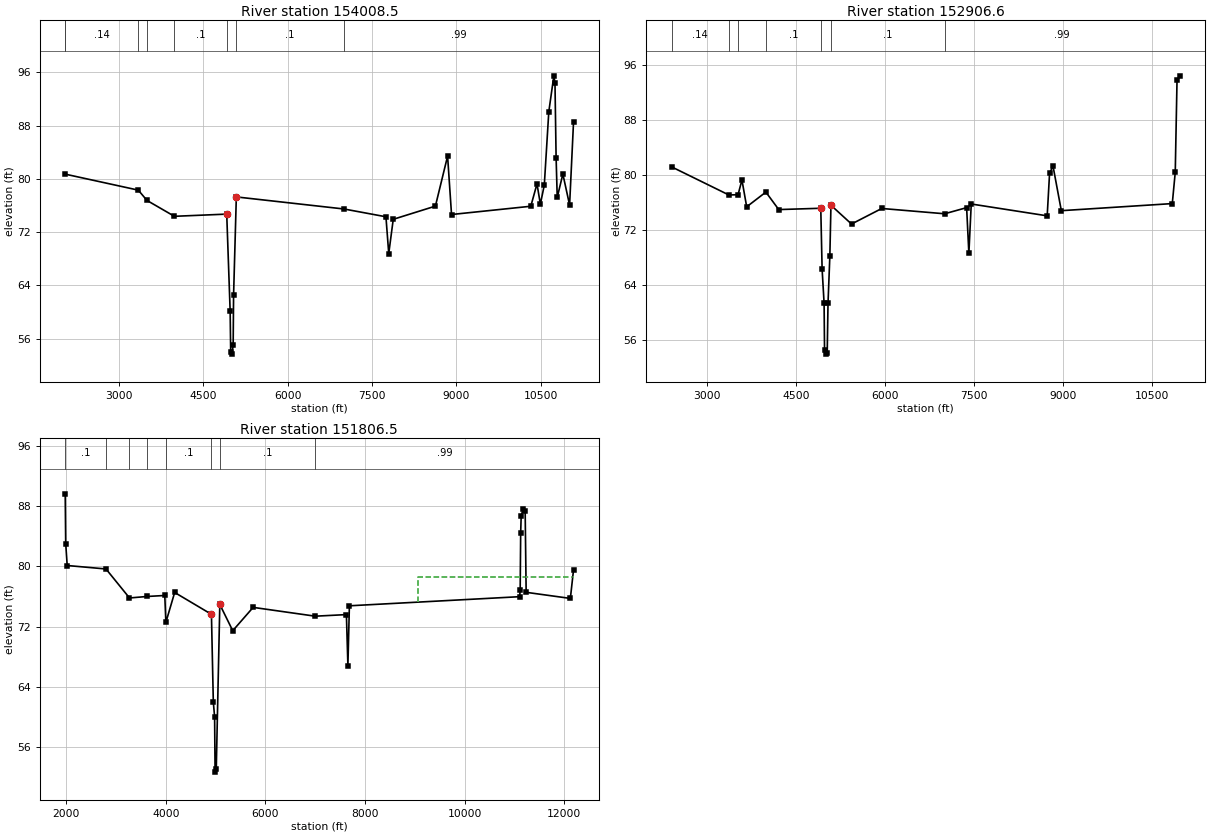
Type RM Length L Ch R = 1 ,154008.5,1136.8,1101.9,925.3
BEGIN DESCRIPTION:
Cross Section 154008.5
END DESCRIPTION:
XS GIS Cut Line= 6
       3114965.1     13913315.96      3114851.38     13912171.22
      3114631.53     13911306.98      3114639.11     13910264.58
      3114950.43     13906631.16      3115226.14     13904337.73
#Sta/Elev= 30
  2041.8    80.7  3341.6    78.3  3496.8   76.75  3983.8   74.37  4914.6    74.7
  4975.4   60.16    4985   54.05  5006.1   53.68  5029.1   55.01  5036.4    62.5
  5085.4   77.28    7000   75.47  7746.4    74.3  7796.4   68.78  7876.4   73.92
  8626.4    75.9  8843.1   83.41  8913.1   74.64 10323.1   75.88 10433.1   79.24
 10493.1    76.2 10563.1   79.05 10643.1   90.07 10733.1   95.46 10753.1   94.38
 10773.1   83.19 10793.1    77.2 10893.1   80.72 11013.1   76.06 11083.1   88.54
#Mann= 8 , 1 , 0
  2041.8      .2       0  2041.8     .14       0  3341.6      .1       0
  3496.8     .12       0  3983.8      .1       0  4914.6    .035       0
  5085.4      .1       0    7000     .99       0
#XS Ineff= 2 , 0
       0                  8843.1       0   83.41
Permanent Ineff=
       F       F
Bank Sta=4914.6,5085.4
XS Rating Curve= 0 ,0
Exp/Cntr=0.3,0.1

Type RM Length L Ch R = 1 ,152906.6,1166.9,1100.1,869
BEGIN DESCRIPTION:
Cross Section 152906.6
END DESCRIPTION:
XS GIS Cut Line= 6
      3115836.92     13913032.86      3115836.92     13912038.55
      3115730.79     13910325.23      3115591.49     13908041.51
      3115303.01     13906663.21      3115338.03     13904503.54
#Sta/Elev= 30
  2399.9    81.2  3364.4   77.12  3518.7   77.16  3584.2    79.3  3664.2    75.4
  3987.6   77.54  4204.2      75  4912.7   75.19  4935.3   66.35  4968.6   61.39
  4976.1    54.6  4997.5      54  5021.4   54.21  5034.8    61.4  5065.7   68.26
  5084.3   75.63  5430.8    72.9  5940.8   75.16    7000   74.39  7370.8   75.28
  7408.7   68.64  7448.7   75.81  8728.7   74.09  8768.7   80.27  8826.9   81.31
  8966.9   74.84 10836.9   75.87 10886.9   80.43 10916.9   93.84 10966.9   94.43
#Mann= 7 , 1 , 0
  2399.9     .14       0  3364.4      .1       0  3518.7     .12       0
  3987.6      .1       0  4912.7    .035       0  5084.3      .1       0
    7000     .99       0
#XS Ineff= 2 , 0
       0                  8826.9       0   81.31
Permanent Ineff=
       F       F
Bank Sta=4912.7,5084.3
XS Rating Curve= 0 ,0
Exp/Cntr=0.3,0.1

Type RM Length L Ch R = 1 ,151806.5,1620.7,976.3,494.1
BEGIN DESCRIPTION:
Cross Section 151806.5
END DESCRIPTION:
XS GIS Cut Line= 6
      3116821.81      13913506.2      3116837.63     13910291.11
      3116382.76     13909605.02      3115575.47     13906663.21
      3115431.91     13903648.59      3115412.46     13903546.77
#Sta/Elev= 30
  1978.1   89.65  1988.1   83.04  2018.1   80.13  2797.5   79.67  3269.4   75.82
  3628.4   76.02  3978.1   76.15  4000.2   72.58  4176.7   76.55  4915.4   73.65
  4953.2      62  4979.1   60.03  4988.7   52.69  5012.5   53.16  5083.5   74.96
  5343.2   71.47  5753.2   74.57    7000    73.4  7626.4   73.61  7656.4   66.85
  7686.4   74.78   11107   75.99   11117    76.9   11127   84.46   11137   86.69
   11177    87.7   11217   87.41   11237   76.57   12125   75.76 12188.7   79.56
#Mann= 8 , 1 , 0
  1978.1      .1       0  2797.5     .14       0  3269.4      .1       0
  3628.4     .12       0  4000.2      .1       0  4915.4    .035       0
  5083.5      .1       0    7000     .99       0
#XS Ineff= 2 , 0
       0                    9067       0    78.6
Permanent Ineff=
       F       F
Bank Sta=4915.4,5083.5
XS Rating Curve= 0 ,0
Exp/Cntr=0.3,0.1