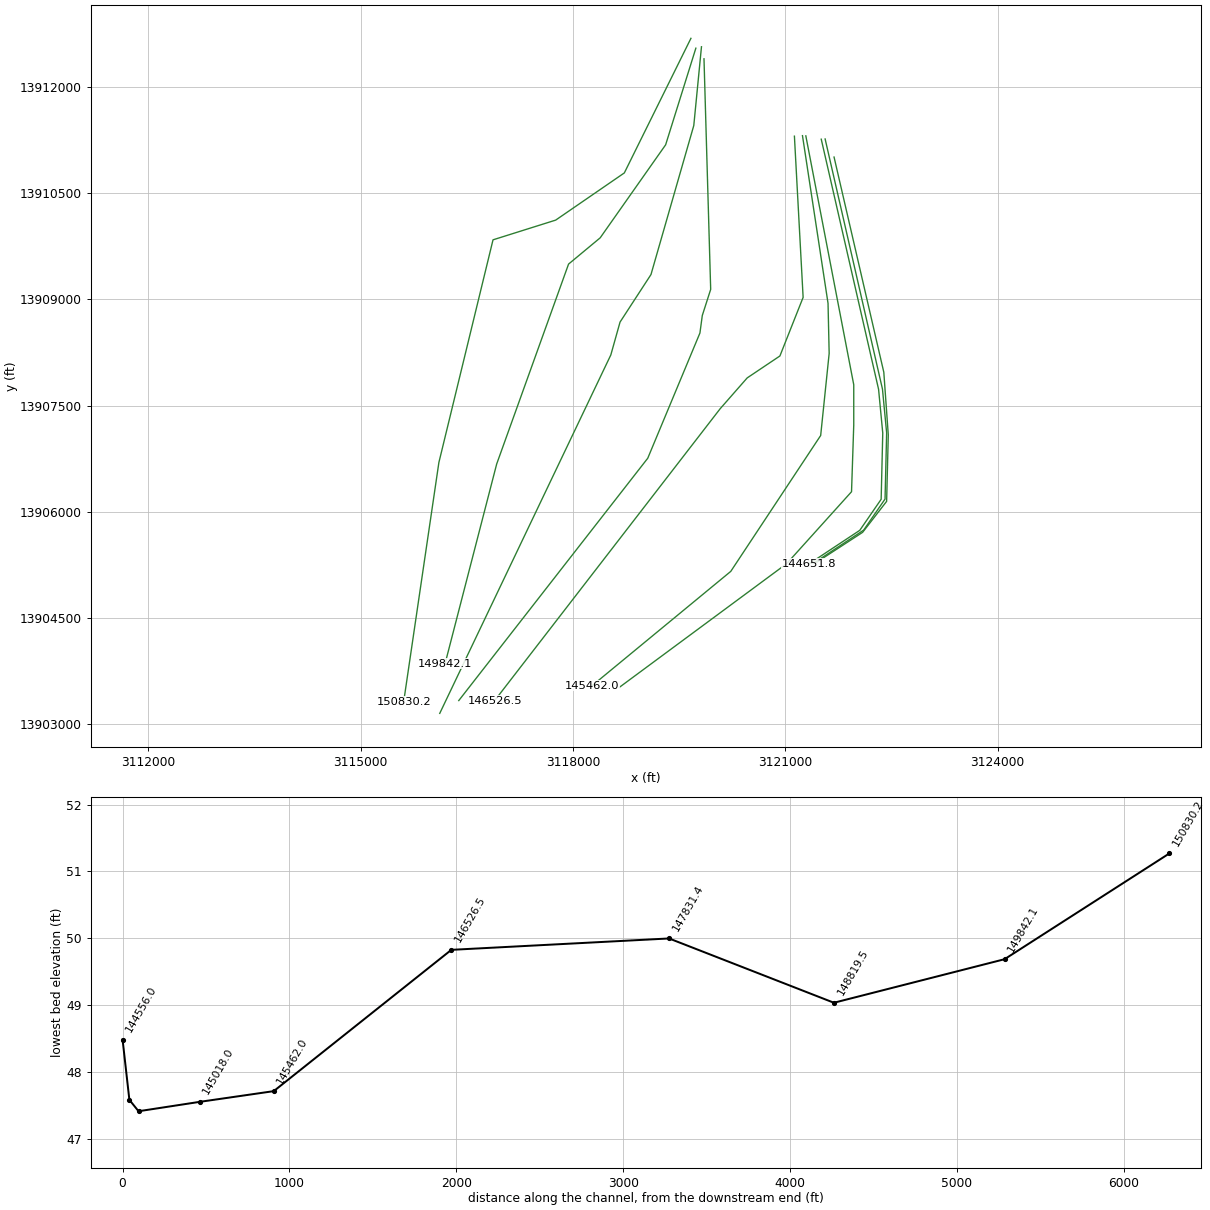
HEC-RAS study P100-00-00.prj: P100-00-00

--- P100-00-00.g01 (geometry) --- (continued)

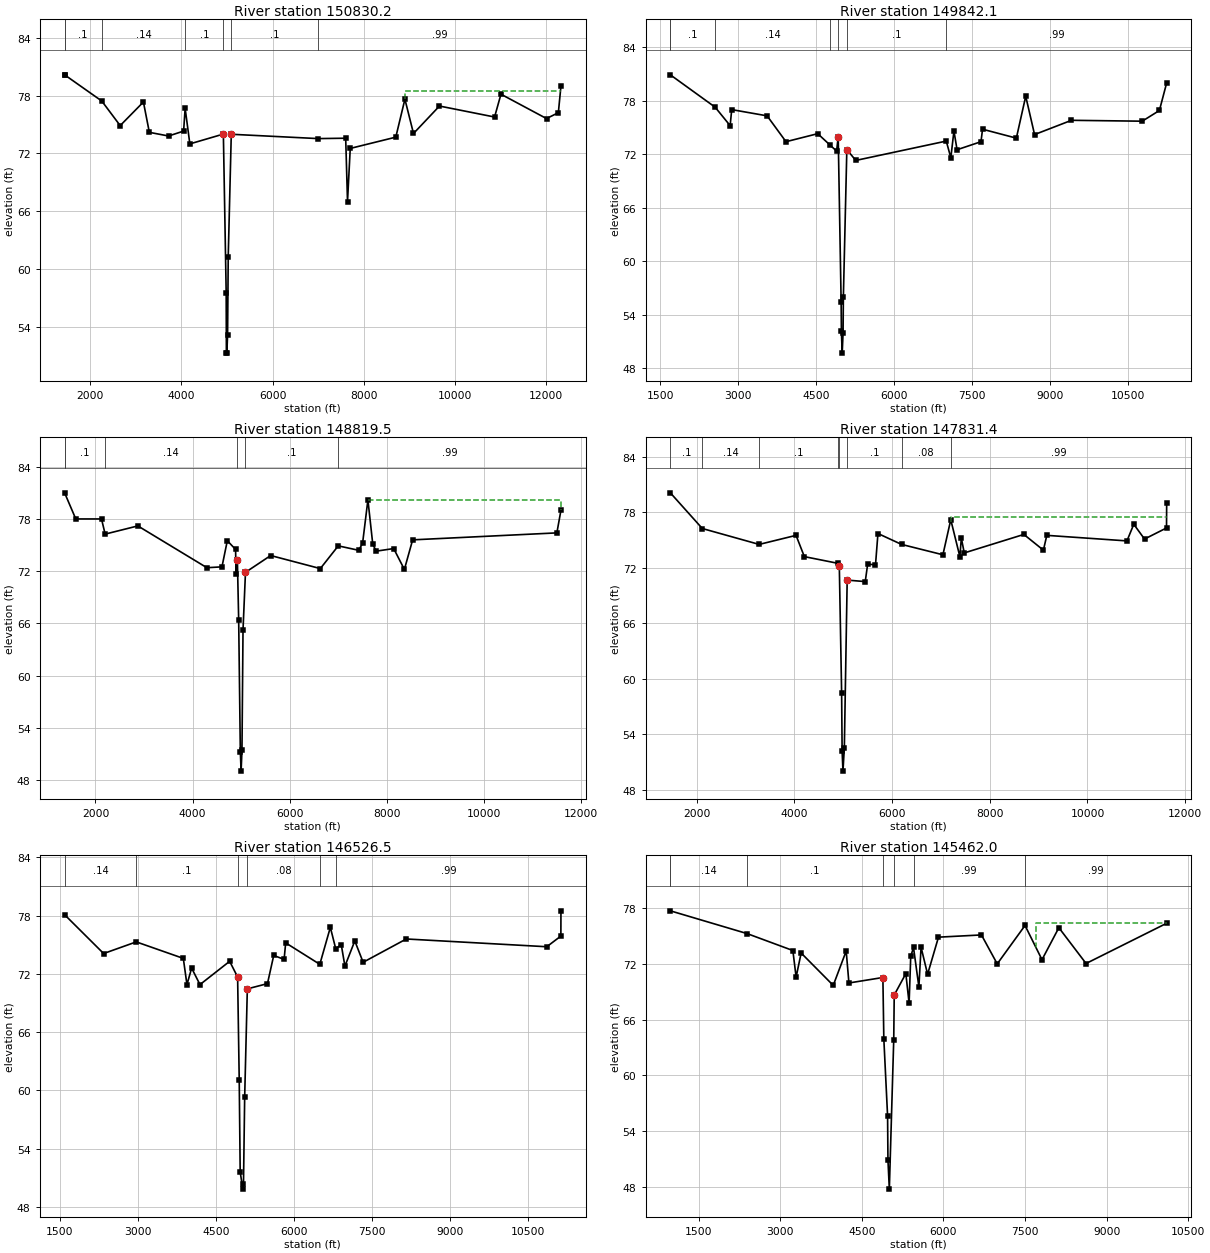
Type RM Length L Ch R = 1 ,150830.2,425,988.1,999.8
BEGIN DESCRIPTION:
Cross Section 150830.2
END DESCRIPTION:
XS GIS Cut Line= 6
      3119666.59      13912689.8      3118725.32     13910787.67
      3117754.94     13910120.54      3116869.44     13909842.11
      3116104.35     13906695.27       3115606.9     13903314.71
#Sta/Elev= 30
    1436   80.16  1436.1   80.16    2252   77.44  2656.1   74.89  3166.1   77.34
  3296.1   74.19  3718.4   73.81  4048.4   74.32  4082.1   76.68  4185.3   72.99
  4921.2   74.01  4982.9   57.56  4987.4   51.31  4997.4   51.27  5013.7   53.16
  5027.9   61.28  5094.8   73.99    7000   73.54  7606.5   73.58  7646.5   67.01
  7706.5   72.52  8706.5   73.69  8906.5   77.63    9095   74.07    9665   76.92
   10875   75.78   11015   78.15   12015   75.62   12275   76.23 12332.1      79
#Mann= 7 , 1 , 0
    1436      .2       0  1436.1      .1       0    2252     .14       0
  4082.1      .1       0  4921.2    .035       0  5094.8      .1       0
    7000     .99       0
#XS Ineff= 2 , 0
       0                  8906.5       0    78.5
Permanent Ineff=
       F       F
Bank Sta=4921.2,5094.8
XS Rating Curve= 0 ,0
Exp/Cntr=0.3,0.1

Type RM Length L Ch R = 1 ,149842.1,814.8,1022.6,1165.1
BEGIN DESCRIPTION:
Cross Section 149842.1
END DESCRIPTION:
XS GIS Cut Line= 6
      3119736.15     13912550.68      3119309.16     13911185.25
      3118384.17     13909870.36      3117936.88     13909498.89
      3116921.18     13906673.67      3116190.98     13903848.74
#Sta/Elev= 30
  1695.2    80.9  2556.8   77.27  2845.2    75.2  2875.2      77  3555.8    76.3
  3918.9    73.4  4528.9    74.3  4764.4   73.03  4891.9   72.35  4922.8   73.95
  4978.9   55.44  4983.9   52.14  4999.4   49.69  5016.1   51.98    5022      56
  5088.6   72.52  5260.5    71.3    7000   73.47  7087.7    71.6  7147.7    74.6
  7207.7    72.5  7667.7    73.4  7697.7    74.8  8347.7    73.8  8527.7    78.5
  8697.7    74.2  9407.7    75.8 10767.7    75.7 11097.7    76.9 11237.7      80
#Mann= 7 , 1 , 0
  1695.2      .2       0  1695.2      .1       0  2556.8     .14       0
  4764.4      .1       0  4922.8    .035       0  5088.6      .1       0
    7000     .99       0
#XS Ineff= 2 , 0
       0                  8527.7       0    78.5
Permanent Ineff=
       F       F
Bank Sta=4922.8,5088.6
XS Rating Curve= 0 ,0
Exp/Cntr=0.3,0.1

Type RM Length L Ch R = 1 ,148819.5,844,988.1,1065.7
BEGIN DESCRIPTION:
Cross Section 148819.5
END DESCRIPTION:
XS GIS Cut Line= 6
      3119815.65     13912570.56      3119706.94      13911457.4
      3119101.86     13909351.15      3118664.69     13908679.41
      3118534.38     13908215.24      3116116.42     13903149.03
#Sta/Elev= 30
  1364.8      81  1594.8      78  2124.8      78  2199.4   76.26  2873.3    77.2
    4295    72.4    4605    72.5  4715.2    75.5  4885.5    74.5  4895.1    71.7
  4922.4    73.3  4949.4   66.37  4983.3   51.28  4999.1   49.04  5017.1   51.42
  5038.7   65.27  5089.3   71.87  5608.4    73.8  6630.5    72.3    7000   74.91
  7420.5    74.4  7500.5    75.2  7610.5    80.2  7710.5    75.1  7780.5    74.3
  8141.5    74.6  8361.5    72.2  8531.5    75.6 11501.5    76.4 11585.6      79
#Mann= 6 , 1 , 0
  1364.8      .2       0  1364.8      .1       0  2199.4     .14       0
  4922.4    .035       0  5089.3      .1       0    7000     .99       0
#XS Ineff= 2 , 0
       0                  7610.5       0    80.2
Permanent Ineff=
       F       F
Bank Sta=4922.4,5089.3
XS Rating Curve= 0 ,0
Exp/Cntr=0.3,0.1

Type RM Length L Ch R = 1 ,147831.4,1392.5,1304.9,633
BEGIN DESCRIPTION:
Cross Section 147831.4
END DESCRIPTION:
XS GIS Cut Line= 6
      3119851.17     13912400.64      3119945.75     13909141.65
      3119827.24     13908772.69       3119793.7     13908524.48
      3119056.34     13906755.13      3116385.36     13903330.02
#Sta/Elev= 30
  1460.9    80.1  2115.7   76.24  3279.3   74.52  4034.1    75.5  4204.1    73.2
  4896.6   72.47 4919.68   72.21 4967.28   58.45 4977.28   52.16 4994.68      50
 5022.78   52.53 5080.98   70.66  5450.6    70.5  5500.6    72.4  5660.6    72.3
  5710.6    75.7  6194.4   74.52  7040.6    73.4  7201.3   77.19  7387.5    73.2
  7417.5    75.2  7477.5    73.6  8697.5    75.6  9097.5    73.9  9167.5    75.5
 10807.5    74.9 10947.5    76.7 11167.5    75.1 11617.5    76.3 11620.9      79
#Mann= 8 , 1 , 0
  1460.9      .1       0  2115.7     .14       0  3279.3      .1       0
  4896.6      .1       0 4919.68    .035       0 5080.98      .1       0
  6194.4     .08       0  7201.3     .99       0
#XS Ineff= 2 , 0
       0                  7210.6       0    77.5
Permanent Ineff=
       F       F
Bank Sta=4919.68,5080.98
XS Rating Curve= 0 ,0
Exp/Cntr=0.3,0.1

Type RM Length L Ch R = 1 ,146526.5,600.3,1064.5,1360.9
BEGIN DESCRIPTION:
Cross Section 146526.5
END DESCRIPTION:
XS GIS Cut Line= 6
      3121129.16     13911307.03      3121252.31     13909028.68
      3120924.29     13908200.62      3120461.79     13907890.42
      3120080.06     13907455.24      3116893.27     13903330.69
#Sta/Elev= 30
  1592.6    78.1  2342.6    74.1  2969.9    75.3  3874.2    73.6  3944.2    70.9
  4034.2    72.6  4194.2    70.9  4764.9    73.3  4917.9   71.68  4948.8    61.1
  4967.3   51.61  5017.7   49.83  5030.7   50.34  5053.6   59.31  5104.7   70.46
  5491.7      71  5611.7    73.9  5811.7    73.5  5841.7    75.2  6497.8   72.99
  6700.3    76.8  6802.8   74.61  6910.3      75  6980.3    72.8  7170.3    75.4
  7330.3    73.2  8160.3    75.6 10860.3    74.8 11131.1    75.9 11132.6    78.5
#Mann= 6 , 1 , 0
  1592.6     .14       0  2969.9      .1       0  4917.9    .035       0
  5104.7     .08       0  6497.8      .1       0  6802.8     .99       0
#XS Ineff= 2 , 0
       0                  6700.3       0    76.8
Permanent Ineff=
       F       F
Bank Sta=4917.9,5104.7
XS Rating Curve= 0 ,0
Exp/Cntr=0.3,0.1

Type RM Length L Ch R = 1 ,145462.0,237.9,444,825
BEGIN DESCRIPTION:
Cross Section 145462.0
END DESCRIPTION:
XS GIS Cut Line= 6
      3121243.12      13911314.3      3121604.34     13908944.67
      3121620.34     13908236.62      3121500.33     13907076.53
       3120229.6     13905155.95      3118268.04     13903539.29
#Sta/Elev= 30
     980   77.73  2388.5   75.28  3232.2   73.45  3292.2   70.59  3384.6   73.18
  3974.6   69.69  4212.8    73.4  4262.8   69.95  4887.2   70.54  4904.5   63.92
  4973.7    55.6  4980.2   50.87  5005.7   47.72  5086.7   63.83  5095.7   68.65
  5309.1   70.96  5369.1   67.77  5399.1   72.81    5450   73.78  5549.1   69.53
  5589.1    73.8  5709.1   70.89  5909.1   74.89  6699.1   75.13  6989.1   72.01
  7500.2   76.15    7812   72.46    8122   75.91    8622   72.05 10103.9   76.39
#Mann= 7 , 1 , 0
     980      .2       0     980     .14       0  2388.5      .1       0
  4887.2    .035       0  5095.7      .1       0    5450     .99       0
  7500.2     .99       0
#XS Ineff= 2 , 0
       0                  7705.5       0   76.42
Permanent Ineff=
       F       F
Bank Sta=4887.2,5095.7
XS Rating Curve= 0 ,0
Exp/Cntr=0.3,0.1

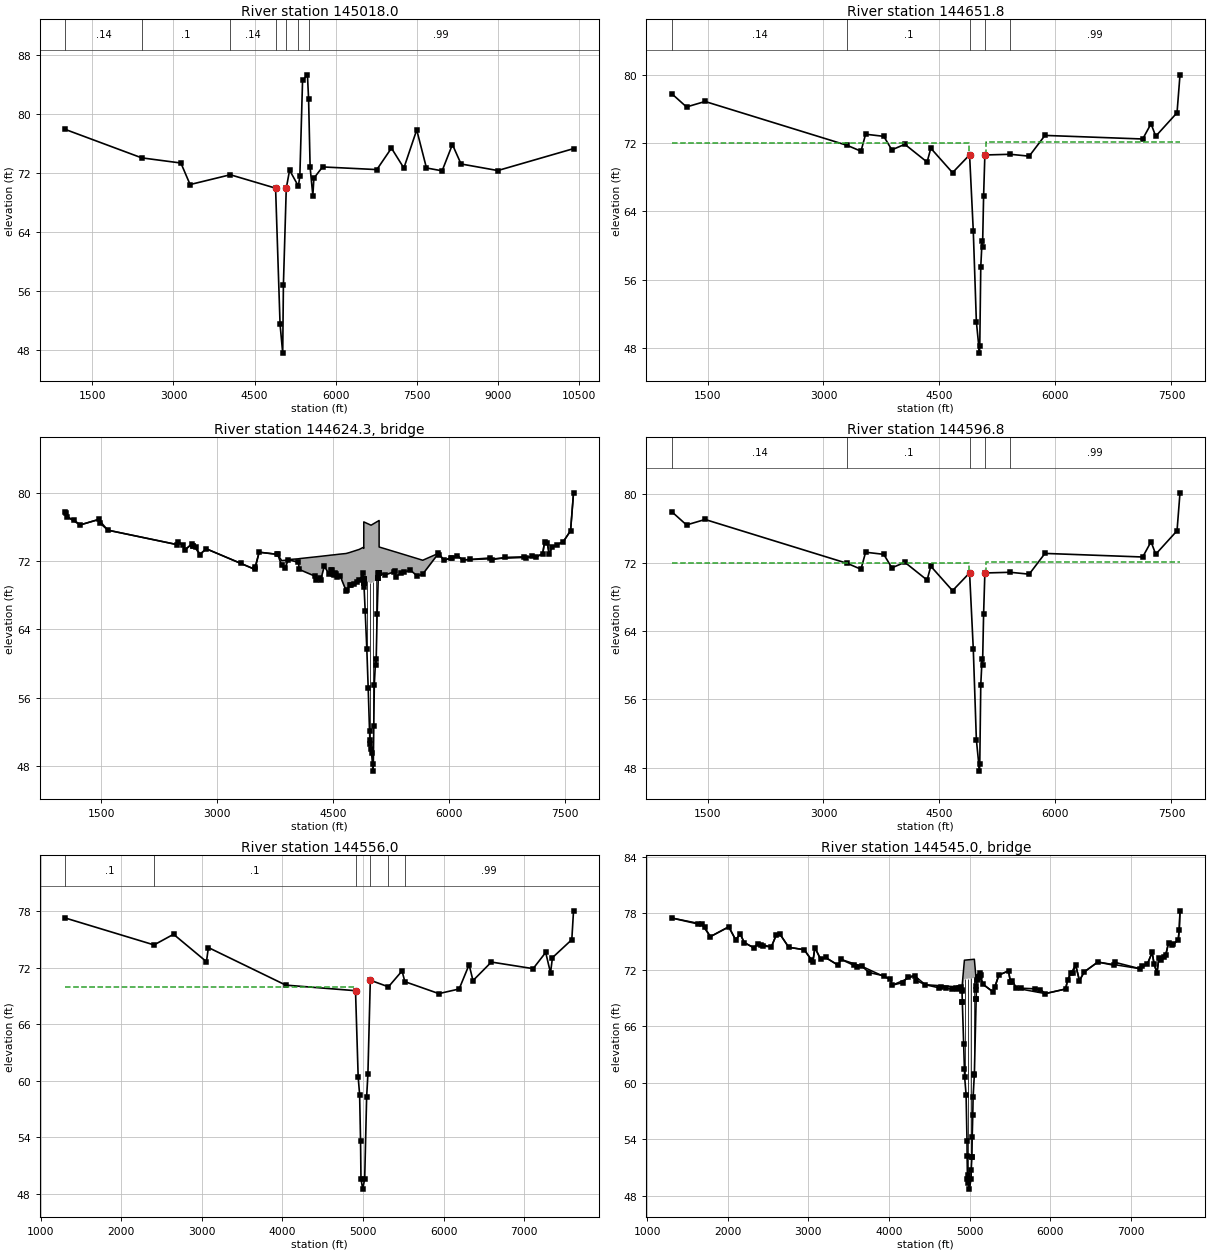
Type RM Length L Ch R = 1 ,145018.0,345.1,366.2,372.1
BEGIN DESCRIPTION:
Cross Section 145018.0-Interpolated
END DESCRIPTION:
XS GIS Cut Line= 6
      3121290.47     13911311.32      3121967.82     13907793.45
      3121967.82     13907225.35      3121936.42     13906281.81
      3121020.58     13905266.06      3118656.04     13903517.73
#Sta/Elev= 30
   997.9    77.9  2413.2   74.04  3137.9   73.34  3307.9   70.42    4052   71.75
  4889.5   69.93  4972.3   51.47  5021.3   47.56  5034.2   56.84  5087.1   69.92
  5148.5   72.37  5311.9   70.19  5338.5   71.62  5388.5   84.55  5478.5    85.3
    5500   82.03  5528.5   72.74  5578.5   68.93  5598.5   71.29  5758.5   72.81
  6762.5   72.45  7032.5   75.36  7262.5   72.66  7500.2   77.83  7680.2   72.67
  7970.2   72.28  8160.2   75.85  8320.2   73.21  9000.2   72.32 10400.9   75.29
#Mann= 7 , 1 , 0
   997.9     .14       0  2413.2      .1       0    4052     .14       0
  4889.5    .035       0  5087.1     .14       0  5311.9      .1       0
    5500     .99       0
Bank Sta=4889.5,5087.1
XS Rating Curve= 0 ,0
Exp/Cntr=0.5,0.3

Type RM Length L Ch R = 1 ,144651.8,55,55,55
BEGIN DESCRIPTION:
Upstream Section of Bridge/Culvert/Weir
END DESCRIPTION:
XS GIS Cut Line= 6
      3121508.32     13911264.42      3122318.61     13907729.88
       3122377.8     13907110.57      3122355.17     13906174.89
      3122053.03     13905736.14      3121339.45      13905264.4
#Sta/Elev= 30
  1036.5   77.79  1228.5   76.23  1468.5   76.87  3308.2   71.73  3484.8   71.05
  3544.8   73.04  3779.7   72.79    3884   71.21    4052   71.86    4340   69.78
    4388    71.4    4669   68.54  4889.5   70.62  4937.2   61.75  4977.2    51.1
  5017.5   47.42  5021.3   48.25  5034.2   57.53  5051.2   60.57  5057.1    59.8
  5070.8   65.79  5087.1   70.61  5415.7   70.69  5660.4   70.47  5864.4    72.9
  7128.5   72.48  7236.5   74.27  7296.5    72.8  7572.5   75.55  7610.9   79.99
#Mann= 5 , 1 , 0
  1036.5     .14       0  3308.2      .1       0  4889.5    .035       0
  5087.1      .1       0  5415.7     .99       0
#XS Ineff= 2 , 0
       0    4884      72    5096       0    72.1
Permanent Ineff=
       F       F
Bank Sta=4889.5,5087.1
XS Rating Curve= 0 ,0
Exp/Cntr=0.5,0.3

Type RM Length L Ch R = 3 ,144624.3,,,
BEGIN DESCRIPTION:
ALDINE-WESTFIELD ROAD
Structure ID: P00-41
END DESCRIPTION:
Bridge Culvert--1,0,-1,-1, 0
Deck Dist Width WeirC Skew NumUp NumDn MinLoCord MaxHiCord MaxSubmerge Is_Ogee
10,35,2.6,0, 60, 60, , , 0.95, 0, 1,1,,
  1036.5  1060.5  1228.5  1468.5  1588.5  2488.5  2500.5  2560.5  2584.5  2680.5
  2776.8  2860.8  3484.8  3544.8  3784.8    3836    3884    3920    4052    4064
    4268    4280    4340    4388    4448    4472    4508    4592    4669  4716.2
  4839.3  4889.5 4897.99  4898.1  4992.2  5070.8    5085  5087.1 5096.29  5096.4
 5096.51  5178.3  5297.7  5309.4  5501.4  5588.4  5660.4  5864.4  5936.4  6104.4
  6176.4  7128.5  7212.5  7236.5  7272.5  7296.5  7332.5  7476.5  7572.5  7610.9
   77.79   77.18   76.23   76.87   75.62   73.92   74.18   73.93   73.31   74.05
   72.77   73.44   71.05   73.04   72.79   72.06    72.1   72.18   72.27   72.29
   72.49    72.5   72.56   72.61   72.67    72.7   72.73   72.82   72.89   73.01
   73.37    73.6   73.49   76.59    76.2   76.62   76.69    76.7   76.75   76.75
   73.65   73.43    73.1   73.07   72.54    72.3    72.1   72.91    72.1   72.66
   72.14   72.48   72.88   74.27   74.06    72.8   73.62   74.25   75.55   79.99
   77.79   77.18   76.23   76.87   75.62   73.92   74.18   73.93   73.31   74.05
   72.77   73.44   71.05   73.04   72.78   71.49   71.21   72.17   71.86   71.02
   70.23   69.81   69.78    71.4   70.48   71.01   70.35   70.28   68.54   69.17
   69.73   70.62   69.79   69.79    69.4   69.82   69.99   70.61   70.59   70.59
   70.59   70.39   70.85   70.19   70.95   70.25   70.47    72.9   72.09   72.65
   72.13   72.48   72.88   74.27   74.06    72.8   73.62   74.25   75.55   79.99
  1036.5  1060.5  1228.5  1468.5  1588.5  2488.5  2500.5  2560.5  2584.5  2680.5
  2776.8  2860.8  3484.8  3544.8  3784.8    3836    3884    3920    4052    4064
    4268    4280    4340    4388    4448    4472    4508    4592    4669  4716.2
  4839.3  4889.5 4897.99  4898.1  4992.2  5070.8    5085  5087.1 5096.29  5096.4
 5096.51  5178.3  5297.7  5309.4  5501.4  5588.4  5660.4  5864.4  5936.4  6104.4
  6176.4  7128.5  7212.5  7236.5  7272.5  7296.5  7332.5  7476.5  7572.5  7610.9
   77.79   77.18   76.23   76.87   75.62   73.92   74.18   73.93   73.31   74.05
   72.77   73.44   71.05   73.04   72.79   72.06    72.1   72.18   72.27   72.29
   72.49    72.5   72.56   72.61   72.67    72.7   72.73   72.82   72.89   73.01
   73.37    73.6   73.49   76.59    76.2   76.62   76.69    76.7   76.75   76.75
   73.65   73.43    73.1   73.07   72.54    72.3    72.1   72.91    72.1   72.66
   72.14   72.48   72.88   74.27   74.06    72.8   73.62   74.25   75.55   79.99
   77.74   77.13   76.18   76.82   75.57   73.87   74.13   73.88   73.26      74
   72.72   73.39      71   72.99   72.73   71.44   71.16   72.12   71.81   70.97
   70.18   69.76   69.73   71.35   70.43   70.96    70.3   70.23   68.49   69.12
   69.68   70.57   69.74   69.74   69.35   69.77   69.94   70.56   70.54   70.54
   70.54   70.34    70.8   70.14    70.9    70.2   70.42   72.85   72.04    72.6
   72.08   72.43   72.83   74.22   74.01   72.75   73.57    74.2    75.5   79.94
Pier Skew, UpSta & Num, DnSta & Num=  ,4937.2, 2 ,4937.2, 2 , 0 , 0 , 0 ,,
       1       1
   60.62   70.63
       1       1
   60.57   70.58
Pier Skew, UpSta & Num, DnSta & Num=  ,4977.2, 2 ,4977.2, 2 , 0 , 0 , 0 ,,
       1       1
   50.05   70.46
       1       1
      50   70.41
Pier Skew, UpSta & Num, DnSta & Num=  ,5017.5, 2 ,5017.5, 2 , 0 , 0 , 0 ,,
     1.3     1.3
   46.49   70.53
     1.3     1.3
   46.44   70.48
Pier Skew, UpSta & Num, DnSta & Num=  ,5057, 2 ,5057, 2 , 0 , 0 , 0 ,,
     1.3     1.3
    58.9   70.74
     1.3     1.3
   58.85   70.69
BR Coef= 1 , 1 , 0 ,1.25, 0 ,,,0.8,0,2,0,
WSPro=,,,, 1 ,,,, 0 ,,,, 0 ,,,,-1 ,-1 ,-1 , 0 , 0 , 0 , 0 , 0
BR U #Sta/Elev= 115
  1036.5   77.79  1048.5   77.67  1060.5   77.18  1156.5   76.76  1228.5   76.23
  1468.5   76.87  1480.5    76.5  1588.5   75.62  2488.5   73.92  2500.5   74.18
  2560.5   73.93  2584.5   73.31  2680.5   74.05  2692.5   73.77  2692.8   73.77
  2728.8   73.67  2776.8   72.77  2860.8   73.44  3308.2   71.73  3484.8   71.05
  3496.8   71.29  3544.8   73.04  3779.7   72.79  3784.8   72.78    3836   71.49
    3884   71.21    3920   72.17    4052   71.86    4064   71.02    4268   70.23
    4280   69.81    4328   70.03    4340   69.78    4388    71.4    4448   70.48
    4472   71.01    4484   70.93    4496   70.45    4508   70.35    4520   70.59
    4544   70.49    4556   70.09    4592   70.28    4669   68.54    4676   68.63
  4716.2   69.17  4731.8   69.21  4775.9   69.32  4810.9   69.55  4839.3   69.73
  4889.5   70.62 4894.71   69.92 4894.83   69.91  4894.9    69.9  4897.2   69.59
 4897.99   69.48  4898.1   69.47 4898.21   69.45  4901.8   68.97    4916   66.19
  4937.2   61.75  4955.3   57.11  4972.3   52.16  4977.2    51.1  4983.3   50.54
  4992.2   49.98  4998.4   49.59  5017.5   47.42  5021.3   48.25  5027.6   52.66
  5034.2   57.53  5051.2   60.57  5057.1    59.8  5070.8   65.79    5085   69.99
 5085.09   70.02  5085.2   70.05  5087.1   70.61 5096.29   70.59  5096.4   70.59
 5096.51   70.59  5097.5   70.58  5178.3   70.39  5288.4   70.74  5297.7   70.85
  5309.4   70.19  5381.4   70.59  5415.7   70.69  5501.4   70.95  5588.4   70.25
  5660.4   70.47  5864.4    72.9  5876.8   72.76  5936.4   72.09  6020.4   72.34
  6044.4   72.33  6104.4   72.65  6176.4   72.13  6272.8   72.19  6536.4   72.37
  6552.5   72.16  6720.5   72.43  6972.5    72.5  6996.5    72.4  7068.5   72.54
  7128.5   72.48  7212.5   72.88  7236.5   74.27  7272.5   74.06  7296.5    72.8
  7332.5   73.62  7392.5    73.9  7476.5   74.25  7572.5   75.55  7610.9   79.99
BR U #Mann= 5
  1036.5     .14  3308.2      .1  4889.5    .035  5087.1      .1  5415.7     .99
BR U Banks=4889.5,5087.1
BR D #Sta/Elev= 115
  1036.5   77.74  1048.5   77.62  1060.5   77.13  1156.5   76.71  1228.5   76.18
  1468.5   76.82  1480.5   76.45  1588.5   75.57  2488.5   73.87  2500.5   74.13
  2560.5   73.88  2584.5   73.26  2680.5      74  2692.5   73.72  2692.8   73.72
  2728.8   73.62  2776.8   72.72  2860.8   73.39  3308.2   71.68  3484.8      71
  3496.8   71.24  3544.8   72.99  3779.7   72.74  3784.8   72.73    3836   71.44
    3884   71.16    3920   72.12    4052   71.81    4064   70.97    4268   70.18
    4280   69.76    4328   69.98    4340   69.73    4388   71.35    4448   70.43
    4472   70.96    4484   70.88    4496    70.4    4508    70.3    4520   70.54
    4544   70.44    4556   70.04    4592   70.23    4669   68.49    4676   68.58
  4716.2   69.12  4731.8   69.16  4775.9   69.27  4810.9    69.5  4839.3   69.68
  4889.5   70.57 4894.71   69.87 4894.83   69.86  4894.9   69.85  4897.2   69.54
 4897.99   69.43  4898.1   69.42 4898.21    69.4  4901.8   68.92    4916   66.14
  4937.2    61.7  4955.3   57.06  4972.3   52.11  4977.2   51.05  4983.3   50.49
  4992.2   49.93  4998.4   49.54  5017.5   47.37  5021.3    48.2  5027.6   52.61
  5034.2   57.48  5051.2   60.52  5057.1   59.75  5070.8   65.74    5085   69.94
 5085.09   69.97  5085.2      70  5087.1   70.56 5096.29   70.54  5096.4   70.54
 5096.51   70.54  5097.5   70.53  5178.3   70.34  5288.4   70.69  5297.7    70.8
  5309.4   70.14  5381.4   70.54  5415.7   70.64  5501.4    70.9  5588.4    70.2
  5660.4   70.42  5864.4   72.85  5876.8   72.71  5936.4   72.04  6020.4   72.29
  6044.4   72.28  6104.4    72.6  6176.4   72.08  6272.8   72.14  6536.4   72.32
  6552.5   72.11  6720.5   72.38  6972.5   72.45  6996.5   72.35  7068.5   72.49
  7128.5   72.43  7212.5   72.83  7236.5   74.22  7272.5   74.01  7296.5   72.75
  7332.5   73.57  7392.5   73.85  7476.5    74.2  7572.5    75.5  7610.9   79.94
BR D #Mann= 5
  1036.5     .14  3308.2      .1  4889.5    .035  5087.1      .1  5415.7     .99
BR D Banks=4889.5,5087.1
BC Design=,, 0 ,, 0 ,,,,,,
BC HTab HWMax=79.99
BC Use User HTab Curves=0
BC User HTab FreeFlow(D)= 0

Type RM Length L Ch R = 1 ,144596.8,40.8,40.8,40.8
BEGIN DESCRIPTION:
Downstream Section of Bridge/Culvert/Weir
END DESCRIPTION:
XS GIS Cut Line= 6
      3121563.24     13911267.46      3122373.53     13907732.92
      3122432.72     13907113.61      3122410.09     13906177.93
      3122107.95     13905739.18      3121394.37     13905267.44
#Sta/Elev= 30
  1036.5   77.96  1228.5    76.4  1468.5   77.04  3308.2    71.9  3484.8   71.22
  3544.8   73.21  3779.7   72.96    3884   71.38    4052   72.03    4340   69.95
    4388   71.57    4669   68.71  4889.5   70.79  4937.2   61.92  4977.2   51.27
  5017.5   47.59  5021.3   48.42  5034.2    57.7  5051.2   60.74  5057.1   59.97
  5070.8   65.96  5087.1   70.78  5415.7   70.86  5660.4   70.64  5864.4   73.07
  7128.5   72.65  7236.5   74.44  7296.5   72.97  7572.5   75.72  7610.9   80.16
#Mann= 5 , 1 , 0
  1036.5     .14       0  3308.2      .1       0  4889.5    .035       0
  5087.1      .1       0  5415.7     .99       0
#XS Ineff= 2 , 0
       0    4884      72    5096       0    72.1
Permanent Ineff=
       F       F
Bank Sta=4889.5,5087.1
XS Rating Curve= 0 ,0
Exp/Cntr=0.5,0.3

Type RM Length L Ch R = 1 ,144556.0,22,22,22
BEGIN DESCRIPTION:
Upstream Section of Bridge/Culvert/Weir
END DESCRIPTION:
XS GIS Cut Line= 6
      3121689.41     13911011.83      3122392.74     13907970.09
      3122455.87     13907084.67      3122432.46     13906145.38
      3122093.08     13905707.76      3121421.38     13905270.67
#Sta/Elev= 30
  1305.8   77.28  2407.6   74.42  2649.8   75.55  3057.8   72.64  3081.8   74.14
  4041.8   70.15 4906.51   69.56 4939.71   60.38 4957.51   58.52 4969.01    53.6
 4974.31   49.59 4995.71   48.49 5020.31   49.57 5044.51   58.27 5060.21   60.69
 5090.01   70.67    5315   69.97  5483.9   71.66  5518.3   70.52  5939.9   69.25
  6191.9   69.74  6315.5   72.32  6363.5   70.63  6591.5    72.6  7109.3    71.9
  7265.3   73.62  7325.3   71.45  7349.3   73.07  7589.3   74.98  7610.7   78.04
#Mann= 6 , 1 , 0
  1305.8      .1       0  2407.6      .1       0 4906.51    .035       0
 5090.01      .1       0    5315      .1       0  5518.3     .99       0
#XS Ineff= 2 , 0
       0    4896      70    5100       0    70.6
Permanent Ineff=
       F       F
Bank Sta=4906.51,5090.01
XS Rating Curve= 0 ,0
Exp/Cntr=0.5,0.3

Type RM Length L Ch R = 3 ,144545.0,,,
BEGIN DESCRIPTION:
28" PIPELINE
Structure ID: PL1_P00-41A
END DESCRIPTION:
Bridge Culvert--1,0,-1,-1, 0
Deck Dist Width WeirC Skew NumUp NumDn MinLoCord MaxHiCord MaxSubmerge Is_Ogee
10,2,2.6,0, 60, 60, , , 0.95, 0, 1,1,,
  1305.8  1677.8  1785.8  2013.8  2097.8  2157.8  2205.8  2325.8  2373.8  2541.8
  2601.8  2649.8  2757.8  2949.8  3057.8  3081.8  3153.8  3213.8  3369.8  3405.8
  3669.8  4017.8  4041.8  4317.8  4451.8 4899.51 4906.51 4911.01 4936.61 5060.01
 5082.21 5086.61 5090.01 5125.91  5161.5  5293.5  5363.9  5483.9  5507.9  5531.9
  5579.9  5939.9  6191.9  6215.9  6315.5  6363.5  6423.5  6591.5  7109.3  7205.3
  7265.3  7289.3  7325.3  7349.3  7433.3  7469.3  7505.3  7589.3  7601.3  7610.7
    77.5   76.86   75.52   76.56   75.21   75.77   74.89   74.33   74.78   74.43
   75.67   75.77   74.39   74.13   72.86   74.36   73.11   73.31   72.49   73.11
   72.35   70.97   70.37   71.37   70.42   70.16   70.12   70.55   73.02   73.12
   71.01   70.59   70.89   71.61    70.5   69.64   71.44   71.88   70.67   70.83
   70.04   69.47   69.96   70.89   72.54   70.85   71.78   72.82   72.12    72.6
   73.84   72.61   71.67   73.29   73.56   74.88   74.58    75.2   76.27   78.26
    77.5   76.86   75.52   76.56   75.21   75.77   74.89   74.33   74.78   74.43
   75.67   75.77   74.39   74.13   72.86   74.36   73.11   73.31   72.49   73.11
   72.35   70.97   70.37   71.37   70.42   70.16   69.78   68.56   71.02   71.12
   68.95   70.24   70.89   71.61    70.5   69.64   71.44   71.88   70.67   70.83
   70.04   69.47   69.96   70.89   72.54   70.85   71.78   72.82   72.12    72.6
   73.84   72.61   71.67   73.29   73.56   74.88   74.58    75.2   76.27   78.26
  1305.8  1677.8  1785.8  2013.8  2097.8  2157.8  2205.8  2325.8  2373.8  2541.8
  2601.8  2649.8  2757.8  2949.8  3057.8  3081.8  3153.8  3213.8  3369.8  3405.8
  3669.8  4017.8  4041.8  4317.8  4451.8 4899.51 4906.51 4911.01 4936.61 5060.01
 5082.21 5086.61 5090.01 5125.91  5161.5  5293.5  5363.9  5483.9  5507.9  5531.9
  5579.9  5939.9  6191.9  6215.9  6315.5  6363.5  6423.5  6591.5  7109.3  7205.3
  7265.3  7289.3  7325.3  7349.3  7433.3  7469.3  7505.3  7589.3  7601.3  7610.7
    77.5   76.86   75.52   76.56   75.21   75.77   74.89   74.33   74.78   74.43
   75.67   75.77   74.39   74.13   72.86   74.36   73.11   73.31   72.49   73.11
   72.35   70.97   70.37   71.37   70.42   70.16   70.12   70.55   73.02   73.12
   71.01   70.59   70.89   71.61    70.5   69.64   71.44   71.88   70.67   70.83
   70.04   69.47   69.96   70.89   72.54   70.85   71.78   72.82   72.12    72.6
   73.84   72.61   71.67   73.29   73.56   74.88   74.58    75.2   76.27   78.26
    77.5   76.86   75.52   76.56   75.21   75.77   74.89   74.33   74.78   74.43
   75.67   75.77   74.39   74.13   72.86   74.36   73.11   73.31   72.49   73.11
   72.35   70.97   70.37   71.37   70.42   70.16   69.78   68.56   71.02   71.12
   68.95   70.24   70.89   71.61    70.5   69.64   71.44   71.88   70.67   70.83
   70.04   69.47   69.96   70.89   72.54   70.85   71.78   72.82   72.12    72.6
   73.84   72.61   71.67   73.29   73.56   74.88   74.58    75.2   76.27   78.26
Pier Skew, UpSta & Num, DnSta & Num=  ,4939.7, 2 ,4939.7, 2 , 0 , 0 , 0 ,,
     1.3     1.3
   59.53   72.02
     1.3     1.3
   59.53   72.02
Pier Skew, UpSta & Num, DnSta & Num=  ,4980.1, 2 ,4980.1, 2 , 0 , 0 , 0 ,,
     1.3     1.3
   49.08   72.06
     1.3     1.3
   49.08   72.06
Pier Skew, UpSta & Num, DnSta & Num=  ,5020.3, 2 ,5020.3, 2 , 0 , 0 , 0 ,,
     1.3     1.3
   48.76   72.09
     1.3     1.3
   48.76   72.09
Pier Skew, UpSta & Num, DnSta & Num=  ,5060.2, 2 ,5060.2, 2 , 0 , 0 , 0 ,,
     1.3     1.3
   59.81   72.12
     1.3     1.3
   59.81   72.12
BR Coef= 1 , 1 , 0 ,1.25, 0 ,,,0.8,0,2,0,
WSPro=,,,, 1 ,,,, 0 ,,,, 0 ,,,,-1 ,-1 ,-1 , 0 , 0 , 0 , 0 , 0
BR U #Sta/Elev= 119
  1305.8    77.5  1629.8   76.87  1677.8   76.86  1713.8   76.51  1785.8   75.52
  2013.8   76.56  2097.8   75.21  2157.8   75.77  2205.8   74.89  2325.8   74.33
  2373.8   74.78  2407.6   74.64  2433.8   74.53  2541.8   74.43  2601.8   75.67
  2649.8   75.77  2757.8   74.39  2949.8   74.13  3033.8   73.09  3057.8   72.86
  3081.8   74.36  3153.8   73.11  3213.8   73.31  3369.8   72.49  3405.8   73.11
  3561.8   72.49  3609.8   72.33  3669.8   72.35  3753.8   71.71  3933.8   71.37
  4017.8   70.97  4041.8   70.37  4173.8   70.64  4233.8   71.26  4317.8   71.37
  4341.8   70.86  4451.8   70.42  4619.8   70.09  4643.8   70.21  4703.8   70.07
  4784.7   69.93  4832.7   70.09 4850.91   69.91 4867.61   70.02 4882.81   70.11
 4899.51   70.16 4905.81   69.82 4906.51   69.78 4910.92   68.58 4911.01   68.56
 4927.31   64.14 4936.61   61.48 4939.71    60.6 4957.51   58.74 4969.01   53.82
 4970.31    52.2 4974.31   49.81 4980.11   50.23 4983.71   49.38 4995.71   48.71
 5020.31   49.79 5021.11   50.79 5029.71   52.14 5030.01   52.14 5033.31   54.29
 5040.31   56.54 5044.51   58.49 5060.01   60.88 5060.21   60.91  5082.1   68.91
 5082.21   68.95 5084.81    69.9 5086.61   70.24 5090.01   70.89 5099.71   71.27
 5110.61   71.05 5118.21   71.24 5125.91   71.61 5132.31   71.37 5139.51   71.41
  5161.5    70.5  5293.5   69.64    5315   70.19  5363.9   71.44  5483.9   71.88
  5507.9   70.67  5518.3   70.74  5531.9   70.83  5579.9   70.04  5639.9   70.04
  5807.9   69.98  5879.9    69.9  5939.9   69.47  6191.9   69.96  6215.9   70.89
  6255.5   71.69  6279.5   71.61  6315.5   72.54  6363.5   70.85  6423.5   71.78
  6591.5   72.82  6795.5   72.48  6809.3   72.78  7109.3   72.12  7133.3   72.43
  7205.3    72.6  7265.3   73.84  7289.3   72.61  7325.3   71.67  7349.3   73.29
  7373.3   73.08  7409.3   73.38  7433.3   73.56  7469.3   74.88  7505.3   74.58
  7529.3   74.69  7589.3    75.2  7601.3   76.27  7610.7   78.26
BR U #Mann= 6
  1305.8      .1  2407.6      .1 4906.51    .035 5090.01      .1    5315      .1
  5518.3     .99
BR U Banks=4906.51,5090.01
BR D #Sta/Elev= 119
  1305.8    77.5  1629.8   76.87  1677.8   76.86  1713.8   76.51  1785.8   75.52
  2013.8   76.56  2097.8   75.21  2157.8   75.77  2205.8   74.89  2325.8   74.33
  2373.8   74.78  2407.6   74.64  2433.8   74.53  2541.8   74.43  2601.8   75.67
  2649.8   75.77  2757.8   74.39  2949.8   74.13  3033.8   73.09  3057.8   72.86
  3081.8   74.36  3153.8   73.11  3213.8   73.31  3369.8   72.49  3405.8   73.11
  3561.8   72.49  3609.8   72.33  3669.8   72.35  3753.8   71.71  3933.8   71.37
  4017.8   70.97  4041.8   70.37  4173.8   70.64  4233.8   71.26  4317.8   71.37
  4341.8   70.86  4451.8   70.42  4619.8   70.09  4643.8   70.21  4703.8   70.07
  4784.7   69.93  4832.7   70.09 4850.91   69.91 4867.61   70.02 4882.81   70.11
 4899.51   70.16 4905.81   69.82 4906.51   69.78 4910.92   68.58 4911.01   68.56
 4927.31   64.14 4936.61   61.48 4939.71    60.6 4957.51   58.74 4969.01   53.82
 4970.31    52.2 4974.31   49.81 4980.11   50.23 4983.71   49.38 4995.71   48.71
 5020.31   49.79 5021.11   50.79 5029.71   52.14 5030.01   52.14 5033.31   54.29
 5040.31   56.54 5044.51   58.49 5060.01   60.88 5060.21   60.91  5082.1   68.91
 5082.21   68.95 5084.81    69.9 5086.61   70.24 5090.01   70.89 5099.71   71.27
 5110.61   71.05 5118.21   71.24 5125.91   71.61 5132.31   71.37 5139.51   71.41
  5161.5    70.5  5293.5   69.64    5315   70.19  5363.9   71.44  5483.9   71.88
  5507.9   70.67  5518.3   70.74  5531.9   70.83  5579.9   70.04  5639.9   70.04
  5807.9   69.98  5879.9    69.9  5939.9   69.47  6191.9   69.96  6215.9   70.89
  6255.5   71.69  6279.5   71.61  6315.5   72.54  6363.5   70.85  6423.5   71.78
  6591.5   72.82  6795.5   72.48  6809.3   72.78  7109.3   72.12  7133.3   72.43
  7205.3    72.6  7265.3   73.84  7289.3   72.61  7325.3   71.67  7349.3   73.29
  7373.3   73.08  7409.3   73.38  7433.3   73.56  7469.3   74.88  7505.3   74.58
  7529.3   74.69  7589.3    75.2  7601.3   76.27  7610.7   78.26
BR D #Mann= 6
  1305.8      .1  2407.6      .1 4906.51    .035 5090.01      .1    5315      .1
  5518.3     .99
BR D Banks=4906.51,5090.01
BC Design=,, 0 ,, 0 ,,,,,,
BC HTab HWMax=78.04
BC Use User HTab Curves=0
BC User HTab FreeFlow(D)= 0