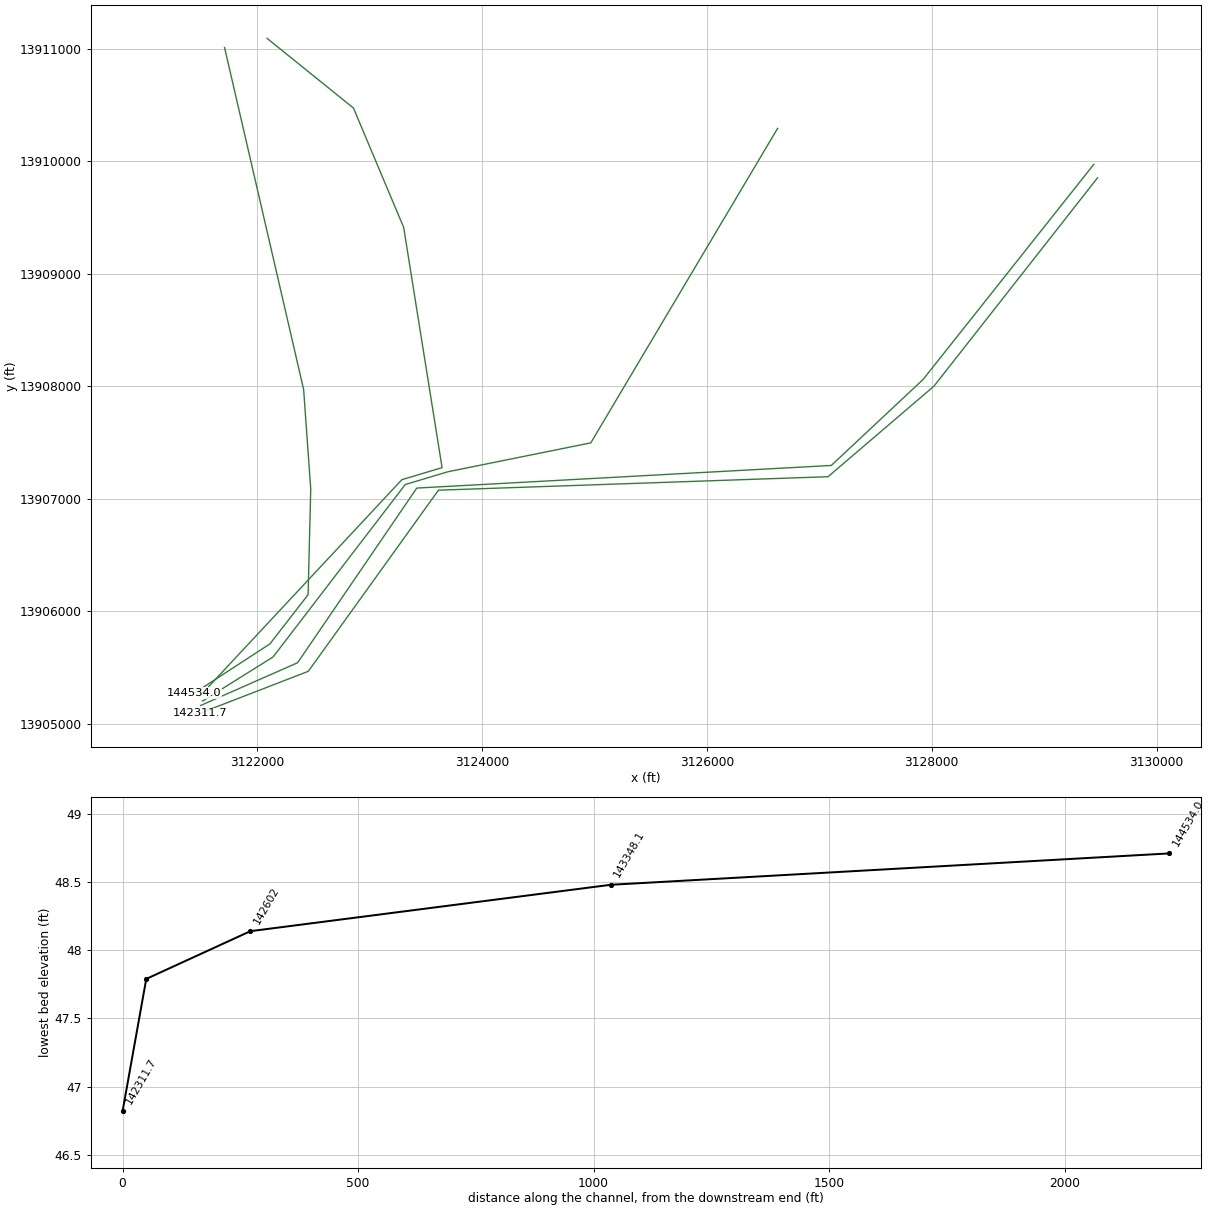
HEC-RAS study P100-00-00.prj: P100-00-00

--- P100-00-00.g01 (geometry) --- (continued)

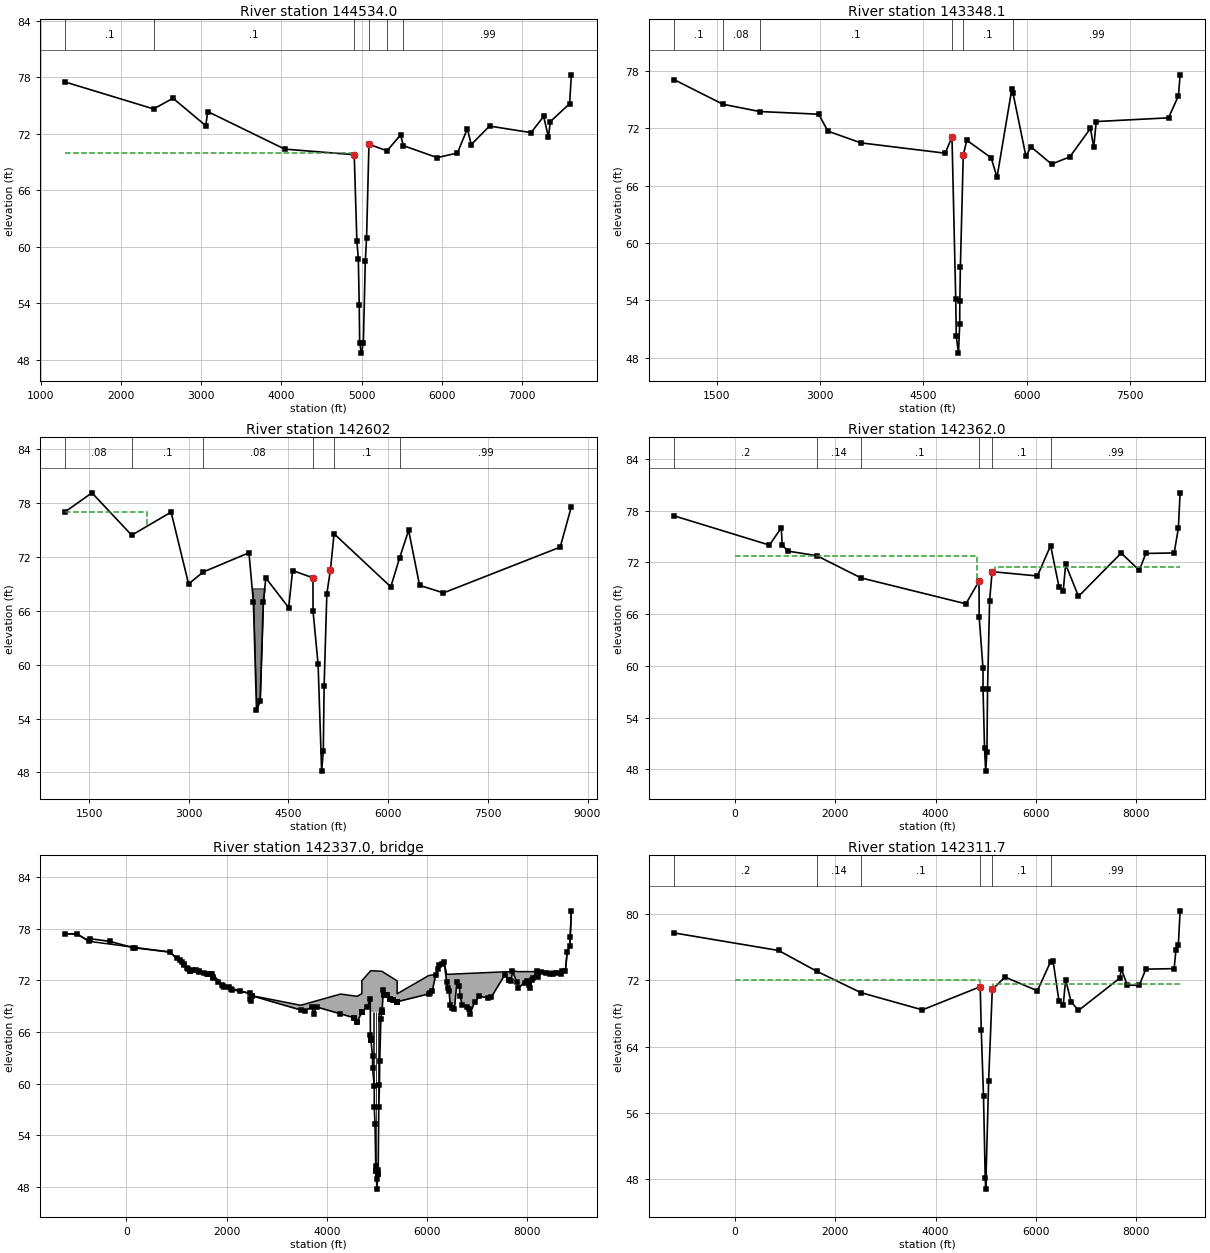
Type RM Length L Ch R = 1 ,144534.0,1185.9,1185.9,1185.9
BEGIN DESCRIPTION:
Downstream Section of Bridge/Culvert/Weir
END DESCRIPTION:
XS GIS Cut Line= 6
      3121711.37      13911013.1       3122414.7     13907971.35
      3122477.83     13907085.93      3122454.42     13906146.64
      3122115.04     13905709.02      3121443.34     13905271.93
#Sta/Elev= 30
  1305.8    77.5  2407.6   74.64  2649.8   75.77  3057.8   72.86  3081.8   74.36
  4041.8   70.37 4906.51   69.78 4939.71    60.6 4957.51   58.74 4969.01   53.82
 4974.31   49.81 4995.71   48.71 5020.31   49.79 5044.51   58.49 5060.21   60.91
 5090.01   70.89    5315   70.19  5483.9   71.88  5518.3   70.74  5939.9   69.47
  6191.9   69.96  6315.5   72.54  6363.5   70.85  6591.5   72.82  7109.3   72.12
  7265.3   73.84  7325.3   71.67  7349.3   73.29  7589.3    75.2  7610.7   78.26
#Mann= 6 , 1 , 0
  1305.8      .1       0  2407.6      .1       0 4906.51    .035       0
 5090.01      .1       0    5315      .1       0  5518.3     .99       0
#XS Ineff= 2 , 0
       0    4896      70    5100       0    70.6
Permanent Ineff=
       F       F
Bank Sta=4906.51,5090.01
XS Rating Curve= 0 ,0
Exp/Cntr=0.5,0.3

Type RM Length L Ch R = 1 ,143348.1,1802.3,765,44.06
BEGIN DESCRIPTION:
Cross Section 143348.1
END DESCRIPTION:
XS GIS Cut Line= 6
       3122089.4     13911094.33      3122857.81     13910474.21
      3123304.34     13909412.95      3123645.88     13907276.49
      3123288.26     13907169.26      3121489.97     13905243.19
#Sta/Elev= 30
   877.7   77.11  1590.3   74.52  2123.1   73.76  2981.1   73.48  3112.5   71.71
  3592.5   70.48  4815.4    69.4  4915.1   71.08  4969.4   54.18  4977.3   50.25
  5009.4   48.48  5027.1   51.48  5028.9   53.92  5036.8   57.47  5078.9   69.23
  5131.1   70.75  5483.5   68.92  5568.8   66.88  5784.8   76.15    5800   75.71
  5988.8   69.07  6060.8   70.07  6360.8   68.26  6624.8   69.01  6924.8   71.99
  6972.8   70.01  7008.8   72.71  8058.5    73.1  8202.5   75.41  8226.5    77.6
#Mann= 6 ,-1 , 0
   877.7      .1       0  1590.3     .08       0  2123.1      .1       0
  4915.1    .035       0  5078.9      .1       0    5800     .99       0
#XS Ineff= 2 , 0
       0    3500                       0
Permanent Ineff=
       F       F
Bank Sta=4915.1,5078.9
XS Rating Curve= 0 ,0
Exp/Cntr=0.3,0.1

Type RM Length L Ch R = 1 ,142602  ,520.9,221.1,12.74
XS GIS Cut Line= 6
      3126629.95   13910293.5943   3124968.49368    13907496.719
   3123698.02903   13907239.9275   3123318.38511   13907126.0934
   3122143.13417   13905592.9196   3121516.49271   13905200.8043
#Sta/Elev= 30
  1139.1   77.03 1542.84   79.15 2140.98   74.43    2734      77    2997      69
 3217.62   70.33 3905.48   72.47    3972      67    4019      55    4073      56
    4121      67 4159.69   69.66 4502.89   66.36 4562.28   70.49 4868.99   69.68
  4869.5   65.99  4945.9   60.05  4999.1   48.14  5024.1   50.37  5036.4   57.61
  5077.5   67.92 5131.47   70.55 5185.97   74.59 6039.92   68.67 6173.39   71.93
 6308.21   74.97 6472.98   68.84 6832.47      68  8588.5    73.1  8756.5    77.6
#Mann= 6 ,-1 , 0
  1139.1     .08       0 2140.98      .1       0 3217.62     .08       0
 4868.99    .035       0 5185.97      .1       0 6173.39     .99       0
#XS Ineff= 1 ,-1
       0    2369      77
Permanent Ineff=
       F
#Block Obstruct= 1 ,-1
    3940    4155    68.5
Bank Sta=4868.99,5131.47
XS Rating Curve= 0 ,0
Exp/Cntr=0.5,0.3

Type RM Length L Ch R = 1 ,142362.0,50.3,50.3,50.3
BEGIN DESCRIPTION:
Upstream Section of Bridge/Culvert/Weir
END DESCRIPTION:
XS GIS Cut Line= 6
      3129442.65     13909974.56      3127923.44     13908060.18
      3127107.41     13907295.87      3123420.73     13907094.61
      3122361.01     13905541.19       3121498.6     13905161.15
#Sta/Elev= 30
 -1218.4    77.4     688      74     923      76     942      74    1058    73.3
  1632.3   72.77  2510.6    70.2  4604.4   67.19  4865.7   69.81  4869.5   65.64
  4945.9    59.7  4946.5   57.29  4975.8   50.52  4999.1   47.79  5024.1   50.02
  5036.4   57.26  5077.5   67.57  5127.3   70.92  6030.2   70.42  6293.9   73.94
  6461.5   69.14  6545.5   68.71  6593.5   71.77  6849.7   68.05  7701.7   73.08
    8061   71.07    8193   73.03    8757   73.09    8841   75.95  8875.7   80.06
#Mann= 6 ,-1 , 0
 -1218.4      .2       0  1632.3     .14       0  2510.6      .1       0
  4865.7    .035       0  5127.3      .1       0  6293.9     .99       0
#XS Ineff= 2 , 0
       0    4823    72.7    5192       0    71.5
Permanent Ineff=
       F       F
Bank Sta=4865.7,5127.3
XS Rating Curve= 0 ,0
Exp/Cntr=0.5,0.3

Type RM Length L Ch R = 3 ,142337.0,,,
BEGIN DESCRIPTION:
SAM HOUSTON PARKWAY (HWY 8 WESTBOUND)
Structure ID: P00-40
END DESCRIPTION:
Bridge Culvert--1,0,-1,-1, 0
Deck Dist Width WeirC Skew NumUp NumDn MinLoCord MaxHiCord MaxSubmerge Is_Ogee
10,30,2.6,0, 60, 60, , , 0.95, 0, 1,1,,
 -1218.4  -978.4  -738.4   869.6  1265.6  1715.6  1955.6  2464.8  2488.8  2500.8
  3479.8  3700.8  3736.8  3796.8  4272.7  4604.4 4698.99  4699.1  4808.5  4865.7
  4869.5 4878.53  4878.6  5096.2  5127.3  5148.7  5402.3 5402.41  6030.2  6101.5
  6173.5  6245.5  6341.5  6389.5  6437.5  6461.5  6545.5  6593.5  6641.5  6653.5
  6701.5  6825.7  6849.7  7041.7  7281.7  7545.7  7677.7  7701.7  7821.7    8001
    8061    8085    8193    8217    8277    8757    8793    8841    8853  8875.7
   77.39   77.36   76.51   75.27   73.13   72.72   71.27   70.48   69.67   70.22
    69.1   69.46   69.52   69.62    70.4   70.14   70.45   71.95   72.67   73.04
   73.07   73.11   73.11   73.04   72.93   72.85   71.93   70.43   72.54   72.61
   72.65    73.8   74.07   72.69    72.7    72.7   72.72   72.74   72.75   72.75
   72.76    72.8    72.8   72.85   72.91   72.98      73   73.08      73      73
      73      73   73.03      73      73   73.08   75.33   75.94   76.96   80.05
   77.39   77.36   76.51   75.27   73.12   72.71   71.26   70.47   69.62   70.21
   68.55   68.91   68.11    68.9    68.1   67.18    68.3   68.31   68.93    69.8
   65.63   65.11   68.31   68.29   70.91   70.32   69.51   69.51   70.41   70.75
   72.64   73.79   74.06   71.79   70.77   69.13    68.7   71.76   71.36   70.19
    69.1   68.68   68.04   70.12   70.06   72.59   71.96   73.07    71.1   71.86
   71.06   72.06   73.02   72.33      73   73.08   75.33   75.94   76.96   80.05
 -1218.4  -978.4  -738.4   869.6  1265.6  1715.6  1955.6  2464.8  2488.8  2500.8
  3479.8  3700.8  3736.8  3796.8  4272.7  4604.4 4698.99  4699.1  4808.5  4865.7
  4869.5 4878.53  4878.6  5096.2  5127.3  5148.7  5402.3 5402.41  6030.2  6101.5
  6173.5  6245.5  6341.5  6389.5  6437.5  6461.5  6545.5  6593.5  6641.5  6653.5
  6701.5  6825.7  6849.7  7041.7  7281.7  7545.7  7677.7  7701.7  7821.7    8001
    8061    8085    8193    8217    8277    8757    8793    8841    8853  8875.7
   77.39   77.36   76.51   75.27   73.13   72.72   71.27   70.48   69.67   70.22
    69.1   69.46   69.52   69.62    70.4   70.14   70.45   71.95   72.67   73.04
   73.07   73.11   73.11   73.04   72.93   72.85   71.93   70.43   72.54   72.61
   72.65    73.8   74.07   72.69    72.7    72.7   72.72   72.74   72.75   72.75
   72.76    72.8    72.8   72.85   72.91   72.98      73   73.08      73      73
      73      73   73.03      73      73   73.08   75.33   75.94   76.96   80.05
   76.76   76.73   75.88   74.64   72.49   72.08   70.63   69.84   68.99   69.58
   67.92   68.28   67.48   68.27   67.47   66.55   67.67   67.68    68.3   69.17
      65   64.48   67.68   67.66   70.28   69.69   68.88   68.88   69.78   70.12
   72.01   73.16   73.43   71.16   70.14    68.5   68.07   71.13   70.73   69.56
   68.47   68.05   67.41   69.49   69.43   71.96   71.33   72.44   70.47   71.23
   70.43   71.43   72.39    71.7   72.37   72.45    74.7   75.31   76.33   79.42
Pier Skew, UpSta & Num, DnSta & Num=  ,4912.7, 2 ,4912.7, 2 , 0 , 0 , 0 ,,
     1.4     1.4
    60.8   69.37
     1.4     1.4
   60.17   68.74
Pier Skew, UpSta & Num, DnSta & Num=  ,4946.5, 2 ,4946.5, 2 , 0 , 0 , 0 ,,
     1.4     1.4
   56.18   69.43
     1.4     1.4
   55.55    68.8
Pier Skew, UpSta & Num, DnSta & Num=  ,4980.4, 2 ,4980.4, 2 , 0 , 0 , 0 ,,
     1.4     1.4
   48.89    69.5
     1.4     1.4
   48.26   68.87
Pier Skew, UpSta & Num, DnSta & Num=  ,5014.3, 2 ,5014.3, 2 , 0 , 0 , 0 ,,
     1.4     1.4
   48.42   69.53
     1.4     1.4
   47.79    68.9
Pier Skew, UpSta & Num, DnSta & Num=  ,5048.5, 2 ,5048.5, 2 , 0 , 0 , 0 ,,
     1.4     1.4
   58.73   69.41
     1.4     1.4
    58.1   68.78
Pier Skew, UpSta & Num, DnSta & Num=  ,5082.4, 2 ,5082.4, 2 , 0 , 0 , 0 ,,
     1.4     1.4
   66.72   69.31
     1.4     1.4
   66.09   68.68
BR Coef= 1 , 1 , 0 ,1.25, 0 ,,,0.8,0,2,0,
WSPro=,,,, 1 ,,,, 0 ,,,, 0 ,,,,-1 ,-1 ,-1 , 0 , 0 , 0 , 0 , 0
BR U #Sta/Elev= 151
 -1218.4   77.39  -978.4   77.36  -738.4   76.51  -726.4   76.82  -330.4   76.51
   137.6   75.78   173.6   75.75   869.6   75.27  1014.4   74.55  1064.4    74.3
  1104.4    74.1  1145.6   73.89  1154.4   73.81  1205.6   73.37  1224.4   73.29
  1265.6   73.12  1276.4   73.12  1336.4   73.15  1397.6   73.18  1446.4   73.03
  1451.6   73.01  1547.6   72.81  1606.4   72.78  1632.3   72.76  1696.4   72.72
  1715.6   72.71  1736.4   72.34  1739.6   72.28  1823.6   71.81  1916.4   71.42
  1931.3   71.36  1955.6   71.26  2039.6   71.24  2091.3   70.96  2099.6   70.92
  2260.6   70.72  2464.8   70.47  2476.8   69.88  2488.8   69.62  2500.8   70.21
  2510.6   70.19  3479.8   68.55  3556.8   68.42  3700.8   68.91  3736.8   68.11
  3796.8    68.9  4272.7    68.1  4536.6   67.66  4537.7   67.66  4602.5   67.19
  4604.4   67.18 4698.99    68.3  4699.1   68.31 4699.21   68.31  4700.5   68.32
  4704.5   68.37  4808.5   68.93  4865.7    69.8  4869.5   65.63  4877.3   65.18
  4878.3   65.13 4878.41   65.12 4878.53   65.11  4878.6   65.11  4912.6   63.17
  4912.7   61.85  4945.9   59.69  4946.5   57.28  4961.1   55.28  4975.8   50.51
  4980.4   49.89  4984.6   49.88  4999.1   47.78  5009.7   48.98  5014.3    49.5
  5016.8    49.5  5024.1   50.01  5036.4   57.25  5048.5   59.88  5054.6   62.65
  5077.5   67.56  5096.2   68.29 5096.29    68.3  5096.4    68.3  5103.3   68.57
  5127.3   70.91  5148.7   70.32  5148.8   70.32  5198.2   70.24  5198.5   70.24
  5263.2   69.88  5265.9   69.86  5324.1   69.68  5324.8   69.68    5392   69.51
  5395.1    69.5 5402.19   69.51  5402.3   69.51 5402.41   69.51  6030.2   70.41
  6049.5    70.5  6101.5   70.75  6173.5   72.64  6221.5    73.3  6245.5   73.79
  6293.9   73.93  6341.5   74.06  6389.5   71.79  6413.5   71.07  6437.5   70.77
  6461.5   69.13  6497.5   68.84  6545.5    68.7  6593.5   71.76  6641.5   71.36
  6653.5   70.19  6701.5    69.1  6785.5    68.9  6825.7   68.68  6849.7   68.04
  6945.7   69.43  7041.7   70.12  7209.7   69.98  7281.7   70.06  7545.7   72.59
  7629.7   72.01  7639.5      72  7677.7   71.96  7701.7   73.07  7785.7   71.81
  7821.7    71.1  7941.7   71.73    8001   71.86    8025   71.46    8061   71.06
    8085   72.06    8109   72.29    8193   73.02    8217   72.33    8277      73
    8361   72.79  8454.1   72.73    8505    72.7    8577   72.84    8661   72.76
    8685   73.07    8757   73.08    8793   75.33    8841   75.94    8853   76.96
  8875.7   80.05
BR U #Mann= 6
 -1218.4      .2  1632.3     .14  2510.6      .1  4865.7    .035  5127.3      .1
  6293.9     .99
BR U Banks=4865.7,5127.3
BR D #Sta/Elev= 151
 -1218.4   76.76  -978.4   76.73  -738.4   75.88  -726.4   76.19  -330.4   75.88
   137.6   75.15   173.6   75.12   869.6   74.64  1014.4   73.92  1064.4   73.67
  1104.4   73.47  1145.6   73.26  1154.4   73.18  1205.6   72.74  1224.4   72.66
  1265.6   72.49  1276.4   72.49  1336.4   72.52  1397.6   72.55  1446.4    72.4
  1451.6   72.38  1547.6   72.18  1606.4   72.15  1632.3   72.13  1696.4   72.09
  1715.6   72.08  1736.4   71.71  1739.6   71.65  1823.6   71.18  1916.4   70.79
  1931.3   70.73  1955.6   70.63  2039.6   70.61  2091.3   70.33  2099.6   70.29
  2260.6   70.09  2464.8   69.84  2476.8   69.25  2488.8   68.99  2500.8   69.58
  2510.6   69.56  3479.8   67.92  3556.8   67.79  3700.8   68.28  3736.8   67.48
  3796.8   68.27  4272.7   67.47  4536.6   67.03  4537.7   67.03  4602.5   66.56
  4604.4   66.55 4698.99   67.67  4699.1   67.68 4699.21   67.68  4700.5   67.69
  4704.5   67.74  4808.5    68.3  4865.7   69.17  4869.5      65  4877.3   64.55
  4878.3    64.5 4878.41   64.49 4878.53   64.48  4878.6   64.48  4912.6   62.54
  4912.7   61.22  4945.9   59.06  4946.5   56.65  4961.1   54.65  4975.8   49.88
  4980.4   49.26  4984.6   49.25  4999.1   47.15  5009.7   48.35  5014.3   48.87
  5016.8   48.87  5024.1   49.38  5036.4   56.62  5048.5   59.25  5054.6   62.02
  5077.5   66.93  5096.2   67.66 5096.29   67.67  5096.4   67.67  5103.3   67.94
  5127.3   70.28  5148.7   69.69  5148.8   69.69  5198.2   69.61  5198.5   69.61
  5263.2   69.25  5265.9   69.23  5324.1   69.05  5324.8   69.05    5392   68.88
  5395.1   68.87 5402.19   68.88  5402.3   68.88 5402.41   68.88  6030.2   69.78
  6049.5   69.87  6101.5   70.12  6173.5   72.01  6221.5   72.67  6245.5   73.16
  6293.9    73.3  6341.5   73.43  6389.5   71.16  6413.5   70.44  6437.5   70.14
  6461.5    68.5  6497.5   68.21  6545.5   68.07  6593.5   71.13  6641.5   70.73
  6653.5   69.56  6701.5   68.47  6785.5   68.27  6825.7   68.05  6849.7   67.41
  6945.7    68.8  7041.7   69.49  7209.7   69.35  7281.7   69.43  7545.7   71.96
  7629.7   71.38  7639.5   71.37  7677.7   71.33  7701.7   72.44  7785.7   71.18
  7821.7   70.47  7941.7    71.1    8001   71.23    8025   70.83    8061   70.43
    8085   71.43    8109   71.66    8193   72.39    8217    71.7    8277   72.37
    8361   72.16  8454.1    72.1    8505   72.07    8577   72.21    8661   72.13
    8685   72.44    8757   72.45    8793    74.7    8841   75.31    8853   76.33
  8875.7   79.42
BR D #Mann= 6
 -1218.4      .2  1632.3     .14  2510.6      .1  4865.7    .035  5127.3      .1
  6293.9     .99
BR D Banks=4865.7,5127.3
BC Design=,, 0 ,, 0 ,,,,,,
BC HTab HWMax=80.06
BC Use User HTab Curves=0
BC User HTab FreeFlow(D)= 0

Type RM Length L Ch R = 1 ,142311.7,163,163,163
BEGIN DESCRIPTION:
Upstream Section of Bridge/Culvert/Weir
END DESCRIPTION:
XS GIS Cut Line= 6
      3129474.79     13909853.35      3128020.49     13908001.12
      3127078.49     13907195.74      3123613.71     13907075.93
      3122456.47     13905465.22      3121489.52       13905091.
#Sta/Elev= 30
 -1218.4   77.71   869.6   75.59  1632.3   73.08  2510.6   70.51  3736.8   68.43
  4890.4   71.22  4910.8   66.01  4955.6   58.05    4990   48.11  4999.7   46.82
  5057.9   59.87  5130.9    70.9  5385.6   72.38  6030.2   70.73  6293.9   74.25
  6341.5   74.38  6461.5   69.45  6545.5   69.02  6593.5   72.08  6701.5   69.42
  6849.7   68.36  7677.7   72.28  7701.7   73.39  7821.7   71.42    8061   71.38
    8193   73.34    8757    73.4    8793   75.65    8841   76.26  8875.7   80.37
#Mann= 6 , 1 , 0
 -1218.4      .2       0  1632.3     .14       0  2510.6      .1       0
  4890.4    .035       0  5130.9      .1       0  6293.9     .99       0
#XS Ineff= 2 , 0
       0    4876      72    5139       0    71.5
Permanent Ineff=
       F       F
Bank Sta=4890.4,5130.9
XS Rating Curve= 0 ,0
Exp/Cntr=0.5,0.3