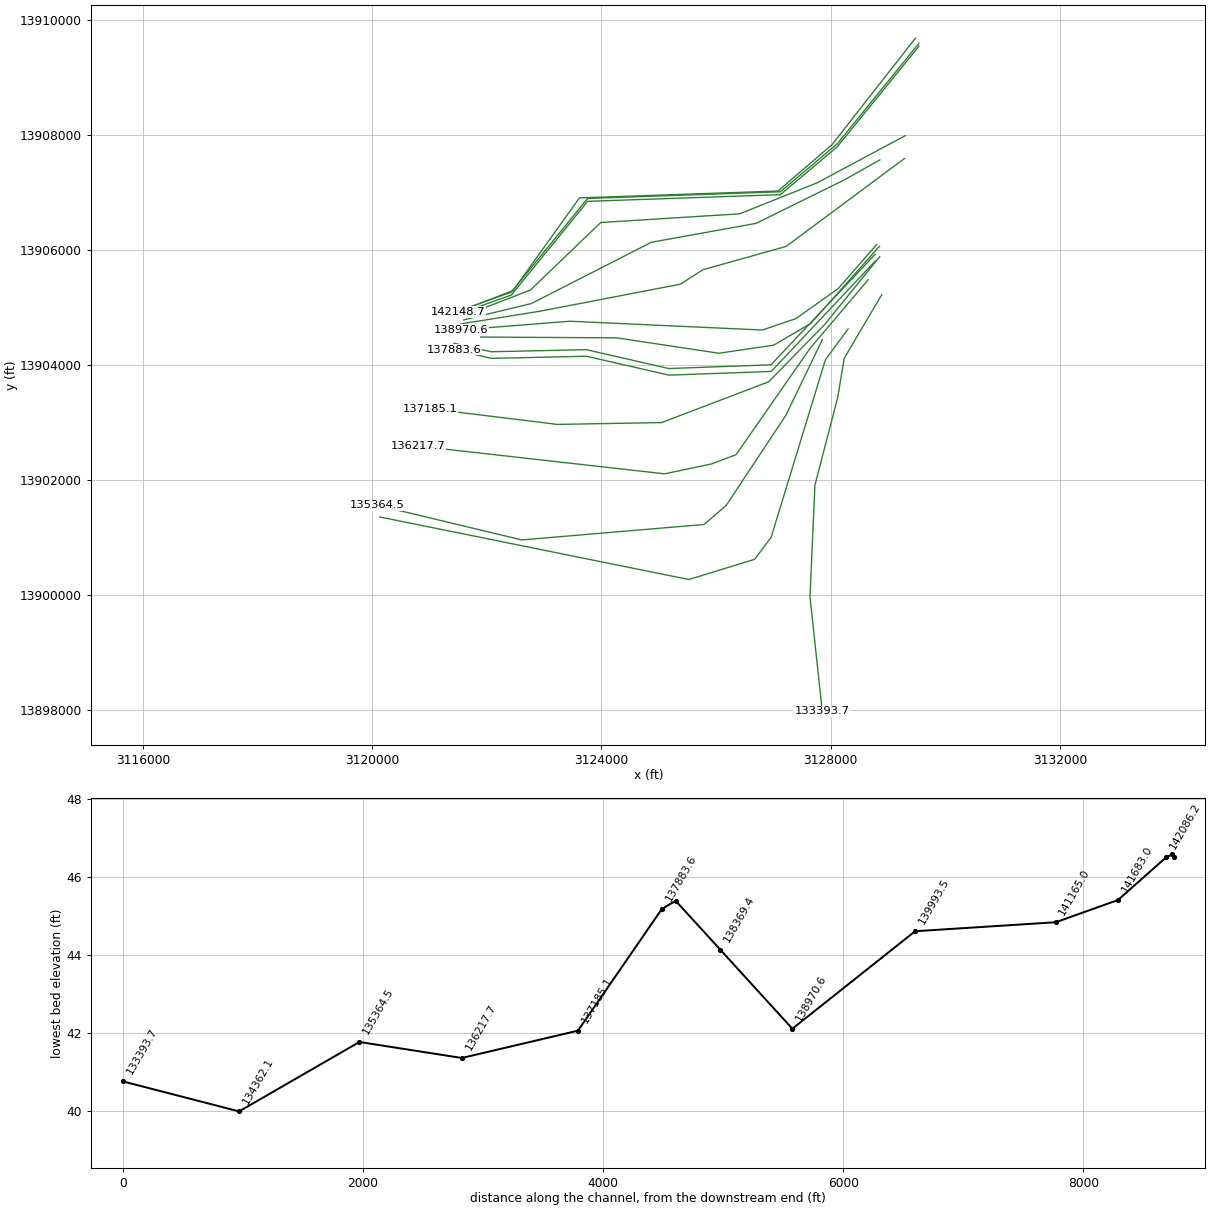
HEC-RAS study P100-00-00.prj: P100-00-00

--- P100-00-00.g01 (geometry) --- (continued)

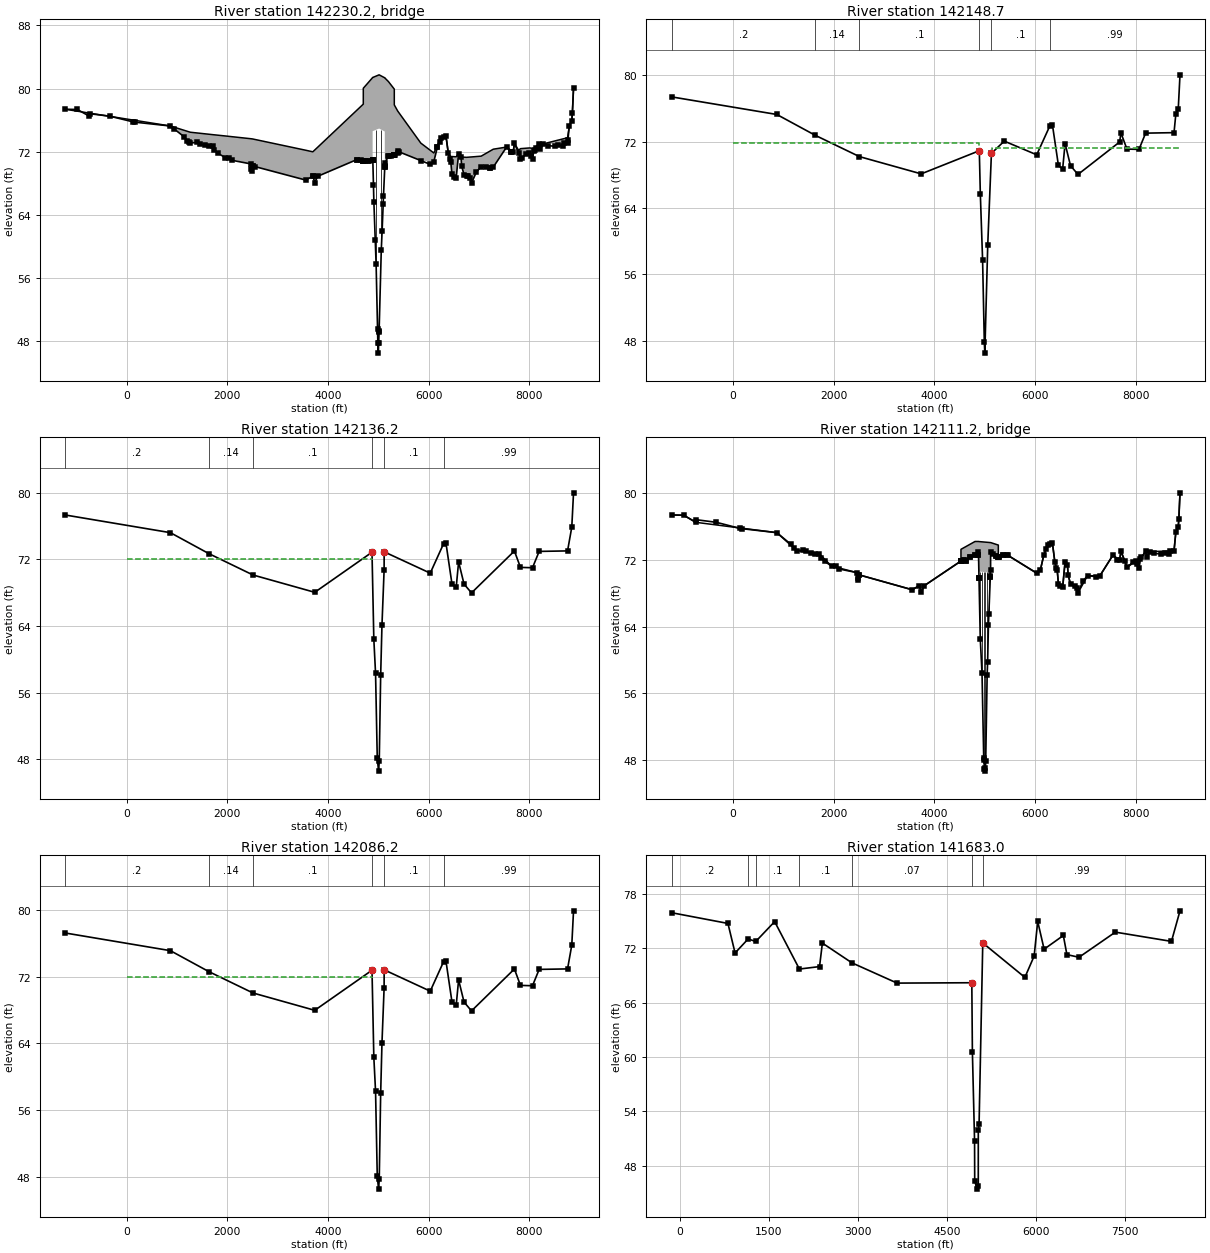
Type RM Length L Ch R = 3 ,142230.2,,,
BEGIN DESCRIPTION:
HIGHWAY 8
Structure ID: P00-39
END DESCRIPTION:
Bridge Culvert--1,0,-1,-1, 0
Deck Dist Width WeirC Skew NumUp NumDn MinLoCord MaxHiCord MaxSubmerge Is_Ogee
10,143,2.6,0, 60, 60, , , 0.95, 0, 1,1,,
 -1218.4   869.6  1265.6  1715.6  1955.6  2464.8  2488.8  2500.8  3556.8  3698.2
  3736.8  3796.8  4571.5  4700.8 4700.89    4701 4886.11  4886.2  4886.3  5014.9
  5127.7 5127.79  5127.9  5199.7  5316.5 5316.61  5385.6  5843.4  6101.5  6245.5
  6341.5  6389.5  6437.5  6461.5  6545.5  6593.5  6641.5  6653.5  6701.5  6752.4
  6825.7  6849.7  7041.7  7281.7  7545.7  7677.7  7701.7  7785.7  7821.7    8001
    8061    8085    8193    8217    8277    8757    8793    8841    8853  8875.7
   77.39   75.27   74.48   74.17   74.01   73.66   73.64   73.63    72.2      72
   72.23   72.59   77.26   78.04   78.05   80.05    81.4    81.4   81.41   81.75
   81.37   81.36   81.36    80.9   79.94   77.94   77.15    73.1   71.85    73.8
   74.07    71.8   71.41    71.4   71.37   71.77   71.37   71.33   71.32    71.3
   71.34   71.35   71.45   72.33    72.6   71.97   73.08   72.18    72.4   72.49
   72.45   72.43   73.03    72.6   73.01   73.78   75.33   75.94   76.96   80.05
   77.39   75.27   73.12   72.71   71.26   70.47   69.62   70.21   68.42    68.9
   68.11    68.9   71.01   70.86   70.86   70.86    70.9    74.6   74.61   74.95
   74.57   74.56   70.15   71.44   71.64   71.64   72.06   70.89   70.75   73.79
   74.06   71.79   70.77   69.13    68.7   71.76   71.36   70.19    69.1   68.98
   68.68   68.04   70.12   70.06   72.59   71.96   73.07   71.81    71.1   71.86
   71.06   72.06   73.02   72.33      73   73.08   75.33   75.94   76.96   80.05
 -1218.4   869.6  1265.6  1715.6  1955.6  2464.8  2488.8  2500.8  3556.8  3698.2
  3736.8  3796.8  4571.5  4700.8 4700.89    4701 4886.11  4886.2  4886.3  5014.9
  5127.7 5127.79  5127.9  5199.7  5316.5 5316.61  5385.6  5843.4  6101.5  6245.5
  6341.5  6389.5  6437.5  6461.5  6545.5  6593.5  6641.5  6653.5  6701.5  6752.4
  6825.7  6849.7  7041.7  7281.7  7545.7  7677.7  7701.7  7785.7  7821.7    8001
    8061    8085    8193    8217    8277    8757    8793    8841    8853  8875.7
   77.39   75.27   74.48   74.17   74.01   73.66   73.64   73.63    72.2      72
   72.23   72.59   77.26   78.04   78.05   80.05    81.4    81.4   81.41   81.75
   81.37   81.36   81.36    80.9   79.94   77.94   77.15    73.1   71.85    73.8
   74.07    71.8   71.41    71.4   71.37   71.77   71.37   71.33   71.32    71.3
   71.34   71.35   71.45   72.33    72.6   71.97   73.08   72.18    72.4   72.49
   72.45   72.43   73.03    72.6   73.01   73.78   75.33   75.94   76.96   80.05
   77.35   75.23   73.08   72.67   71.22   70.43   69.58   70.17   68.38   68.86
   68.07   68.86   70.97   70.82   70.82   70.82   70.86   74.56   74.57   74.91
   74.53   74.52   70.11    71.4    71.6    71.6   72.02   70.85   70.71   73.75
   74.02   71.75   70.73   69.09   68.66   71.72   71.32   70.15   69.06   68.94
   68.64      68   70.08   70.02   72.55   71.92   73.03   71.77   71.06   71.82
   71.02   72.02   72.98   72.29   72.96   73.04   75.29    75.9   76.92   80.01
Pier Skew, UpSta & Num, DnSta & Num=  ,4955.6, 2 ,4955.6, 2 , 0 , 0 , 0 ,,
       3       3
   56.32   75.82
       3       3
   56.28   75.78
Pier Skew, UpSta & Num, DnSta & Num=  ,5057.9, 2 ,5057.9, 2 , 0 , 0 , 0 ,,
       3       3
   58.19   75.85
       3       3
   58.15   75.81
BR Coef= 1 , 1 , 0 ,1.25, 0 ,,,0.8,-1,2,0,
WSPro=,,,, 1 ,,,, 0 ,,,, 0 ,,,,-1 ,-1 ,-1 , 0 , 0 , 0 , 0 , 0
BR U #Sta/Elev= 135
 -1218.4   77.39  -978.4   77.36  -738.4   76.51  -726.4   76.82  -330.4   76.51
   137.6   75.78   173.6   75.75   869.6   75.27   948.2   74.88  1145.6   73.89
  1205.6   73.37  1236.6   73.24  1265.6   73.12  1397.6   73.18  1451.6   73.01
  1547.6   72.81  1632.3   72.76  1715.6   72.71  1739.6   72.28  1823.6   71.81
  1955.6   71.26  2039.6   71.24  2099.6   70.92  2464.8   70.47  2476.8   69.88
  2488.8   69.62  2500.8   70.21  2510.6   70.19  2548.2   70.13  3556.8   68.42
  3698.2    68.9  3700.8   68.91  3736.8   68.11  3796.8    68.9  4571.5   71.01
  4577.1   70.95  4659.4    70.9  4700.8   70.86 4700.89   70.86    4701   70.86
 4701.11   70.86  4730.7   70.83  4788.7   70.86  4819.5   70.88 4886.11    70.9
  4886.2    70.9  4886.3    70.9  4890.4    70.9  4902.6   67.78  4910.8   65.69
  4938.6   60.86  4955.6   57.73  4985.8   49.51    4990   47.79  4999.7    46.5
  5007.3   47.84  5014.1   49.12  5014.9   49.31  5057.9   59.55  5074.9   61.99
  5095.8   65.41  5101.9   66.41  5127.7   70.12 5127.79   70.13  5127.9   70.15
  5130.9   70.58  5199.7   71.44  5208.1   71.45  5250.2   71.52  5304.8   71.62
 5316.39   71.64  5316.5   71.64 5316.61   71.64    5324   71.65  5384.2   71.82
  5385.6   72.06  5411.9   71.99  5843.4   70.89  6030.2   70.41  6101.5   70.75
  6173.4   72.64  6173.5   72.64  6221.5    73.3  6245.5   73.79  6293.9   73.93
  6341.5   74.06  6389.5   71.79  6413.5   71.07  6437.5   70.77  6461.5   69.13
  6497.5   68.84  6545.5    68.7  6593.5   71.76  6641.5   71.36  6653.5   70.19
  6701.5    69.1  6752.4   68.98  6785.5    68.9  6825.7   68.68  6849.7   68.04
  6945.7   69.43  7041.7   70.12  7142.4   70.04  7209.7   69.98  7222.4   69.99
  7281.7   70.06  7545.7   72.59  7629.7   72.01  7642.4      72  7677.7   71.96
  7701.7   73.07  7785.7   71.81  7821.7    71.1    7854   71.27  7941.7   71.73
    8001   71.86    8025   71.46    8061   71.06    8085   72.06    8109   72.29
    8124   72.42    8193   73.02    8217   72.33    8277      73    8361   72.79
    8505    72.7    8577   72.84    8661   72.76    8685   73.07    8757   73.08
    8764   73.52    8793   75.33    8841   75.94    8853   76.96  8875.7   80.05
BR U #Mann= 6
 -1218.4      .2  1632.3     .14  2510.6      .1  4890.4    .035  5130.9      .1
  6293.9     .99
BR U Banks=4890.4,5130.9
BR D #Sta/Elev= 135
 -1218.4   77.35  -978.4   77.32  -738.4   76.47  -726.4   76.78  -330.4   76.47
   137.6   75.74   173.6   75.71   869.6   75.23   948.2   74.84  1145.6   73.85
  1205.6   73.33  1236.6    73.2  1265.6   73.08  1397.6   73.14  1451.6   72.97
  1547.6   72.77  1632.3   72.72  1715.6   72.67  1739.6   72.24  1823.6   71.77
  1955.6   71.22  2039.6    71.2  2099.6   70.88  2464.8   70.43  2476.8   69.84
  2488.8   69.58  2500.8   70.17  2510.6   70.15  2548.2   70.09  3556.8   68.38
  3698.2   68.86  3700.8   68.87  3736.8   68.07  3796.8   68.86  4571.5   70.97
  4577.1   70.91  4659.4   70.86  4700.8   70.82 4700.89   70.82    4701   70.82
 4701.11   70.82  4730.7   70.79  4788.7   70.82  4819.5   70.84 4886.11   70.86
  4886.2   70.86  4886.3   70.86  4890.4   70.86  4902.6   67.74  4910.8   65.65
  4938.6   60.82  4955.6   57.69  4985.8   49.47    4990   47.75  4999.7   46.46
  5007.3    47.8  5014.1   49.08  5014.9   49.27  5057.9   59.51  5074.9   61.95
  5095.8   65.37  5101.9   66.37  5127.7   70.08 5127.79   70.09  5127.9   70.11
  5130.9   70.54  5199.7    71.4  5208.1   71.41  5250.2   71.48  5304.8   71.58
 5316.39    71.6  5316.5    71.6 5316.61    71.6    5324   71.61  5384.2   71.78
  5385.6   72.02  5411.9   71.95  5843.4   70.85  6030.2   70.37  6101.5   70.71
  6173.4    72.6  6173.5    72.6  6221.5   73.26  6245.5   73.75  6293.9   73.89
  6341.5   74.02  6389.5   71.75  6413.5   71.03  6437.5   70.73  6461.5   69.09
  6497.5    68.8  6545.5   68.66  6593.5   71.72  6641.5   71.32  6653.5   70.15
  6701.5   69.06  6752.4   68.94  6785.5   68.86  6825.7   68.64  6849.7      68
  6945.7   69.39  7041.7   70.08  7142.4      70  7209.7   69.94  7222.4   69.95
  7281.7   70.02  7545.7   72.55  7629.7   71.97  7642.4   71.96  7677.7   71.92
  7701.7   73.03  7785.7   71.77  7821.7   71.06    7854   71.23  7941.7   71.69
    8001   71.82    8025   71.42    8061   71.02    8085   72.02    8109   72.25
    8124   72.38    8193   72.98    8217   72.29    8277   72.96    8361   72.75
    8505   72.66    8577    72.8    8661   72.72    8685   73.03    8757   73.04
    8764   73.48    8793   75.29    8841    75.9    8853   76.92  8875.7   80.01
BR D #Mann= 6
 -1218.4      .2  1632.3     .14  2510.6      .1  4890.4    .035  5130.9      .1
  6293.9     .99
BR D Banks=4890.4,5130.9
BC Design=,, 0 ,, 0 ,,,,,,
BC HTab HWMax=80.37
BC Use User HTab Curves=0
BC User HTab FreeFlow(D)= 0

Type RM Length L Ch R = 1 ,142148.7,12.5,12.5,12.5
BEGIN DESCRIPTION:
Downstream Section of Bridge/Culvert/Weir
END DESCRIPTION:
XS GIS Cut Line= 6
      3129477.44     13909690.38      3128023.13     13907838.14
      3127081.13     13907032.76      3123616.35     13906912.95
      3122459.11     13905302.24      3121492.17     13904928.02
#Sta/Elev= 30
 -1218.4   77.41   869.6   75.29  1632.3   72.78  2510.6   70.21  3736.8   68.13
  4890.4   70.92  4910.8   65.71  4955.6   57.75    4990   47.81  4999.7   46.52
  5057.9   59.57  5130.9    70.6  5385.6   72.08  6030.2   70.43  6293.9   73.95
  6341.5   74.08  6461.5   69.15  6545.5   68.72  6593.5   71.78  6701.5   69.12
  6849.7   68.06  7677.7   71.98  7701.7   73.09  7821.7   71.12    8061   71.08
    8193   73.04    8757    73.1    8793   75.35    8841   75.96  8875.7   80.07
#Mann= 6 , 1 , 0
 -1218.4      .2       0  1632.3     .14       0  2510.6      .1       0
  4890.4    .035       0  5130.9      .1       0  6293.9     .99       0
#XS Ineff= 2 , 0
       0    4876    71.8    5139       0    71.3
Permanent Ineff=
       F       F
Bank Sta=4890.4,5130.9
XS Rating Curve= 0 ,0
Exp/Cntr=0.5,0.3

Type RM Length L Ch R = 1 ,142136.2,50,50,50
BEGIN DESCRIPTION:
Upstream Section of Bridge/Culvert/Weir
END DESCRIPTION:
XS GIS Cut Line= 6
      3129540.37     13909601.74      3128113.66     13907851.85
      3127121.83     13907019.44      3123759.55      13906903.5
      3122426.24     13905273.08      3121425.29     13904917.18
#Sta/Elev= 30
 -1218.4   77.33   869.6   75.21  1632.3    72.7  2510.6   70.13  3736.8   68.05
  4873.8   72.86    4910   62.42  4944.3   58.33  4978.4   48.12  5004.7   46.59
  5017.5   47.77  5046.1   58.14  5071.6   64.11  5114.2   70.73  5115.3   72.91
  6030.2   70.35  6293.9   73.87  6341.5      74  6461.5   69.07  6545.5   68.64
  6593.5    71.7  6701.5   69.04  6849.7   67.98  7701.7   73.01  7821.7   71.04
    8061      71    8193   72.96    8757   73.02    8841   75.88  8875.7   79.99
#Mann= 6 , 1 , 0
 -1218.4      .2       0  1632.3     .14       0  2510.6      .1       0
  4873.8    .035       0  5115.3      .1       0  6293.9     .99       0
#XS Ineff= 2 , 0
       0    4877      72    5115       0    70.8
Permanent Ineff=
       F       F
Bank Sta=4873.8,5115.3
XS Rating Curve= 0 ,0
Exp/Cntr=0.5,0.3

Type RM Length L Ch R = 3 ,142111.2,,,
BEGIN DESCRIPTION:
SAM HOUSTON PARKWAY (HWY 8 EASTBOUND)
Structure ID: P00-38
END DESCRIPTION:
Bridge Culvert--1,0,-1,-1, 0
Deck Dist Width WeirC Skew NumUp NumDn MinLoCord MaxHiCord MaxSubmerge Is_Ogee
10,30,2.6,0, 60, 60, , , 0.95, 0, 1,1,,
 -1218.4  -978.4  -738.4   869.6  1265.6  1715.6  1955.6  2464.8  2488.8  2500.8
  3556.8  3700.8  3736.8  3796.8  4524.9 4526.09  4526.2  4805.1  4873.8 4884.41
  4884.5 5109.09  5109.2  5114.2  5115.3  5268.1 5268.21  5451.7  6030.2  6101.5
  6173.5  6245.5  6341.5  6389.5  6437.5  6461.5  6545.5  6593.5  6641.5  6653.5
  6701.5  6825.7  6849.7  7041.7  7281.7  7545.7  7677.7  7701.7  7821.7    8001
    8061    8085    8193    8217    8277    8757    8793    8841    8853  8875.7
   77.39   77.36   76.51   75.27   73.12   72.71   71.26   70.47   69.62   70.21
   68.42   68.91   68.11    68.9   71.86   71.87   73.27   74.21   74.21    74.2
    74.2   74.08   74.08   74.08   74.08   73.78   72.37   72.57   70.41   70.75
   72.64   73.79   74.06   71.79   70.77   69.13    68.7   71.76   71.36   70.19
    69.1   68.68   68.04   70.12   70.06   72.59   71.96   73.07    71.1   71.86
   71.06   72.06   73.02   72.33      73   73.08   75.33   75.94   76.96   80.05
   77.39   77.36   76.51   75.27   73.12   72.71   71.26   70.47   69.62   70.21
   68.42   68.91   68.11    68.9   71.86   71.86   71.86   72.53   72.92   69.86
    70.6   70.48   70.02   70.79   72.97   72.36   72.36   72.57   70.41   70.75
   72.64   73.79   74.06   71.79   70.77   69.13    68.7   71.76   71.36   70.19
    69.1   68.68   68.04   70.12   70.06   72.59   71.96   73.07    71.1   71.86
   71.06   72.06   73.02   72.33      73   73.08   75.33   75.94   76.96   80.05
 -1218.4  -978.4  -738.4   869.6  1265.6  1715.6  1955.6  2464.8  2488.8  2500.8
  3556.8  3700.8  3736.8  3796.8  4524.9 4526.09  4526.2  4805.1  4873.8 4884.41
  4884.5 5109.09  5109.2  5114.2  5115.3  5268.1 5268.21  5451.7  6030.2  6101.5
  6173.5  6245.5  6341.5  6389.5  6437.5  6461.5  6545.5  6593.5  6641.5  6653.5
  6701.5  6825.7  6849.7  7041.7  7281.7  7545.7  7677.7  7701.7  7821.7    8001
    8061    8085    8193    8217    8277    8757    8793    8841    8853  8875.7
   77.39   77.36   76.51   75.27   73.12   72.71   71.26   70.47   69.62   70.21
   68.42   68.91   68.11    68.9   71.86   71.87   73.27   74.21   74.21    74.2
    74.2   74.08   74.08   74.08   74.08   73.78   72.37   72.57   70.41   70.75
   72.64   73.79   74.06   71.79   70.77   69.13    68.7   71.76   71.36   70.19
    69.1   68.68   68.04   70.12   70.06   72.59   71.96   73.07    71.1   71.86
   71.06   72.06   73.02   72.33      73   73.08   75.33   75.94   76.96   80.05
   77.29   77.26   76.41   75.17   73.02   72.61   71.16   70.37   69.52   70.11
   68.32   68.81   68.01    68.8   71.76   71.76   71.76   72.43   72.82   69.76
    70.5   70.38   69.92   70.69   72.87   72.26   72.26   72.47   70.31   70.65
   72.54   73.69   73.96   71.69   70.67   69.03    68.6   71.66   71.26   70.09
      69   68.58   67.94   70.02   69.96   72.49   71.86   72.97      71   71.76
   70.96   71.96   72.92   72.23    72.9   72.98   75.23   75.84   76.86   79.95
Pier Skew, UpSta & Num, DnSta & Num=  ,4910, 2 ,4910, 2 , 0 , 0 , 0 ,,
       2       2
   61.36   71.59
       2       2
   61.26   71.49
Pier Skew, UpSta & Num, DnSta & Num=  ,4944.3, 2 ,4944.3, 2 , 0 , 0 , 0 ,,
       2       2
   57.09   71.57
       2       2
   56.99   71.47
Pier Skew, UpSta & Num, DnSta & Num=  ,4978.4, 2 ,4978.4, 2 , 0 , 0 , 0 ,,
       2       2
   47.14   71.55
       2       2
   47.04   71.45
Pier Skew, UpSta & Num, DnSta & Num=  ,5012.1, 2 ,5012.1, 2 , 0 , 0 , 0 ,,
       2       2
      46   71.53
       2       2
    45.9   71.43
Pier Skew, UpSta & Num, DnSta & Num=  ,5046.1, 2 ,5046.1, 2 , 0 , 0 , 0 ,,
       2       2
   56.84   71.52
       2       2
   56.74   71.42
Pier Skew, UpSta & Num, DnSta & Num=  ,5080, 2 ,5080, 2 , 0 , 0 , 0 ,,
       2       2
   64.36    71.5
       2       2
   64.26    71.4
BR Coef= 1 , 1 , 0 ,1.25, 0 ,,,0.8,0,2,0,
WSPro=,,,, 1 ,,,, 0 ,,,, 0 ,,,,-1 ,-1 ,-1 , 0 , 0 , 0 , 0 , 0
BR U #Sta/Elev= 127
 -1218.4   77.39  -978.4   77.36  -738.4   76.51  -726.4   76.82  -330.4   76.51
   137.6   75.78   173.6   75.75   869.6   75.27  1145.6   73.89  1205.6   73.37
  1265.6   73.12  1397.6   73.18  1451.6   73.01  1547.6   72.81  1632.3   72.76
  1715.6   72.71  1739.6   72.28  1823.6   71.81  1955.6   71.26  2039.6   71.24
  2099.6   70.92  2464.8   70.47  2476.8   69.88  2488.8   69.62  2500.8   70.21
  2510.6   70.19  3556.8   68.42  3700.8   68.91  3736.8   68.11  3796.8    68.9
  4524.9   71.86  4525.4   71.86 4526.09   71.86  4526.2   71.86 4526.31   71.86
    4579   71.94  4579.2   71.94  4621.7   71.92  4625.4   71.92  4712.1   72.37
  4714.4   72.37  4805.1   72.53  4805.8   72.53  4864.8    72.6  4865.3   72.62
  4873.8   72.92 4884.41   69.86  4884.5   69.83  4884.6   69.81    4910   62.48
  4944.3   58.39  4978.4   48.18  4982.5   48.01  4992.5   46.94  5004.7   46.65
  5012.1   47.05  5017.5   47.83  5046.1    58.2  5055.7   59.76  5071.6   64.17
    5080   65.52 5108.97   69.98 5109.09      70  5109.2   70.02  5114.2   70.79
  5115.3   72.97    5170   72.67  5213.2   72.51  5215.3    72.5 5267.99   72.36
  5268.1   72.36 5268.21   72.36    5275   72.35    5281   72.33  5351.7   72.56
  5355.3   72.56  5449.9   72.57  5451.7   72.57  6030.2   70.41  6101.5   70.75
  6173.5   72.64  6221.5    73.3  6245.5   73.79  6293.9   73.93  6341.5   74.06
  6389.5   71.79  6413.5   71.07  6437.5   70.77  6461.5   69.13  6497.5   68.84
  6545.5    68.7  6593.5   71.76  6641.5   71.36  6653.5   70.19  6701.5    69.1
  6785.5    68.9  6825.7   68.68  6849.7   68.04  6945.7   69.43  7041.7   70.12
  7209.7   69.98  7281.7   70.06  7545.7   72.59  7629.7   72.01  7677.7   71.96
  7701.7   73.07  7785.7   71.81  7821.7    71.1  7941.7   71.73    8001   71.86
    8025   71.46    8061   71.06    8085   72.06    8109   72.29    8193   73.02
    8217   72.33    8277      73    8361   72.79    8505    72.7    8577   72.84
    8661   72.76    8685   73.07    8757   73.08    8793   75.33    8841   75.94
    8853   76.96  8875.7   80.05
BR U #Mann= 6
 -1218.4      .2  1632.3     .14  2510.6      .1  4873.8    .035  5115.3      .1
  6293.9     .99
BR U Banks=4873.8,5115.3
BR D #Sta/Elev= 127
 -1218.4   77.29  -978.4   77.26  -738.4   76.41  -726.4   76.72  -330.4   76.41
   137.6   75.68   173.6   75.65   869.6   75.17  1145.6   73.79  1205.6   73.27
  1265.6   73.02  1397.6   73.08  1451.6   72.91  1547.6   72.71  1632.3   72.66
  1715.6   72.61  1739.6   72.18  1823.6   71.71  1955.6   71.16  2039.6   71.14
  2099.6   70.82  2464.8   70.37  2476.8   69.78  2488.8   69.52  2500.8   70.11
  2510.6   70.09  3556.8   68.32  3700.8   68.81  3736.8   68.01  3796.8    68.8
  4524.9   71.76  4525.4   71.76 4526.09   71.76  4526.2   71.76 4526.31   71.76
    4579   71.84  4579.2   71.84  4621.7   71.82  4625.4   71.82  4712.1   72.27
  4714.4   72.27  4805.1   72.43  4805.8   72.43  4864.8    72.5  4865.3   72.52
  4873.8   72.82 4884.41   69.76  4884.5   69.73  4884.6   69.71    4910   62.38
  4944.3   58.29  4978.4   48.08  4982.5   47.91  4992.5   46.84  5004.7   46.55
  5012.1   46.95  5017.5   47.73  5046.1    58.1  5055.7   59.66  5071.6   64.07
    5080   65.42 5108.97   69.88 5109.09    69.9  5109.2   69.92  5114.2   70.69
  5115.3   72.87    5170   72.57  5213.2   72.41  5215.3    72.4 5267.99   72.26
  5268.1   72.26 5268.21   72.26    5275   72.25    5281   72.23  5351.7   72.46
  5355.3   72.46  5449.9   72.47  5451.7   72.47  6030.2   70.31  6101.5   70.65
  6173.5   72.54  6221.5    73.2  6245.5   73.69  6293.9   73.83  6341.5   73.96
  6389.5   71.69  6413.5   70.97  6437.5   70.67  6461.5   69.03  6497.5   68.74
  6545.5    68.6  6593.5   71.66  6641.5   71.26  6653.5   70.09  6701.5      69
  6785.5    68.8  6825.7   68.58  6849.7   67.94  6945.7   69.33  7041.7   70.02
  7209.7   69.88  7281.7   69.96  7545.7   72.49  7629.7   71.91  7677.7   71.86
  7701.7   72.97  7785.7   71.71  7821.7      71  7941.7   71.63    8001   71.76
    8025   71.36    8061   70.96    8085   71.96    8109   72.19    8193   72.92
    8217   72.23    8277    72.9    8361   72.69    8505    72.6    8577   72.74
    8661   72.66    8685   72.97    8757   72.98    8793   75.23    8841   75.84
    8853   76.86  8875.7   79.95
BR D #Mann= 6
 -1218.4      .2  1632.3     .14  2510.6      .1  4873.8    .035  5115.3      .1
  6293.9     .99
BR D Banks=4873.8,5115.3
BC Design=,, 0 ,, 0 ,,,,,,
BC HTab HWMax=79.99
BC Use User HTab Curves=0
BC User HTab FreeFlow(D)= 0

Type RM Length L Ch R = 1 ,142086.2,403.2,403.2,403.2
BEGIN DESCRIPTION:
Downstream Section of Bridge/Culvert/Weir
END DESCRIPTION:
XS GIS Cut Line= 6
      3129541.16     13909551.74      3128114.46     13907801.85
      3127122.63     13906969.44      3123760.35      13906853.5
      3122427.04     13905223.08      3121426.08     13904867.19
#Sta/Elev= 30
 -1218.4   77.26   869.6   75.14  1632.3   72.63  2510.6   70.06  3736.8   67.98
  4873.8   72.79    4910   62.35  4944.3   58.26  4978.4   48.05  5004.7   46.52
  5017.5    47.7  5046.1   58.07  5071.6   64.04  5114.2   70.66  5115.3   72.84
  6030.2   70.28  6293.9    73.8  6341.5   73.93  6461.5      69  6545.5   68.57
  6593.5   71.63  6701.5   68.97  6849.7   67.91  7701.7   72.94  7821.7   70.97
    8061   70.93    8193   72.89    8757   72.95    8841   75.81  8875.7   79.92
#Mann= 6 , 1 , 0
 -1218.4      .2       0  1632.3     .14       0  2510.6      .1       0
  4873.8    .035       0  5115.3      .1       0  6293.9     .99       0
#XS Ineff= 2 , 0
       0    4877      72    5115       0    70.8
Permanent Ineff=
       F       F
Bank Sta=4873.8,5115.3
XS Rating Curve= 0 ,0
Exp/Cntr=0.5,0.3

Type RM Length L Ch R = 1 ,141683.0,318.2,518,639.7
BEGIN DESCRIPTION:
Cross Section 141683.0
END DESCRIPTION:
XS GIS Cut Line= 6
      3129300.21     13907994.77      3127769.67     13907177.79
      3126411.46     13906635.56      3123988.27     13906485.21
      3122760.72     13905310.08      3121611.26     13904867.34
#Sta/Elev= 30
    -134    75.9     814   74.72     934   71.46  1154.2   73.01  1282.5   72.73
  1600.9   74.92  2017.7   69.69  2356.9   69.96  2404.9   72.55  2903.9   70.37
  3663.4   68.14 4922.24   68.18 4932.04   60.55 4968.64   50.69 4971.04    46.3
 5013.44   45.42 5031.34   45.77 5031.44   51.93 5044.54   52.55 5106.94   72.57
  5816.3   68.77  5972.3   71.12  6032.3   74.94  6140.3   71.88  6464.3   73.39
  6524.3   71.28  6728.3   70.99  7340.3   73.76  8285.5   72.74  8429.5   76.11
#Mann= 7 , 1 , 0
    -134      .2       0  1154.2     .14       0  1282.5      .1       0
  2017.7      .1       0  2903.9     .07       0 4922.24    .035       0
 5106.94     .99       0
#XS Ineff= 2 , 0
       0  1600.9   74.92               0
Permanent Ineff=
       F       F
Bank Sta=4922.24,5106.94
XS Rating Curve= 0 ,0
Exp/Cntr=0.3,0.1

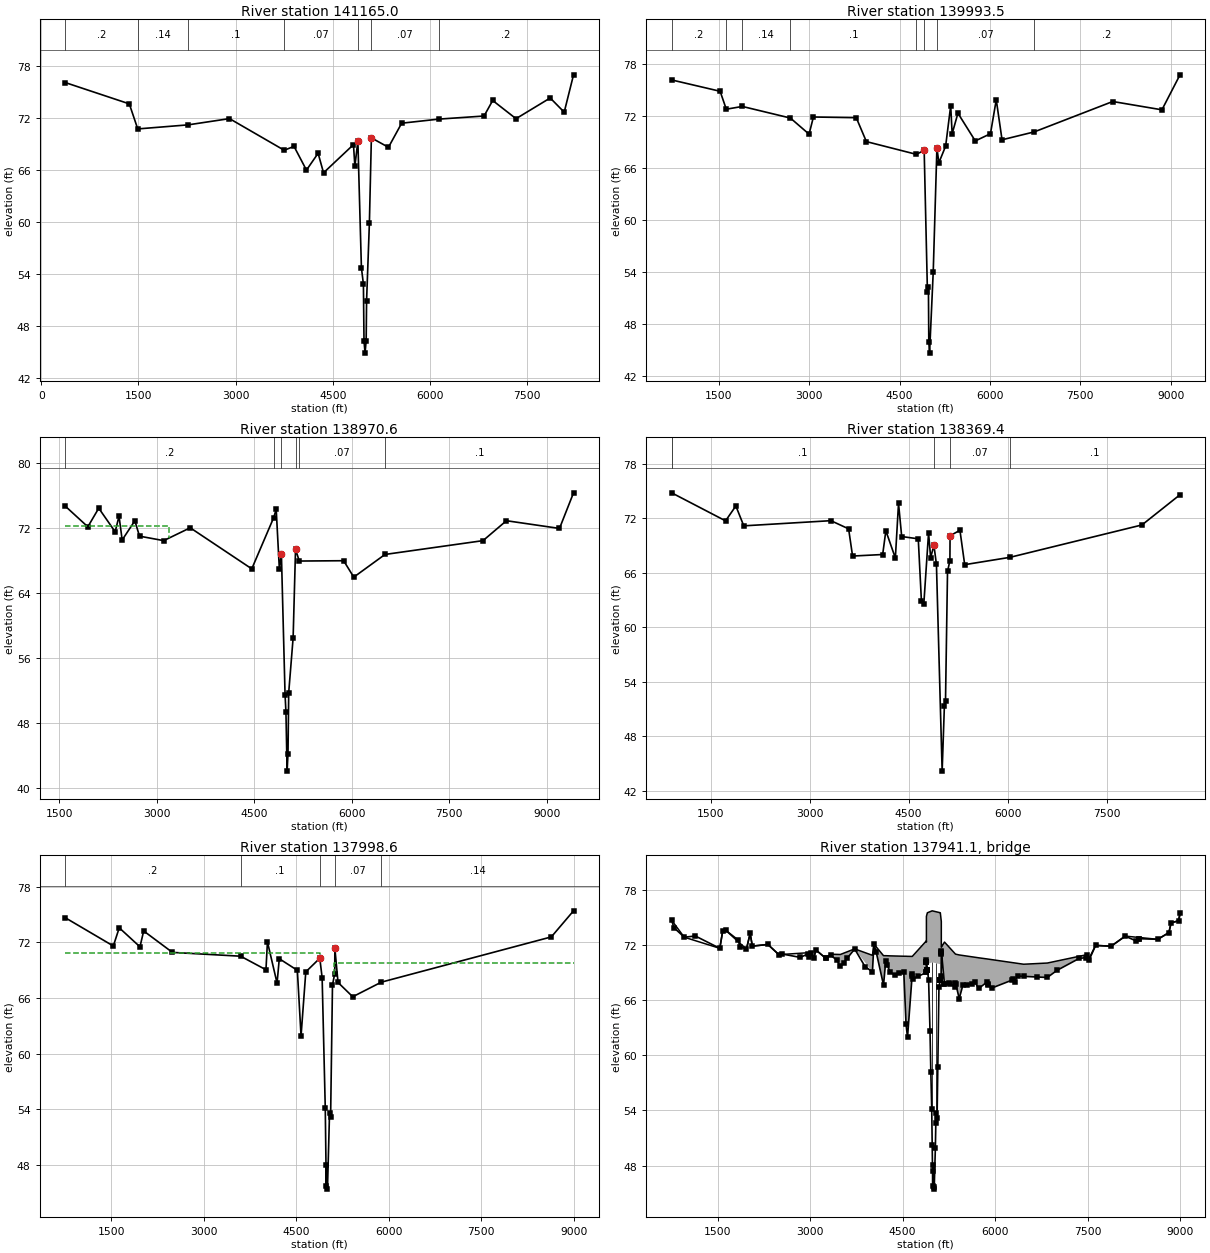
Type RM Length L Ch R = 1 ,141165.0,1202.4,1171.5,981.4
BEGIN DESCRIPTION:
Cross Section 141165.0
END DESCRIPTION:
XS GIS Cut Line= 6
       3128857.8      13907573.7       3128224.7     13907219.16
      3126695.99     13906469.45      3124871.41     13906141.12
      3122775.75     13905074.76      3121596.41     13904790.45
#Sta/Elev= 30
   370.6   76.06  1360.2    73.6  1490.3   70.71  2269.2   71.18  2906.8    71.9
  3751.7   68.25  3902.8    68.7  4094.8   65.96  4274.8    67.9  4358.8   65.65
  4820.7    68.9  4842.5    66.4  4888.6   69.33  4943.3    54.7  4974.3    52.8
  4983.3   46.26  4999.6   44.85  5016.7    46.3  5023.3   50.92  5066.3   59.81
  5097.1   69.68  5360.8   68.59  5564.8   71.37  6134.3   71.84  6836.8    72.2
    6970   73.99    7330   71.89    7858   74.28    8074   72.64    8218   76.95
#Mann= 7 , 1 , 0
   370.6      .2       0  1490.3     .14       0  2269.2      .1       0
  3751.7     .07       0  4888.6    .035       0  5097.1     .07       0
  6134.3      .2       0
#XS Ineff= 2 , 0
       0                    6970       0   73.99
Permanent Ineff=
       F       F
Bank Sta=4888.6,5097.1
XS Rating Curve= 0 ,0
Exp/Cntr=0.3,0.1

Type RM Length L Ch R = 1 ,139993.5,1289.4,1022.9,554.1
BEGIN DESCRIPTION:
Cross Section 139993.5
END DESCRIPTION:
XS GIS Cut Line= 6
      3129288.64     13907598.41      3127221.85     13906069.07
      3125771.96     13905663.82      3125375.72     13905411.67
      3122935.22     13904943.38      3121548.83     13904721.29
#Sta/Elev= 30
   717.5   76.16  1521.5   74.85  1623.7   72.78  1889.8    73.1  2687.6   71.76
  2997.5    69.9  3069.5   71.88  3780.6    71.8  3948.6   69.04  4777.7   67.57
  4907.5   68.03  4961.6   51.73    4978   52.24  4984.3   45.94  4996.9   44.62
  5057.9   54.02  5118.9   68.31  5151.5    66.6  5263.7   68.52  5347.7   73.18
  5371.7   69.95  5467.7   72.32  5755.7   69.12  6007.7   69.95  6103.7   73.87
  6199.7   69.25  6733.3   70.16  8036.8   73.67  8852.8   72.71  9152.8   76.75
#Mann= 8 , 1 , 0
   717.5      .2       0  1623.7      .1       0  1889.8     .14       0
  2687.6      .1       0  4777.7     .07       0  4907.5    .035       0
  5118.9     .07       0  6733.3      .2       0
#XS Ineff= 2 , 0
       0                  8036.8       0   73.67
Permanent Ineff=
       F       F
Bank Sta=4907.5,5118.9
XS Rating Curve= 0 ,0
Exp/Cntr=0.3,0.1

Type RM Length L Ch R = 1 ,138970.6,565.8,601.2,365.4
BEGIN DESCRIPTION:
Cross Section 138970.6
END DESCRIPTION:
XS GIS Cut Line= 6
      3128805.24     13906104.69      3128131.41     13905335.12
      3127392.95      13904812.8      3126807.59     13904614.68
      3123448.53     13904767.77      3121558.43     13904618.84
#Sta/Elev= 30
    1593   74.72    1941   72.17    2109   74.46    2361   71.56    2421   73.48
    2469   70.55  2663.9   72.91  2735.9   71.02  3107.9   70.47  3515.9   72.05
  4462.4      67    4800   73.31  4838.3   74.32  4886.5   67.01  4918.3   68.78
  4974.5   51.49  4987.8   49.43  5005.9   42.12  5019.6   44.26  5030.7   51.79
  5098.5   58.52  5135.4   69.39  5193.6   67.96  5875.3      68  6031.3   65.98
  6511.7   68.77  8019.3   70.47  8379.3   72.92  9195.3   71.97  9411.3   76.35
#Mann= 6 , 1 , 0
    1593      .2       0    4800      .1       0  4918.3    .035       0
  5135.4      .1       0  5193.6     .07       0  6511.7      .1       0
#XS Ineff= 2 , 0
       0  3191.9   72.24  8379.3       0   72.92
Permanent Ineff=
       F       F
Bank Sta=4918.3,5135.4
XS Rating Curve= 0 ,0
Exp/Cntr=0.3,0.1

Type RM Length L Ch R = 1 ,138369.4,243.4,370.8,399.9
BEGIN DESCRIPTION:
Cross Section 138369.4-Interpolated
END DESCRIPTION:
XS GIS Cut Line= 6
      3128852.82     13906072.97      3127654.19     13904730.43
      3127008.59     13904352.52      3126048.08     13904210.81
      3124268.77     13904478.49      3121892.81     13904492.75
#Sta/Elev= 30
   910.8   74.83  1726.8   71.74  1882.8   73.38  2002.8   71.19  3322.6   71.76
  3590.6   70.86  3650.6   67.86  4106.6   68.03  4154.6   70.65  4298.6   67.64
  4346.6   73.67  4394.6   70.01  4645.5   69.76  4693.5   62.87  4729.5   62.56
  4801.5   70.42  4832.8    67.7  4882.9   69.03  4920.8   66.94  5007.3   44.15
  5041.2   51.33  5058.1   51.87  5088.7   66.16  5124.8   67.36  5127.2    70.1
  5276.8    70.7  5348.8   66.91  6035.1   67.72  8033.7   71.29  8609.7   74.62
#Mann= 5 , 1 , 0
   910.8      .2       0   910.8      .1       0  4882.9    .035       0
  5127.2     .07       0  6035.1      .1       0
Bank Sta=4882.9,5127.2
XS Rating Curve= 0 ,0
Exp/Cntr=0.5,0.3

Type RM Length L Ch R = 1 ,137998.6,115,115,115
BEGIN DESCRIPTION:
Upstream Section of Bridge/Culvert/Weir
END DESCRIPTION:
XS GIS Cut Line= 6
      3128773.54     13905929.19      3126958.29     13904009.58
      3125175.29     13903945.02      3123734.41     13904273.54
      3122078.77     13904236.62      3121428.47     13904385.36
#Sta/Elev= 30
   755.8   74.65  1535.8    71.6  1631.8   73.56  1967.8   71.51  2027.8   73.22
    2494   70.91  3599.8    70.5  4010.2   69.04  4034.2   72.05  4190.2    67.6
  4226.2   70.23    4519   68.98    4579   61.91  4655.9   68.81  4882.9   70.28
  4920.8   68.19  4971.6   54.14  4987.8   45.69  4991.2   47.98  5007.3    45.4
    5041   53.65  5058.1   53.12  5088.7   67.41  5124.8   68.61  5127.2   71.35
  5178.5   67.67    5417   66.13  5879.3    67.7  8636.3   72.58  8996.3   75.39
#Mann= 5 , 1 , 0
   755.8      .2       0  3599.8      .1       0  4882.9    .035       0
  5127.2     .07       0  5879.3     .14       0
#XS Ineff= 2 , 0
       0    4890    70.8    5121       0    69.8
Permanent Ineff=
       F       F
Bank Sta=4882.9,5127.2
XS Rating Curve= 0 ,0
Exp/Cntr=0.5,0.3

Type RM Length L Ch R = 3 ,137941.1,,,
BEGIN DESCRIPTION:
ALDINE BENDER ROAD
Structure ID: P00-37
END DESCRIPTION:
Bridge Culvert--1,0,-1,-1, 0
Deck Dist Width WeirC Skew NumUp NumDn MinLoCord MaxHiCord MaxSubmerge Is_Ogee
10,95,2.6,0, 60, 60, , , 0.95, 0, 1,1,,
   755.8   959.8  1535.8  1583.8  1631.8  1967.8  2027.8  2063.8  2315.8    2494
    3010    3058    3094    3250    3334    3490  3722.2  4010.2  4034.2  4190.2
  4226.2  4298.2    4519    4555    4579  4655.9  4882.8  4882.9 4885.29  4885.4
    4901  4901.2  4979.1  5110.9 5111.39  5111.5  5124.8    5127 5127.11  5127.2
  5178.5  5356.6    5417    5477    5672    5732    5864  5945.6  6461.7  6845.8
  7493.8  7520.3  7628.3  7880.3  8108.3  8636.3  8816.3  8852.3  8972.3  8996.3
   74.68   72.84   71.63   73.54   73.59   71.54   73.25   71.87   72.05   70.94
   71.17   70.54   71.45   70.57   70.99   70.96   71.57   70.87   72.09   70.83
   70.83   70.81   70.77   70.77   70.76   70.75   72.43   72.42   72.31   75.11
    75.5    75.5   75.71    75.5   75.47   75.46   74.67   74.55   71.75   71.75
   72.31      71   70.91   70.85   70.66    70.6   70.48    70.4    69.9   70.03
   70.95   70.51   71.95   71.87   72.96   72.61   73.34   74.41   74.62   75.42
   74.68   72.84   71.63   73.54   73.59   71.54   73.25   71.87   72.05   70.94
   71.17   70.54   71.45   70.57   70.87   69.66   71.56   69.07   72.08   67.63
   70.26   69.05   69.01   63.38   61.94   68.84   69.01   70.31   70.18   70.17
   69.31    69.9   70.11    69.9   69.87    68.2   68.64   71.15   71.28   71.38
    67.7    67.9   66.16   67.63   67.95   67.26   67.94   67.31   68.58   68.46
   70.94   70.32   71.94   71.86   72.95   72.61   73.34   74.41   74.62   75.42
   755.8   959.8  1535.8  1583.8  1631.8  1967.8  2027.8  2063.8  2315.8    2494
    3010    3058    3094    3250    3334    3490  3722.2  4010.2  4034.2  4190.2
  4226.2  4298.2    4519    4555    4579  4655.9  4882.8  4882.9 4885.29  4885.4
    4901  4901.2  4979.1  5110.9 5111.39  5111.5  5124.8    5127 5127.11  5127.2
  5178.5  5356.6    5417    5477    5672    5732    5864  5945.6  6461.7  6845.8
  7493.8  7520.3  7628.3  7880.3  8108.3  8636.3  8816.3  8852.3  8972.3  8996.3
   74.68   72.84   71.63   73.54   73.59   71.54   73.25   71.87   72.05   70.94
   71.17   70.54   71.45   70.57   70.99   70.96   71.57   70.87   72.09   70.83
   70.83   70.81   70.77   70.77   70.76   70.75   72.43   72.42   72.31   75.11
    75.5    75.5   75.71    75.5   75.47   75.46   74.67   74.55   71.75   71.75
   72.31      71   70.91   70.85   70.66    70.6   70.48    70.4    69.9   70.03
   70.95   70.51   71.95   71.87   72.96   72.61   73.34   74.41   74.62   75.42
   74.48   72.64   71.43   73.34   73.39   71.34   73.05   71.67   71.85   70.74
   70.97   70.34   71.25   70.37   70.67   69.46   71.36   68.87   71.88   67.43
   70.06   68.85   68.81   63.18   61.74   68.64   68.81   70.11   69.98   69.97
   69.11    69.7   69.91    69.7   69.67      68   68.44   70.95   71.08   71.18
    67.5    67.7   65.96   67.43   67.75   67.06   67.74   67.11   68.38   68.26
   70.74   70.12   71.74   71.66   72.75   72.41   73.14   74.21   74.42   75.22
Pier Skew, UpSta & Num, DnSta & Num=  ,4971.6, 2 ,4971.6, 2 , 0 , 0 , 0 ,,
     1.3     1.3
   52.83   71.09
     1.3     1.3
   52.63   70.89
Pier Skew, UpSta & Num, DnSta & Num=  ,5041, 2 ,5041, 2 , 0 , 0 , 0 ,,
     1.3     1.3
   51.62   71.01
     1.3     1.3
   51.42   70.81
BR Coef= 1 , 1 , 0 ,1.25, 0 ,,,0.8,0,2,0,
WSPro=,,,, 1 ,,,, 0 ,,,, 0 ,,,,-1 ,-1 ,-1 , 0 , 0 , 0 , 0 , 0
BR U #Sta/Elev= 121
   755.8   74.68   791.8   73.88   959.8   72.84  1139.8   72.97  1535.8   71.63
  1583.8   73.54  1631.8   73.59  1835.8   72.52  1859.8   71.82  1967.8   71.54
  2027.8   73.25  2063.8   71.87  2315.8   72.05    2494   70.94    2542   71.02
    2842   70.64    2962   71.02    2986   70.68    3010   71.17    3058   70.54
    3094   71.45    3250   70.57  3264.2   70.62    3334   70.87    3430   70.37
    3490   69.66  3542.2   70.04  3599.8   70.53  3722.2   71.56  3890.2   69.65
  4010.2   69.07  4034.2   72.08  4070.2   71.26  4190.2   67.63  4226.2   70.26
  4250.2   69.77  4298.2   69.05    4375   68.73    4435   68.91    4519   69.01
    4555   63.38    4579   61.94  4655.9   68.84  4657.8   68.61  4660.6   68.28
  4753.6   68.59  4880.7      69  4882.8   69.01  4882.9   70.31 4885.29   70.18
  4885.4   70.17 4885.51   70.17    4901   69.31 4901.11   69.31  4901.2    69.3
  4901.3    69.3  4920.8   68.22  4943.7   62.62  4957.2   58.12  4971.6   54.17
  4979.1   50.26  4987.8   45.72  4991.2   48.01  4999.9   47.44  5007.3   45.43
  5012.3   45.65  5030.5    49.9    5041   53.68  5041.2   52.61  5058.1   53.15
  5070.1   58.73  5088.7   67.44  5110.9   68.18  5111.3   68.19 5111.39   68.19
  5111.5    68.2  5124.8   68.64 5126.89   71.03    5127   71.15 5127.11   71.28
  5127.2   71.38  5178.3   67.71  5178.5    67.7  5259.2   67.83  5273.1   67.76
  5350.4    67.4  5356.6    67.9  5362.4   67.73    5417   66.16    5477   67.63
    5549   67.68    5624   67.79    5672   67.95    5732   67.26    5864   67.94
  5879.3   67.73  5885.6   67.65  5945.6   67.31  6269.6   68.16  6291.6   68.26
  6315.6      68  6363.6   68.61  6461.7   68.58    6673   68.51  6845.8   68.46
  7001.8   69.23  7361.8   70.53  7469.8   70.62  7493.8   70.94  7520.3   70.32
  7628.3   71.94  7880.3   71.86  8108.3   72.95  8288.3   72.43  8324.3   72.68
  8329.2   72.68  8636.3   72.61  8816.3   73.34  8852.3   74.41  8972.3   74.62
  8996.3   75.42
BR U #Mann= 5
   755.8      .2  3599.8      .1  4882.9    .035  5127.2     .07  5879.3     .14
BR U Banks=4882.9,5127.2
BR D #Sta/Elev= 121
   755.8   74.48   791.8   73.68   959.8   72.64  1139.8   72.77  1535.8   71.43
  1583.8   73.34  1631.8   73.39  1835.8   72.32  1859.8   71.62  1967.8   71.34
  2027.8   73.05  2063.8   71.67  2315.8   71.85    2494   70.74    2542   70.82
    2842   70.44    2962   70.82    2986   70.48    3010   70.97    3058   70.34
    3094   71.25    3250   70.37  3264.2   70.42    3334   70.67    3430   70.17
    3490   69.46  3542.2   69.84  3599.8   70.33  3722.2   71.36  3890.2   69.45
  4010.2   68.87  4034.2   71.88  4070.2   71.06  4190.2   67.43  4226.2   70.06
  4250.2   69.57  4298.2   68.85    4375   68.53    4435   68.71    4519   68.81
    4555   63.18    4579   61.74  4655.9   68.64  4657.8   68.41  4660.6   68.08
  4753.6   68.39  4880.7    68.8  4882.8   68.81  4882.9   70.11 4885.29   69.98
  4885.4   69.97 4885.51   69.97    4901   69.11 4901.11   69.11  4901.2    69.1
  4901.3    69.1  4920.8   68.02  4943.7   62.42  4957.2   57.92  4971.6   53.97
  4979.1   50.06  4987.8   45.52  4991.2   47.81  4999.9   47.24  5007.3   45.23
  5012.3   45.45  5030.5    49.7    5041   53.48  5041.2   52.41  5058.1   52.95
  5070.1   58.53  5088.7   67.24  5110.9   67.98  5111.3   67.99 5111.39   67.99
  5111.5      68  5124.8   68.44 5126.89   70.83    5127   70.95 5127.11   71.08
  5127.2   71.18  5178.3   67.51  5178.5    67.5  5259.2   67.63  5273.1   67.56
  5350.4    67.2  5356.6    67.7  5362.4   67.53    5417   65.96    5477   67.43
    5549   67.48    5624   67.59    5672   67.75    5732   67.06    5864   67.74
  5879.3   67.53  5885.6   67.45  5945.6   67.11  6269.6   67.96  6291.6   68.06
  6315.6    67.8  6363.6   68.41  6461.7   68.38    6673   68.31  6845.8   68.26
  7001.8   69.03  7361.8   70.33  7469.8   70.42  7493.8   70.74  7520.3   70.12
  7628.3   71.74  7880.3   71.66  8108.3   72.75  8288.3   72.23  8324.3   72.48
  8329.2   72.48  8636.3   72.41  8816.3   73.14  8852.3   74.21  8972.3   74.42
  8996.3   75.22
BR D #Mann= 5
   755.8      .2  3599.8      .1  4882.9    .035  5127.2     .07  5879.3     .14
BR D Banks=4882.9,5127.2
BC Design=,, 0 ,, 0 ,,,,,,
BC HTab HWMax=75.39
BC Use User HTab Curves=0
BC User HTab FreeFlow(D)= 0

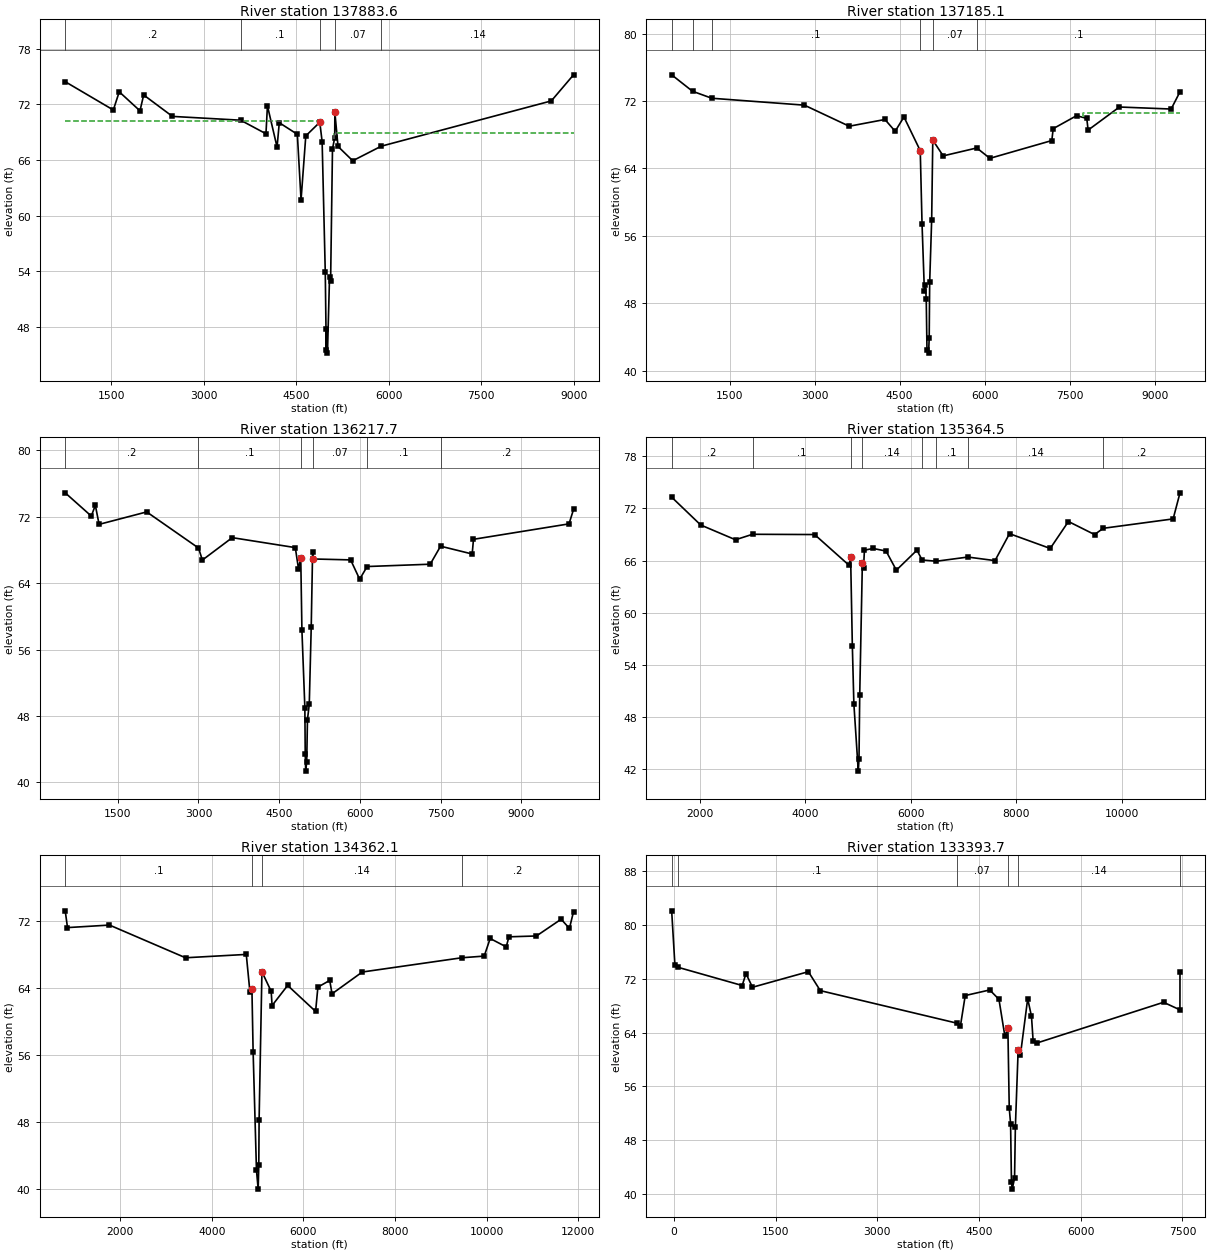
Type RM Length L Ch R = 1 ,137883.6,698.5,698.5,698.5
BEGIN DESCRIPTION:
Downstream Section of Bridge/Culvert/Weir
END DESCRIPTION:
XS GIS Cut Line= 6
      3128778.14     13905814.28      3126962.89     13903894.68
      3125179.89     13903830.12      3123739.01     13904158.64
      3122083.37     13904121.72      3121433.07     13904270.46
#Sta/Elev= 30
   755.8   74.44  1535.8   71.39  1631.8   73.35  1967.8    71.3  2027.8   73.01
    2494    70.7  3599.8   70.29  4010.2   68.83  4034.2   71.84  4190.2   67.39
  4226.2   70.02    4519   68.77    4579    61.7  4655.9    68.6  4882.9   70.07
  4920.8   67.98  4971.6   53.93  4987.8   45.48  4991.2   47.77  5007.3   45.19
    5041   53.44  5058.1   52.91  5088.7    67.2  5124.8    68.4  5127.2   71.14
  5178.5   67.46    5417   65.92  5879.3   67.49  8636.3   72.37  8996.3   75.18
#Mann= 5 , 1 , 0
   755.8      .2       0  3599.8      .1       0  4882.9    .035       0
  5127.2     .07       0  5879.3     .14       0
#XS Ineff= 2 , 0
       0    4890    70.2    5121       0    68.9
Permanent Ineff=
       F       F
Bank Sta=4882.9,5127.2
XS Rating Curve= 0 ,0
Exp/Cntr=0.5,0.3

Type RM Length L Ch R = 1 ,137185.1,976.6,967.4,892
BEGIN DESCRIPTION:
Cross Section 137185.1
END DESCRIPTION:
XS GIS Cut Line= 6
      3128854.93     13905890.34      3127893.19     13904708.57
      3126919.11     13903714.35      3125049.62     13903005.23
      3123233.85       13902973.      3121018.27     13903243.73
#Sta/Elev= 30
   480.1    75.1   847.6   73.15  1188.2   72.32  2820.2    71.5  3610.7      69
  4240.7    69.8  4420.7    68.4  4575.7    70.1  4863.1    66.1  4894.6   57.42
  4936.3   49.39  4955.2   50.18  4968.7   48.48  4981.9   42.42  5010.2   42.07
  5020.9   43.83  5029.3   50.46  5064.4   57.91  5084.1   67.35  5267.7   65.48
  5860.1   66.42  6091.1   65.19  7183.1    67.3  7207.1   68.71  7619.2   70.25
  7799.2   69.93  7823.2   68.54  8375.2   71.28  9287.2   71.04  9443.2   73.09
#Mann= 6 , 1 , 0
   480.1      .1       0   847.6     .14       0  1188.2      .1       0
  4863.1    .035       0  5084.1     .07       0  5860.1      .1       0
#XS Ineff= 2 , 0
       0                  7727.2       0    70.6
Permanent Ineff=
       F       F
Bank Sta=4863.1,5084.1
XS Rating Curve= 0 ,0
Exp/Cntr=0.3,0.1

Type RM Length L Ch R = 1 ,136217.7,385.3,853.2,1009.2
BEGIN DESCRIPTION:
Cross Section 136217.7
END DESCRIPTION:
XS GIS Cut Line= 6
      3128652.34     13905487.27      3127638.97     13904294.54
      3126349.67     13902446.53       3125919.9     13902285.37
      3125103.34     13902113.46      3120796.04     13902596.28
#Sta/Elev= 30
   522.2    74.9  1007.2    72.1  1082.2    73.4  1152.2    71.1  2037.2    72.6
    3000   68.25  3072.3    66.8  3627.3    69.5  4799.6    68.3  4858.8   65.75
    4901   67.02  4922.6   58.34  4977.3      49    4984   43.42  4992.9   41.37
  5011.6    42.5  5025.6   47.58  5059.1   49.41  5095.5   58.72  5121.1   67.78
  5134.9   66.93  5828.1   66.82  5996.1   64.49  6134.7   66.02  7307.7    66.3
    7500   68.47  8087.7   67.53  8111.7    69.3  9887.7   71.16  9971.7    72.9
#Mann= 6 , 1 , 0
   522.2      .2       0    3000      .1       0    4901    .035       0
  5134.9     .07       0  6134.7      .1       0    7500      .2       0
Bank Sta=4901,5134.9
XS Rating Curve= 0 ,0
Exp/Cntr=0.3,0.1

Type RM Length L Ch R = 1 ,135364.5,798,1002.4,1008.8
BEGIN DESCRIPTION:
Cross Section 135364.5
END DESCRIPTION:
XS GIS Cut Line= 6
      3127856.03      13904450.9      3127219.95     13903134.16
      3126177.76     13901565.51      3125790.97     13901232.44
      3122610.69     13900963.83      3120096.49     13901564.65
#Sta/Elev= 30
  1466.6    73.3  2016.6    70.1  2676.6    68.4    3000   69.03  4175.7      69
  4831.9   65.45  4858.8   66.46  4891.3   56.23  4920.5   49.51  5004.1   41.78
  5017.7   43.17  5031.3    50.5  5081.5   65.75  5103.5   65.13  5120.4    67.2
  5285.4    67.4  5530.8    67.1  5725.8    64.9  6115.8    67.2    6215   66.07
  6484.3   65.93    7081   66.41  7595.8      66  7870.8    69.1  8642.7    67.4
  8987.7    70.5  9482.7      69  9648.6   69.72 10972.7    70.8 11102.7    73.8
#Mann= 8 , 1 , 0
  1466.6      .2       0    3000      .1       0  4858.8    .035       0
  5081.5     .14       0    6215     .07       0  6484.3      .1       0
    7081     .14       0  9648.6      .2       0
#XS Ineff= 2 , 0
       0                  8987.7       0    70.5
Permanent Ineff=
       F       F
Bank Sta=4858.8,5081.5
XS Rating Curve= 0 ,0
Exp/Cntr=0.3,0.1

Type RM Length L Ch R = 1 ,134362.1,702.3,968.4,2938.1
BEGIN DESCRIPTION:
Cross Section 134362.1
END DESCRIPTION:
XS GIS Cut Line= 6
      3128303.35      13904632.5      3127907.58     13904095.77
      3126962.09     13901012.18        3126672.     13900625.39
      3125525.59     13900275.17      3120132.74      13901362.7
#Sta/Elev= 30
   800.8    73.2   850.8    71.2  1767.7    71.5  3427.7    67.6  4753.5      68
  4834.4   63.46  4877.1   63.82  4903.1   56.37  4976.3   42.24  5013.3      40
  5026.6   42.82  5033.7   48.29  5095.4   65.93    5297    63.6    5317    61.9
    5657    64.3    6267    61.2    6317    64.1  6575.7    64.9  6625.7    63.3
  7285.7    65.9  9456.7    67.6  9947.8    67.8 10077.8    69.9 10427.8    68.9
 10487.8    70.1 11087.8    70.2 11627.8    72.2 11807.8    71.1 11897.8    73.1
#Mann= 4 , 1 , 0
   800.8      .1       0  4877.1    .035       0  5095.4     .14       0
  9456.7      .2       0
Bank Sta=4877.1,5095.4
XS Rating Curve= 0 ,0
Exp/Cntr=0.3,0.1

Type RM Length L Ch R = 1 ,133393.7,1085.9,1077.2,993.9
BEGIN DESCRIPTION:
Cross Section 133393.7
END DESCRIPTION:
XS GIS Cut Line= 6
      3128890.13     13905228.14      3128236.23     13904122.96
      3128122.46     13903440.37      3127724.93      13901914.7
      3127638.97     13899975.37       3127853.2     13897984.97
#Sta/Elev= 30
   -34.3   82.06    13.7   73.95    52.8    73.7  1005.7   70.98  1061.7   72.74
  1157.7   70.72  1981.9   73.03  2157.9   70.22  4170.1    65.4  4223.7   64.91
  4295.7   69.49  4657.1   70.32  4793.1   68.93  4881.1   63.43  4924.7   64.71
  4945.1   52.78  4964.8   50.48  4977.5    41.8    4989   40.77  5023.3   42.39
  5035.3   49.95  5076.2   61.37  5110.2   60.71  5217.1   69.02  5273.1    66.4
  5297.1   62.78  5353.1   62.45    7221   68.49  7462.8   67.37  7463.7      73
#Mann= 6 , 1 , 0
   -34.3     .14       0    52.8      .1       0  4170.1     .07       0
  4924.7    .035       0  5076.2     .14       0  7462.8      .2       0
Bank Sta=4924.7,5076.2
XS Rating Curve= 0 ,0
Exp/Cntr=0.3,0.1