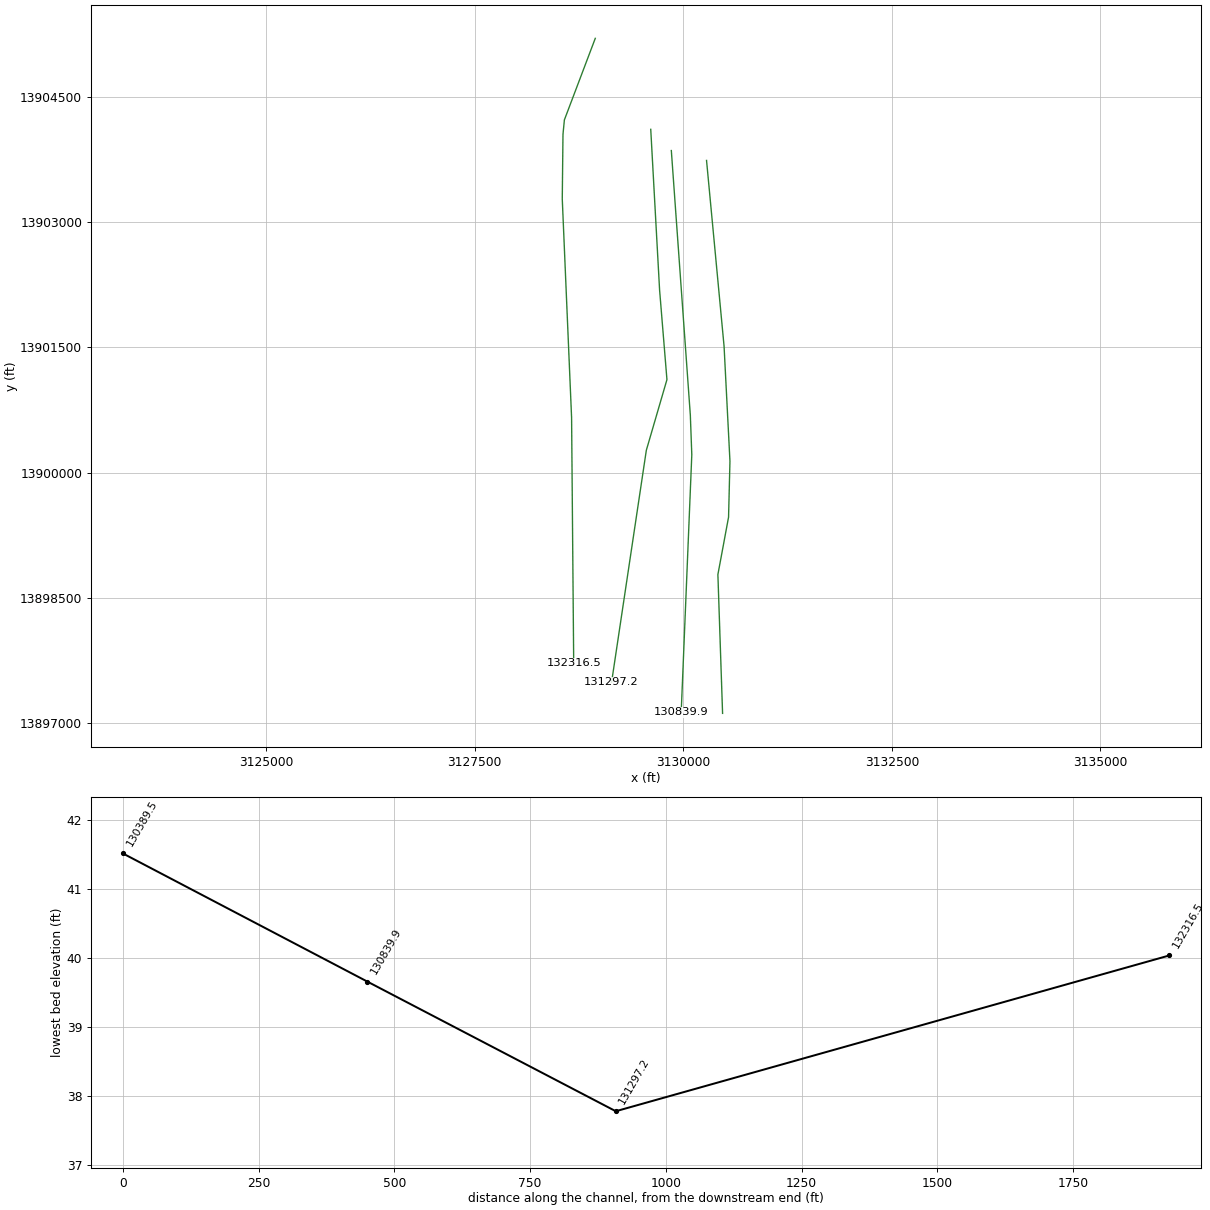
HEC-RAS study P100-00-00.prj: P100-00-00

--- P100-00-00.g01 (geometry) --- (continued)

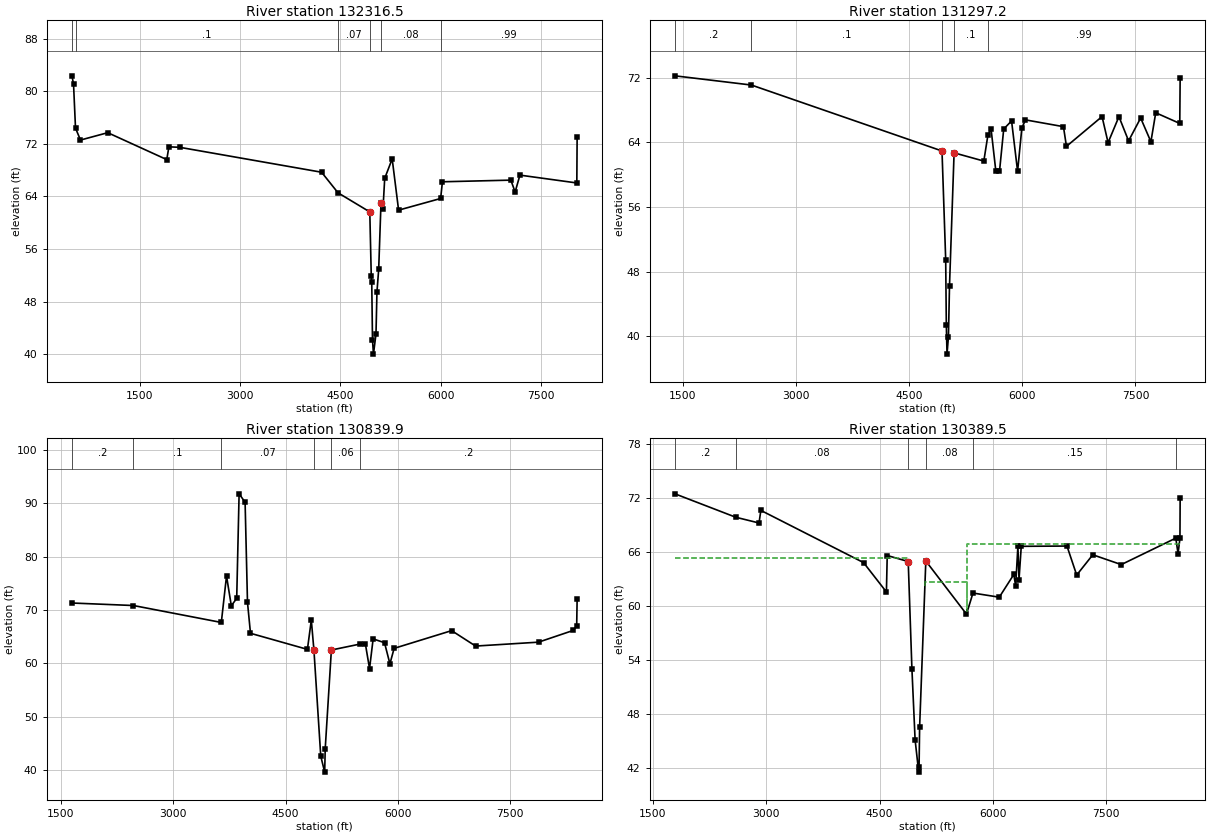
Type RM Length L Ch R = 1 ,132316.5,1166.9,1019.3,710.3
BEGIN DESCRIPTION:
Cross Section 132316.5
END DESCRIPTION:
XS GIS Cut Line= 6
      3128945.77     13905204.75      3128575.56     13904227.51
      3128558.68     13904053.87      3128550.08     13903280.28
      3128661.82      13900658.7       3128687.1     13897715.08
#Sta/Elev= 30
   481.1   82.33   505.1   81.09   534.6   74.39   609.1   72.57  1017.1   73.69
  1900.6    69.6  1932.6   71.54  2092.6   71.47  4218.2   67.68  4464.4   64.55
  4939.7   61.65  4961.7   51.87    4969   50.93    4980    42.2  4994.7   40.04
  5032.5   43.13  5046.8   49.48  5072.7   52.91  5107.4   63.03  5137.5   62.14
  5162.8   66.74  5274.8   69.71  5370.8   61.92    6000   63.69  6026.8   66.23
  7050.9   66.48  7114.9   64.68  7186.9   67.24  8038.5   66.05  8043.1      73
#Mann= 6 , 1 , 0
   481.1      .1       0   534.6      .1       0  4464.4     .07       0
  4939.7    .032       0  5107.4     .08       0    6000     .99       0
Bank Sta=4939.7,5107.4
XS Rating Curve= 0 ,0
Exp/Cntr=0.3,0.1

Type RM Length L Ch R = 1 ,131297.2,269.9,457.3,728.9
BEGIN DESCRIPTION:
Cross Section 131297.2
END DESCRIPTION:
XS GIS Cut Line= 5
      3129610.38     13904114.37      3129716.24     13902191.24
      3129804.45     13901114.99      3129557.44     13900268.11
        3129141.     13897487.21
#Sta/Elev= 30
  1393.3   72.22  2407.6   71.08  4934.9   62.92  4983.8   49.47  4992.2   41.41
  5001.3   37.78  5020.2   39.92  5034.5   46.27  5095.2   62.69  5489.4   61.67
    5544    64.9  5585.4   65.65  5649.4   60.39  5697.4   60.39  5753.4   65.64
  5857.4   66.64  5937.4   60.41  5993.4   65.72  6041.4   66.77  6545.4   65.93
  6585.4   63.49  7057.4   67.18  7137.4   63.95  7281.4   67.17  7409.4   64.17
  7569.4      67  7705.4   64.06  7769.4   67.65  8088.1   66.33  8093.3      72
#Mann= 5 , 1 , 0
  1393.3      .2       0  2407.6      .1       0  4934.9    .032       0
  5095.2      .1       0    5544     .99       0
Bank Sta=4934.9,5095.2
XS Rating Curve= 0 ,0
Exp/Cntr=0.3,0.1

Type RM Length L Ch R = 1 ,130839.9,455.5,450.4,374.3
BEGIN DESCRIPTION:
Cross Section 130839.9-Interpolated
END DESCRIPTION:
XS GIS Cut Line= 4
      3129857.02     13903860.16      3130084.84     13900688.26
      3130102.36     13900215.11       3129975.3      13897126.3
#Sta/Elev= 30
    1648   71.32    2469   70.85  3642.5   67.68    3712   76.38    3776    70.8
    3848   72.19    3880   91.76    3960   90.19    3992   71.43    4032   65.65
    4792   62.64  4844.1   68.12  4879.2   62.46  4970.2   42.65  5022.6   39.66
  5029.8   44.06  5111.9   62.52    5500   63.65  5565.5    63.7  5621.5   59.04
  5669.5    64.6  5821.5   63.89  5893.5   59.93  5949.5   62.83  6717.5   66.15
  7037.5   63.26  7877.5   63.99  8341.5   66.19    8387   67.01    8393      72
#Mann= 6 , 1 , 0
    1648      .2       0    2469      .1       0  3642.5     .07       0
  4879.2    .032       0  5111.9     .06       0    5500      .2       0
Bank Sta=4879.2,5111.9
XS Rating Curve= 0 ,0
Exp/Cntr=0.5,0.3

Type RM Length L Ch R = 1 ,130389.5,109,109,109
BEGIN DESCRIPTION:
Upstream Section of Bridge/Culvert/Weir
END DESCRIPTION:
XS GIS Cut Line= 6
      3130278.97     13903741.44        3130489.     13901515.58
       3130559.6     13900137.09      3130542.79     13899466.33
      3130415.03     13898778.77 3130471.252066913897115.3692777
#Sta/Elev= 30
  1794.1   72.43    2598   69.83  2906.1   69.19  2930.1   70.59  4288.5   64.79
  4590.8   61.53  4601.4   65.58  4879.1   64.91  4927.9   53.01  4970.2    45.1
  5017.7   41.52  5022.6   42.11  5029.8   46.51  5111.9   64.97  5649.5   59.07
  5735.6   61.41  6083.3   60.95  6275.4   63.47  6300.1    62.2  6329.7   66.62
  6344.5   62.91  6374.1    66.6  6978.6   66.63  7107.2   63.41  7320.2   65.66
  7696.9   64.57    8418   67.51  8447.9   65.78  8472.8   67.49  8475.6   71.96
#Mann= 6 ,-1 , 0
  1794.1      .2       0    2598     .08       0  4879.1    .032       0
  5111.9     .08       0  5735.6     .15       0    8418      .2       0
#XS Ineff= 3 ,-1
  1794.1    4873    65.3  5099.6    5660    62.6    5660  8475.6    66.9
Permanent Ineff=
       F       F       F
Bank Sta=4879.1,5111.9
XS Rating Curve= 0 ,0
Exp/Cntr=0.5,0.3