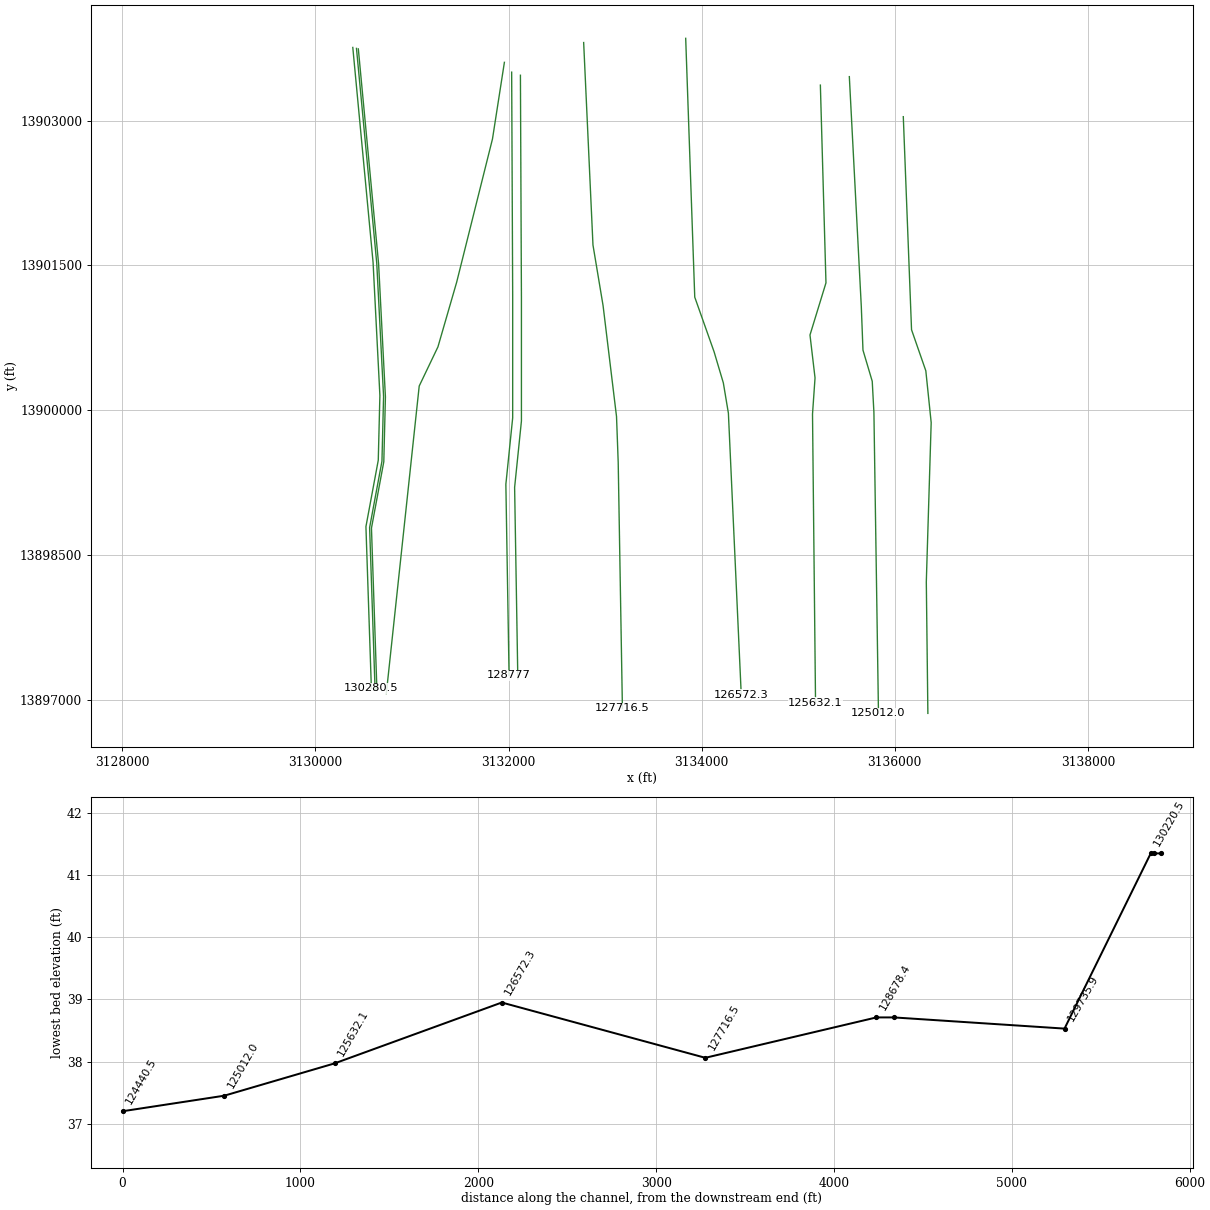
HEC-RAS study P100-00-00.prj: P100-00-00

--- P100-00-00.g01 (geometry) --- (continued)

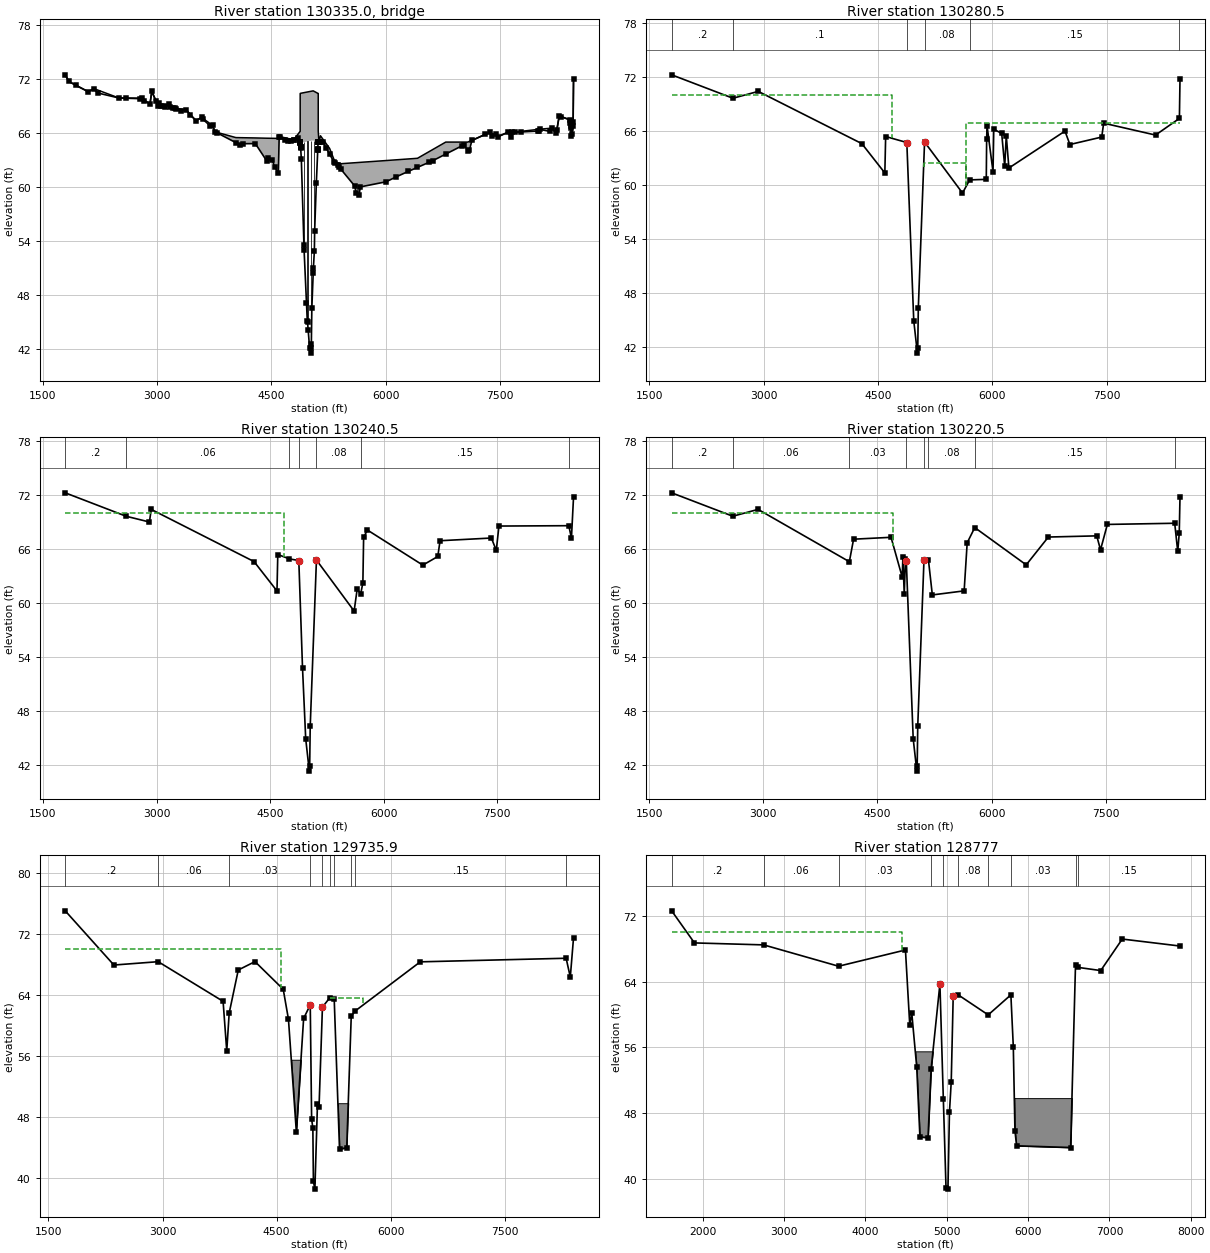
Type RM Length L Ch R = 3 ,130335.0,,,
BEGIN DESCRIPTION:
JOHN F. KENNEDY BOULEVARD
Structure ID: P00-35
END DESCRIPTION:
Bridge Culvert--1,0,-1,-1, 0
Deck Dist Width WeirC Skew NumUp NumDn MinLoCord MaxHiCord MaxSubmerge Is_Ogee
10,89,2.6,0, 60, 60, , , 0.95, 0, 1,1,,
  1794.1  1842.1  2098.1  2170.1  2498.1  2802.1  2906.1  2930.1  3010.1  3154.8
  3170.8  3382.6  3510.6  3582.6  3727.6  3759.6  4032.9  4288.5  4440.5  4510.8
  4590.8  4601.4    4792 4876.89    4877 4882.91    4883  5047.5 5107.59  5107.7
  5113.7 5113.81    5123    5143    5263    5333  5413.5  5649.5  5665.5  6004.1
  6415.6  6786.4  7026.2  7074.2  7130.2  7371.4  7467.4  7603.4  7643.4  7659.4
  8019.4  8179.4  8227.4  8243.4  8275.4  8411.4  8423.8  8435.4  8457.8  8463.1
   72.47   71.74   70.59   70.94    69.9   69.88   69.23   70.63   69.01   69.28
   68.85   68.58   67.38   67.74   66.85   66.14    65.5   65.46   65.43   65.42
   65.41   65.63   65.25    66.2    70.4   70.42   70.42   70.69   70.42   70.42
    70.4    66.2   65.02    65.7    64.3    62.8    62.6   62.74   62.75   62.95
    63.2      65      65      65   65.19   66.08   65.59    66.1   65.52   66.08
   66.43   66.55   66.07   66.32   67.91   67.49    67.2   65.66   67.19      72
   72.47   71.74   70.59   70.94    69.9   69.88   69.23   70.63   69.01   69.28
   68.85   68.58   67.38   67.74   66.85   66.14   64.94   64.83   62.88   62.99
   61.57   65.62   65.24   64.98   64.98   64.41   64.92   65.19   64.92   64.18
   65.01   65.01   65.01   65.02   63.65   62.72   61.96   59.11   60.02   60.59
   62.19   63.67    64.7   64.01   65.18   66.07   65.58   66.09   65.51   66.07
   66.42   66.54   66.06   66.31    67.9   67.48   66.83   65.66   67.19      72
  1794.1  1842.1  2098.1  2170.1  2498.1  2802.1  2906.1  2930.1  3010.1  3154.8
  3170.8  3382.6  3510.6  3582.6  3727.6  3759.6  4032.9  4288.5  4440.5  4510.8
  4590.8  4601.4    4792 4876.89    4877 4882.91    4883  5047.5 5107.59  5107.7
  5113.7 5113.81    5123    5143    5263    5333  5413.5  5649.5  5665.5  6004.1
  6415.6  6786.4  7026.2  7074.2  7130.2  7371.4  7467.4  7603.4  7643.4  7659.4
  8019.4  8179.4  8227.4  8243.4  8275.4  8411.4  8423.8  8435.4  8457.8  8463.1
   72.47   71.74   70.59   70.94    69.9   69.88   69.23   70.63   69.01   69.28
   68.85   68.58   67.38   67.74   66.85   66.14    65.5   65.46   65.43   65.42
   65.41   65.63   65.25    66.2    70.4   70.42   70.42   70.69   70.42   70.42
    70.4    66.2   65.02    65.7    64.3    62.8    62.6   62.74   62.75   62.95
    63.2      65      65      65   65.19   66.08   65.59    66.1   65.52   66.08
   66.43   66.55   66.07   66.32   67.91   67.49    67.2   65.66   67.19      72
   72.31   71.58   70.43   70.78   69.74   69.72   69.07   70.47   68.85   69.12
   68.69   68.42   67.22   67.58   66.69   65.98   64.78   64.67   62.72   62.83
   61.41   65.46   65.08   64.82   64.82   64.25   64.76   65.03   64.76   64.02
   64.85   64.85   64.85   64.86   63.49   62.56    61.8   58.95   59.86   60.43
   62.03   63.51   64.54   63.85   65.02   65.91   65.42   65.93   65.35   65.91
   66.26   66.38    65.9   66.15   67.74   67.32   66.67    65.5   67.03   71.84
Pier Skew, UpSta & Num, DnSta & Num=  ,4927.9, 2 ,4927.9, 2 , 0 , 0 , 0 ,,
     1.3     1.3
   51.93   66.08
     1.3     1.3
   51.77   65.92
Pier Skew, UpSta & Num, DnSta & Num=  ,4972.9, 2 ,4972.9, 2 , 0 , 0 , 0 ,,
     1.3     1.3
   43.99    66.2
     1.3     1.3
   43.83   66.04
Pier Skew, UpSta & Num, DnSta & Num=  ,5017.7, 2 ,5017.7, 2 , 0 , 0 , 0 ,,
     1.3     1.3
   40.58   66.19
     1.3     1.3
   40.42   66.03
Pier Skew, UpSta & Num, DnSta & Num=  ,5062.8, 2 ,5062.8, 2 , 0 , 0 , 0 ,,
     1.3     1.3
   51.77   66.12
     1.3     1.3
   51.61   65.96
BR Coef= 1 , 1 , 0 ,1.25, 0 ,,,0.8,0,2,0,
WSPro=,,,, 1 ,,,, 0 ,,,, 0 ,,,,-1 ,-1 ,-1 , 0 , 0 , 0 , 0 , 0
BR U #Sta/Elev= 140
  1794.1   72.47  1842.1   71.74  1930.1   71.31  2098.1   70.59  2170.1   70.94
  2218.1   70.46  2498.1    69.9    2598   69.87  2778.1   69.82  2802.1   69.88
  2826.1    69.6  2906.1   69.23  2930.1   70.63  2986.1   69.58  3010.1   69.01
  3026.1   69.34  3050.8      69  3082.8   69.04  3106.8   68.94  3154.8   69.28
  3170.8   68.85  3202.8   68.84  3234.8   68.77  3250.8   68.63  3314.8   68.47
  3382.6   68.58  3430.6   68.04  3510.6   67.38  3582.6   67.74  3599.6   67.54
  3695.6   66.81  3727.6   66.85  3759.6   66.14  3783.6   66.04  4032.9   64.94
  4082.4   64.72  4130.4   64.82  4288.5   64.83  4440.5   62.88  4454.8   63.19
  4510.8   62.99  4542.8   62.21  4590.8   61.57  4601.4   65.62  4606.7   65.52
  4682.2   65.19  4711.6   65.17  4755.8   65.13  4789.6   65.23    4792   65.24
  4847.3   65.41 4876.89   64.98    4877   64.98 4877.11   64.98  4877.7   64.97
  4879.1   64.95  4879.2   64.95  4882.8   64.43 4882.91   64.41    4883    64.4
  4883.1   64.38    4892   63.09    4927   53.57  4927.9   53.05  4959.6   47.12
  4970.2   45.14  4972.9   45.06  4981.2   44.15  5000.1   42.16  5017.7   41.56
  5018.6   42.57  5022.6   42.15  5029.8   46.55  5047.5   50.45  5050.2   51.04
  5062.8   52.86  5066.7   55.16  5088.5   60.41  5107.5   64.15 5107.59   64.16
  5107.7   64.18  5107.8    64.2  5111.9   65.01 5113.59   65.01  5113.7   65.01
 5113.81   65.01    5123   65.01    5143   65.02  5170.1   65.03  5214.7   64.38
    5263   63.65    5319   62.81    5333   62.72  5379.1   62.41  5389.1   62.21
  5413.5   61.96  5593.5   60.11  5609.5   59.34  5649.5   59.11  5665.5   60.02
  6004.1   60.59  6140.1   61.15  6296.4   61.75  6415.6   62.19  6568.2   62.76
  6618.2   62.94  6786.4   63.67    7000   64.59  7026.2    64.7  7074.2   64.01
  7098.2   64.17  7130.2   65.18  7307.4   65.88  7371.4   66.07  7387.4   65.65
  7451.4   65.86  7467.4   65.58  7603.4   66.09  7643.4   65.51  7659.4   66.07
  7694.2   66.09  7771.5   66.12  8001.5   66.23  8011.4   66.23  8019.4   66.42
  8155.4   66.18  8179.4   66.54  8227.4   66.06  8243.4   66.31  8275.4    67.9
  8303.8   67.81  8411.4   67.48  8419.4   67.17  8423.8   66.83  8427.4   66.56
  8435.4   65.66  8443.4   65.87  8451.4   66.81  8457.8   67.19  8463.1      72
BR U #Mann= 5
  1794.1      .2    2598     .08  4879.1    .032  5111.9     .08    7000      .2
BR U Banks=4879.1,5111.9
BR D #Sta/Elev= 140
  1794.1   72.31  1842.1   71.58  1930.1   71.15  2098.1   70.43  2170.1   70.78
  2218.1    70.3  2498.1   69.74    2598   69.71  2778.1   69.66  2802.1   69.72
  2826.1   69.44  2906.1   69.07  2930.1   70.47  2986.1   69.42  3010.1   68.85
  3026.1   69.18  3050.8   68.84  3082.8   68.88  3106.8   68.78  3154.8   69.12
  3170.8   68.69  3202.8   68.68  3234.8   68.61  3250.8   68.47  3314.8   68.31
  3382.6   68.42  3430.6   67.88  3510.6   67.22  3582.6   67.58  3599.6   67.38
  3695.6   66.65  3727.6   66.69  3759.6   65.98  3783.6   65.88  4032.9   64.78
  4082.4   64.56  4130.4   64.66  4288.5   64.67  4440.5   62.72  4454.8   63.03
  4510.8   62.83  4542.8   62.05  4590.8   61.41  4601.4   65.46  4606.7   65.36
  4682.2   65.03  4711.6   65.01  4755.8   64.97  4789.6   65.07    4792   65.08
  4847.3   65.25 4876.89   64.82    4877   64.82 4877.11   64.82  4877.7   64.81
  4879.1   64.79  4879.2   64.79  4882.8   64.27 4882.91   64.25    4883   64.24
  4883.1   64.22    4892   62.93    4927   53.41  4927.9   52.89  4959.6   46.96
  4970.2   44.98  4972.9    44.9  4981.2   43.99  5000.1      42  5017.7    41.4
  5018.6   42.41  5022.6   41.99  5029.8   46.39  5047.5   50.29  5050.2   50.88
  5062.8    52.7  5066.7      55  5088.5   60.25  5107.5   63.99 5107.59      64
  5107.7   64.02  5107.8   64.04  5111.9   64.85 5113.59   64.85  5113.7   64.85
 5113.81   64.85    5123   64.85    5143   64.86  5170.1   64.87  5214.7   64.22
    5263   63.49    5319   62.65    5333   62.56  5379.1   62.25  5389.1   62.05
  5413.5    61.8  5593.5   59.95  5609.5   59.18  5649.5   58.95  5665.5   59.86
  6004.1   60.43  6140.1   60.99  6296.4   61.59  6415.6   62.03  6568.2    62.6
  6618.2   62.78  6786.4   63.51    7000   64.43  7026.2   64.54  7074.2   63.85
  7098.2   64.01  7130.2   65.02  7307.4   65.72  7371.4   65.91  7387.4   65.49
  7451.4    65.7  7467.4   65.42  7603.4   65.93  7643.4   65.35  7659.4   65.91
  7694.2   65.93  7771.5   65.96  8001.5   66.07  8011.4   66.07  8019.4   66.26
  8155.4   66.02  8179.4   66.38  8227.4    65.9  8243.4   66.15  8275.4   67.74
  8303.8   67.65  8411.4   67.32  8419.4   67.01  8423.8   66.67  8427.4    66.4
  8435.4    65.5  8443.4   65.71  8451.4   66.65  8457.8   67.03  8463.1   71.84
BR D #Mann= 5
  1794.1      .2    2598     .08  4879.1    .032  5111.9     .08    7000      .2
BR D Banks=4879.1,5111.9
BC Design=,, 0 ,, 0 ,,,,,,
BC HTab HWMax=72.43
BC Use User HTab Curves=0
BC User HTab FreeFlow(D)= 0

Type RM Length L Ch R = 1 ,130280.5,40,40,40
BEGIN DESCRIPTION:
Property Line
END DESCRIPTION:
XS GIS Cut Line= 6
      3130386.87     13903756.86       3130596.9       13901531.
       3130667.5     13900152.51      3130650.69     13899481.75
      3130522.93     13898794.19      3130579.34     13897118.69
#Sta/Elev= 30
  1794.1   72.26    2598   69.66  2930.1   70.42  4288.5   64.62  4590.8   61.36
  4601.4   65.41  4879.1   64.74  4970.2   44.93  5017.7   41.35  5022.6   41.94
  5029.8   46.34  5111.9    64.8  5609.5   59.13    5704   60.59  5921.5   60.65
  5926.4   65.09  5931.4   66.62    6010   61.49  6019.8   66.22  6123.8   65.75
  6163.6   62.08  6183.6   65.52  6218.4   61.91    6954   66.01  7018.5   64.52
  7436.4   65.35  7461.3   66.89  8142.3   65.57  8455.3   67.42  8463.1   71.79
#Mann= 6 ,-1 , 0
  1794.1      .2       0    2598      .1       0  4879.1    .032       0
  5111.9     .08       0    5704     .15       0  8455.3      .2       0
#XS Ineff= 3 ,-1
  1794.1    4690      70  5099.6    5660    62.5    5660  8463.1    66.9
Permanent Ineff=
       F       F       F
Bank Sta=4879.1,5111.9
XS Rating Curve= 0 ,0
Exp/Cntr=0.5,0.3

Type RM Length L Ch R = 1 ,130240.5,20,20,20
BEGIN DESCRIPTION:
Property Line
END DESCRIPTION:
XS GIS Cut Line= 6
      3130425.04     13903746.99      3130635.07     13901521.13
      3130705.67     13900142.64      3130688.86     13899471.88
       3130561.1     13898784.32      3130617.51     13897108.82
#Sta/Elev= 30
  1794.1   72.26    2598   69.66  2906.1   69.02  2930.1   70.42  4288.5   64.62
  4590.8   61.36  4601.4   65.41  4755.8   64.92  4879.1   64.74  4927.9   52.84
  4970.2   44.93  5017.7   41.35  5022.6   41.94  5029.8   46.34  5111.9    64.8
  5609.5   59.13  5650.7   61.61  5695.4      61  5725.1   62.26    5735    67.3
  5784.6   68.13  6516.7   64.23  6714.5   65.19  6744.2   66.94  7422.4   67.24
    7487   65.86  7521.9   68.57  8444.6   68.61  8479.4   67.22  8507.1   71.79
#Mann= 7 ,-1 , 0
  1794.1      .2       0    2598     .06       0  4755.8     .03       0
  4879.1    .032       0  5111.9     .08       0  5695.4     .15       0
  8444.6      .2       0
#XS Ineff= 2 , 0
       0    4690      70  5784.6       0   68.13
Permanent Ineff=
       F       F
Bank Sta=4879.1,5111.9
XS Rating Curve= 0 ,0
Exp/Cntr=0.5,0.3

Type RM Length L Ch R = 1 ,130220.5,484.6,484.6,484.6
BEGIN DESCRIPTION:
Property Line
END DESCRIPTION:
XS GIS Cut Line= 6
      3130444.17     13903741.53       3130654.2     13901515.67
       3130724.8     13900137.18      3130707.99     13899466.42
      3130580.23     13898778.86      3130636.64     13897103.36
#Sta/Elev= 30
  1794.1   72.26    2598   69.66  2930.1   70.42  4130.4   64.61  4186.1   67.11
 4678.79   67.32  4826.2   62.88  4834.1   65.08  4852.4      61    4868    64.9
  4879.1   64.74  4970.2   44.93  5017.7   41.35  5022.6   41.94  5029.8   46.34
  5111.9    64.8  5170.1   64.82  5221.7   60.92    5640   61.37  5679.9   66.71
  5779.6    68.4    6456   64.26  6747.2   67.35  7383.5   67.48  7433.3   65.93
  7523.1   68.75  8408.8   68.88  8448.6   65.75  8468.4   67.76  8478.4   71.79
#Mann= 8 ,-1 , 0
  1794.1      .2       0    2598     .06       0  4130.4     .03       0
  4879.1    .032       0  5111.9     .08       0  5170.1     .08       0
  5779.6     .15       0  8408.8      .2       0
#XS Ineff= 2 , 0
       0    4710      70  5779.6       0    68.4
Permanent Ineff=
       F       F
Bank Sta=4879.1,5111.9
XS Rating Curve= 0 ,0
Exp/Cntr=0.5,0.3

Type RM Length L Ch R = 1 ,129735.9,722.9,958.9,966.4
BEGIN DESCRIPTION:
Cross Section 129735.9 - Blocked Obstruction to limit conveyance in detention pond.
END DESCRIPTION:
XS GIS Cut Line= 6
      3131956.95     13903602.71      3131833.45     13902808.76
      3131462.93     13901326.71      3131268.86     13900656.26
      3131074.78     13900250.47 3130733.895401913897065.4738134
#Sta/Elev= 30
    1720   75.03    2360   67.92  2942.4   68.36  3795.5   63.16  3843.5   56.65
  3875.5   61.62    3995   67.27    4215   68.37    4586   64.74  4654.7   60.81
  4758.3   46.06  4854.1   60.91  4941.2    62.7  4959.3   47.72  4975.5   46.53
  4982.7   39.54  5002.1   38.53    5036   49.66    5057   49.36  5101.4    62.4
    5199   63.64 5256.27   63.41 5325.94    43.8 5420.48   43.95  5480.2   61.26
  5535.1   61.92  6387.4   68.34  8304.9   68.81  8359.7   66.34  8402.2    71.5
#Mann= 10 ,-1 , 0
    1720      .2       0  2942.4     .06       0  3875.5     .03       0
  4941.2    .032       0  5101.4     .08       0    5199     .06       0
 5256.27     .03       0  5480.2     .06       0  5535.1     .15       0
  8304.9      .2       0
#XS Ineff= 2 ,-1
    1720    4563      70    5199    5630   63.64
Permanent Ineff=
       F       T
#Block Obstruct= 2 ,-1
    4400    4887    55.5    5247    5457    49.8
Bank Sta=4941.2,5101.4
XS Rating Curve= 0 ,0
Exp/Cntr=0.3,0.1

Type RM Length L Ch R = 1 ,128777  ,98.6,98.6,98.6
BEGIN DESCRIPTION:
Cross Section 128678.4 - Blocked Obstruction to limit conveyance in detention pond.
END DESCRIPTION:
XS GIS Cut Line= 5
       3132032.2       13903501.       3132042.7      13901191.2
       3132042.7      13899920.9       3131972.1      13899232.8
 3132005.331459913897254.2867306
#Sta/Elev= 30
  1616.8   72.62  1896.8   68.71  2747.7   68.47    3669   65.87  4491.4   67.85
  4544.2   58.73  4569.2   60.15  4629.7   53.61  4669.4   45.06  4769.1   44.99
  4806.9   53.32  4915.2   63.71  4957.1   49.75  4990.3   38.83  5014.1   38.71
  5032.4   48.06  5054.3   51.78  5078.8    62.3  5134.2   62.42    5509   59.94
  5787.8   62.38  5817.7   56.06  5837.7   45.85  5857.7   43.99  6522.6   43.78
  6582.6   66.08  6612.6   65.73  6892.6   65.34  7157.5   69.18  7867.4   68.33
#Mann= 10 ,-1 , 0
  1616.8      .2       0  2747.7     .06       0    3669     .03       0
  4806.9     .03       0  4957.1    .032       0  5134.2     .08       0
    5509     .08       0  5787.8     .03       0  6582.6     .06       0
  6612.6     .15       0
#XS Ineff= 2 , 0
       0  4443.8      70  5787.8       0   62.38
Permanent Ineff=
       F       T
#Block Obstruct= 2 ,-1
    4400    4887    55.5    5790    6580    49.8
Bank Sta=4915.2,5078.8
XS Rating Curve= 0 ,0
Exp/Cntr=0.3,0.1

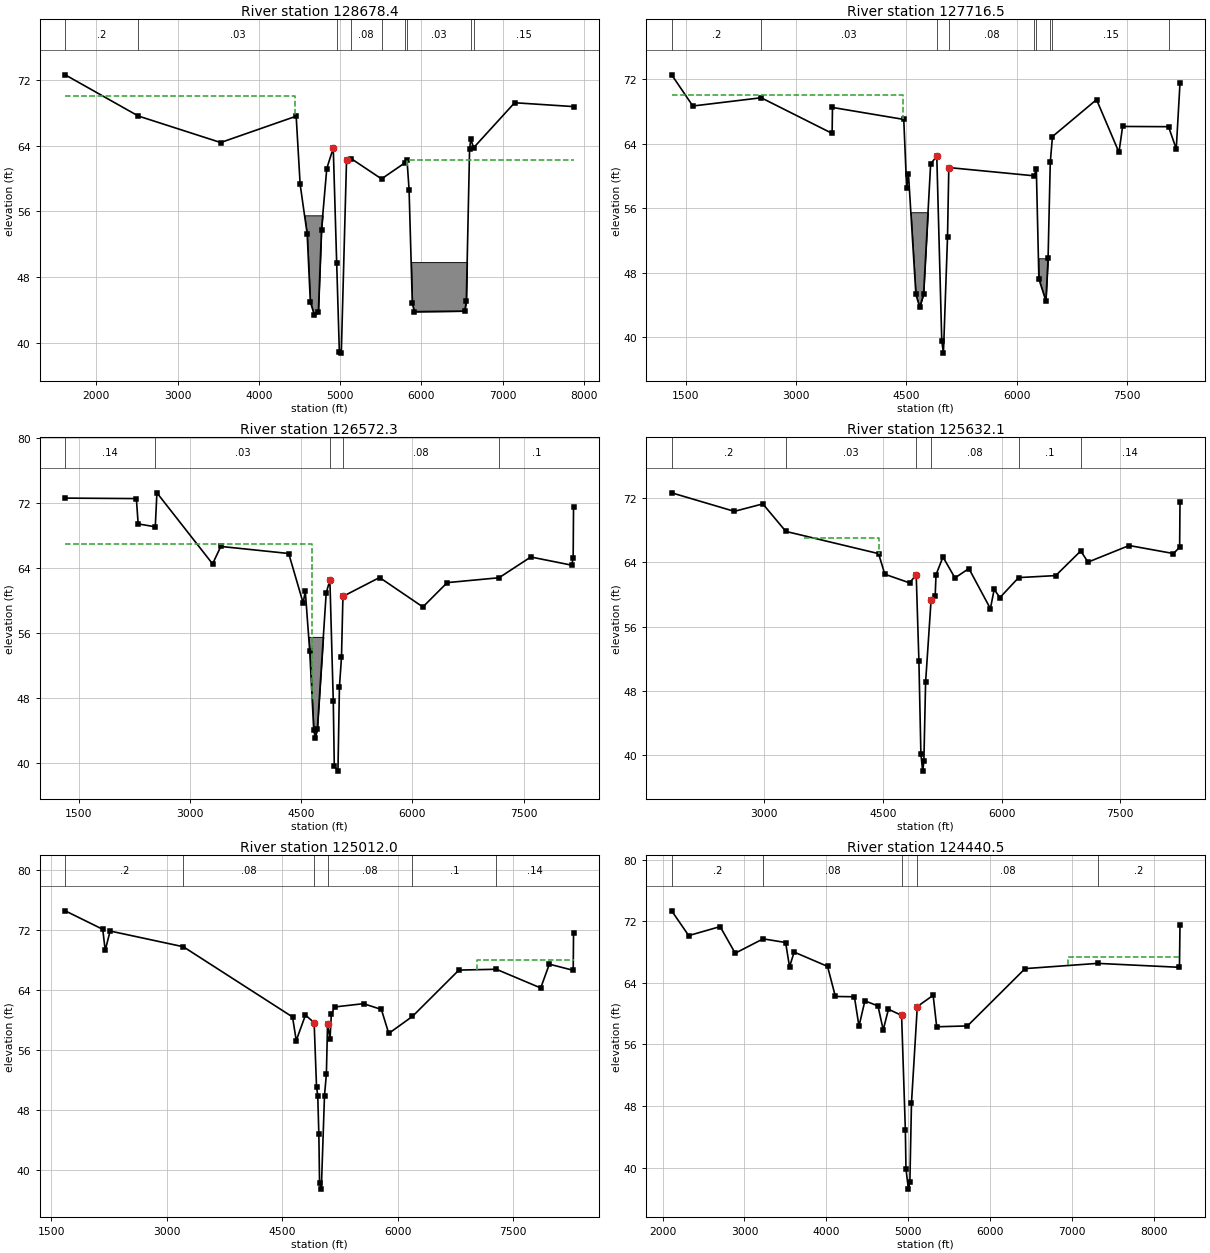
Type RM Length L Ch R = 1 ,128678.4,900.6,961.9,975.7
BEGIN DESCRIPTION:
Cross Section 128678.4 - Blocked Obstruction to limit conveyance in detention pond.
END DESCRIPTION:
XS GIS Cut Line= 5
      3132122.94     13903468.92      3132133.38      13901159.1
      3132133.38     13899888.78      3132062.81     13899200.68
 3132096.0753472 13897217.937072
#Sta/Elev= 30
  1616.8   72.62  2516.8    67.6  3529.8   64.37  4458.8   67.58  4507.8   59.27
    4594   53.24  4633.1   44.96  4683.7   43.31  4731.7   43.68  4770.6   53.77
  4835.3    61.2  4915.2   63.71  4957.1   49.75  4990.3   38.83  5014.1   38.71
  5078.8    62.3  5134.2   62.42    5509   59.94  5793.2   61.87  5823.1    62.2
  5848.1   58.61    5888   44.76    5913   43.76  6532.6   43.83  6552.6   45.06
  6592.6   63.58  6607.6   64.77  6642.5   63.74  7147.2   69.22  7871.7   68.75
#Mann= 9 ,-1 , 0
  1616.8      .2       0  2516.8     .03       0  4957.1    .032       0
  5134.2     .08       0    5509     .08       0  5793.2     .06       0
  5823.1     .03       0  6607.6     .06       0  6642.5     .15       0
#XS Ineff= 2 , 0
       0  4443.8      70  5828.1       0   62.22
Permanent Ineff=
       F       T
#Block Obstruct= 2 ,-1
    4400    4887    55.5  5823.1  6607.6    49.8
Bank Sta=4915.2,5078.8
XS Rating Curve= 0 ,0
Exp/Cntr=0.3,0.1

Type RM Length L Ch R = 1 ,127716.5,1028.8,1144.2,1494.3
BEGIN DESCRIPTION:
Cross Section 127716.5 - Blocked Obstruction to limit conveyance in detention pond.
END DESCRIPTION:
XS GIS Cut Line= 6
      3132777.78      13903807.5      3132874.24     13901710.83
      3132978.78     13901083.63      3133118.16     13899933.77
      3133135.58     13899459.01 3133179.184064813896910.7794212
#Sta/Elev= 30
  1306.2   72.51  1594.2   68.65  2524.2   69.67  3489.2   65.26  3494.2   68.47
  4464.2   66.99  4503.7   58.45  4528.1   60.26  4629.2   45.32  4681.3   43.75
  4733.6   45.36    4830   61.49  4913.6   62.43  4981.3   39.57    5004   38.06
  5059.5   52.42  5077.3   61.03    6238   60.01    6268   60.86  6302.9   47.23
  6397.9   44.54  6427.8   49.78  6457.8   61.68  6487.8   64.87  7087.4   69.44
  7392.3   62.92  7442.3   66.12    8067   66.09    8172   63.34  8222.9    71.5
#Mann= 9 ,-1 , 0
  1306.2      .2       0  2524.2     .03       0  4913.6    .032       0
  5077.3     .08       0    6238     .06       0    6268     .03       0
  6457.8     .06       0  6487.8     .15       0    8067     .14       0
#XS Ineff= 3 ,-1
    1000  4447.8      70    6268    6500   60.86  7087.4  8222.9   69.44
Permanent Ineff=
       F       T       F
#Block Obstruct= 2 ,-1
    4400    4887    55.5    6268    6460    49.8
Bank Sta=4913.6,5077.3
XS Rating Curve= 0 ,0
Exp/Cntr=0.3,0.1

Type RM Length L Ch R = 1 ,126572.3,1106.6,940.2,719.2
BEGIN DESCRIPTION:
XS 126572.3-Blocked Obstruction to limit conveyance in detention pond.
END DESCRIPTION:
XS GIS Cut Line= 6
      3133834.46     13903851.14      3133928.29     13901170.74
      3134128.64     13900604.52      3134224.46     13900282.21
      3134276.73     13899968.61      3134409.93     13897051.51
#Sta/Elev= 30
    1317   72.61    2277   72.55    2301   69.43    2532   69.07    2554   73.26
    3305    64.5    3416   66.65    4332   65.78    4527   59.67  4555.3   61.16
  4615.8    53.7  4669.2   44.08  4689.2   43.08  4717.7    44.1  4837.6   60.93
  4887.5   62.48    4933   47.62  4946.8   39.58  4996.1   38.95  5016.2   49.34
  5043.8   52.96  5063.4   60.49  5557.8   62.82  6141.8   59.19  6469.8   62.19
    7169   62.79  7597.8   65.35  8149.8   64.34    8169   65.24    8174    71.5
#Mann= 5 ,-1 , 0
    1317     .14       0    2532     .03       0  4887.5    .032       0
  5063.4     .08       0    7169      .1       0
#XS Ineff= 2 , 0
       0    4650      67               0
Permanent Ineff=
       F       F
#Block Obstruct= 1 ,-1
    4400    4887    55.5
Bank Sta=4887.5,5063.4
XS Rating Curve= 0 ,0
Exp/Cntr=0.3,0.1

Type RM Length L Ch R = 1 ,125632.1,548.5,620.1,622.1
BEGIN DESCRIPTION:
Cross Section 125632.1
END DESCRIPTION:
XS GIS Cut Line= 6
      3135229.21     13903366.86      3135287.22     13901318.83
      3135121.71     13900778.74      3135173.97     13900334.48
      3135147.84      13899959.9      3135179.21     13896971.63
#Sta/Elev= 30
  1829.7   72.67  2621.7   70.36  2981.7   71.29  3272.8   67.86  4444.7   65.09
  4523.7   62.52  4837.7   61.44  4920.5   62.47  4954.4   51.75  4979.8    40.1
  5002.3   37.97  5017.4   39.23  5039.2   49.05  5108.9   59.35  5160.3    59.8
  5170.7   62.45  5258.7   64.67  5410.2   62.06  5586.2   63.23  5858.2   58.23
  5906.2   60.63  5978.2    59.6  6214.9    62.1  6683.8   62.35    7000   65.42
  7091.8   64.03  7611.8    66.1  8171.8    65.1  8250.1   65.88  8254.7    71.5
#Mann= 6 ,-1 , 0
  1829.7      .2       0  3272.8     .03       0  4920.5    .032       0
  5108.9     .08       0  6214.9      .1       0    7000     .14       0
#XS Ineff= 1 ,-1
    3500  4444.7      67
Permanent Ineff=
       F
Bank Sta=4920.5,5108.9
XS Rating Curve= 0 ,0
Exp/Cntr=0.3,0.1

Type RM Length L Ch R = 1 ,125012.0,564.5,571.5,623.5
BEGIN DESCRIPTION:
Cross Section 125012.0
END DESCRIPTION:
XS GIS Cut Line= 6
      3135529.12     13903454.52      3135653.08     13901074.92
       3135670.5     13900621.94      3135766.33     13900299.63
      3135783.75     13899977.32      3135830.96     13896862.89
#Sta/Elev= 30
  1678.3    74.5  2166.3   72.04  2198.3   69.24  2262.3   71.81  3213.7   69.72
  4634.4   60.37  4682.4   57.23  4802.4   60.62  4915.3   59.61  4946.3    51.1
  4962.2   49.87  4976.5   44.76  4985.7   38.25  5008.7   37.45    5050   49.91
  5074.6   52.79  5089.6    59.4  5122.1   57.47  5138.7   60.71  5181.5    61.7
  5557.5   62.14  5789.5   61.37  5885.5   58.18  6194.2   60.45  6797.5   66.61
  7284.2   66.72  7861.5   64.23  7973.5    67.4  8284.2   66.58  8288.3    71.5
#Mann= 6 ,-1 , 0
  1678.3      .2       0  3213.7     .08       0  4915.3    .032       0
  5089.6     .08       0  6194.2      .1       0  7284.2     .14       0
#XS Ineff= 2 , 0
       0                  7029.5       0      68
Permanent Ineff=
       F       F
Bank Sta=4915.3,5089.6
XS Rating Curve= 0 ,0
Exp/Cntr=0.3,0.1

Type RM Length L Ch R = 1 ,124440.5,896.2,780.4,648
BEGIN DESCRIPTION:
Cross Section 124440.5-Interpolated
END DESCRIPTION:
XS GIS Cut Line= 6
        3136088.     13903039.87      3136173.45     13900833.19
      3136321.35     13900407.97      3136376.82     13899871.82
      3136326.34     13898222.78      3136342.62     13896860.27
#Sta/Elev= 30
  2111.1   73.37  2319.1   70.15  2703.1   71.32  2887.1   67.86  3228.5   69.73
  3503.1   69.25  3551.1   66.09  3607.1   68.01  4015.1   66.15  4111.1   62.24
  4343.4    62.2  4399.4   58.37  4471.4   61.67  4631.4   61.01  4695.4    57.9
  4759.4   60.58    4920   59.78  4965.9   44.89  4973.5   39.83  5003.1    37.2
    5021   38.12  5040.7   48.39  5111.9   60.93  5305.6   62.39  5348.6    58.3
  5724.6   58.41  6428.6   65.86  7314.4   66.54  8314.4   66.03  8321.1    71.5
#Mann= 5 , 1 , 0
  2111.1      .2       0  3228.5     .08       0    4920    .032       0
  5111.9     .08       0  7314.4      .2       0
#XS Ineff= 2 , 0
       0                  6958.5       0   67.35
Permanent Ineff=
       F       F
Bank Sta=4920,5111.9
XS Rating Curve= 0 ,0
Exp/Cntr=0.3,0.1