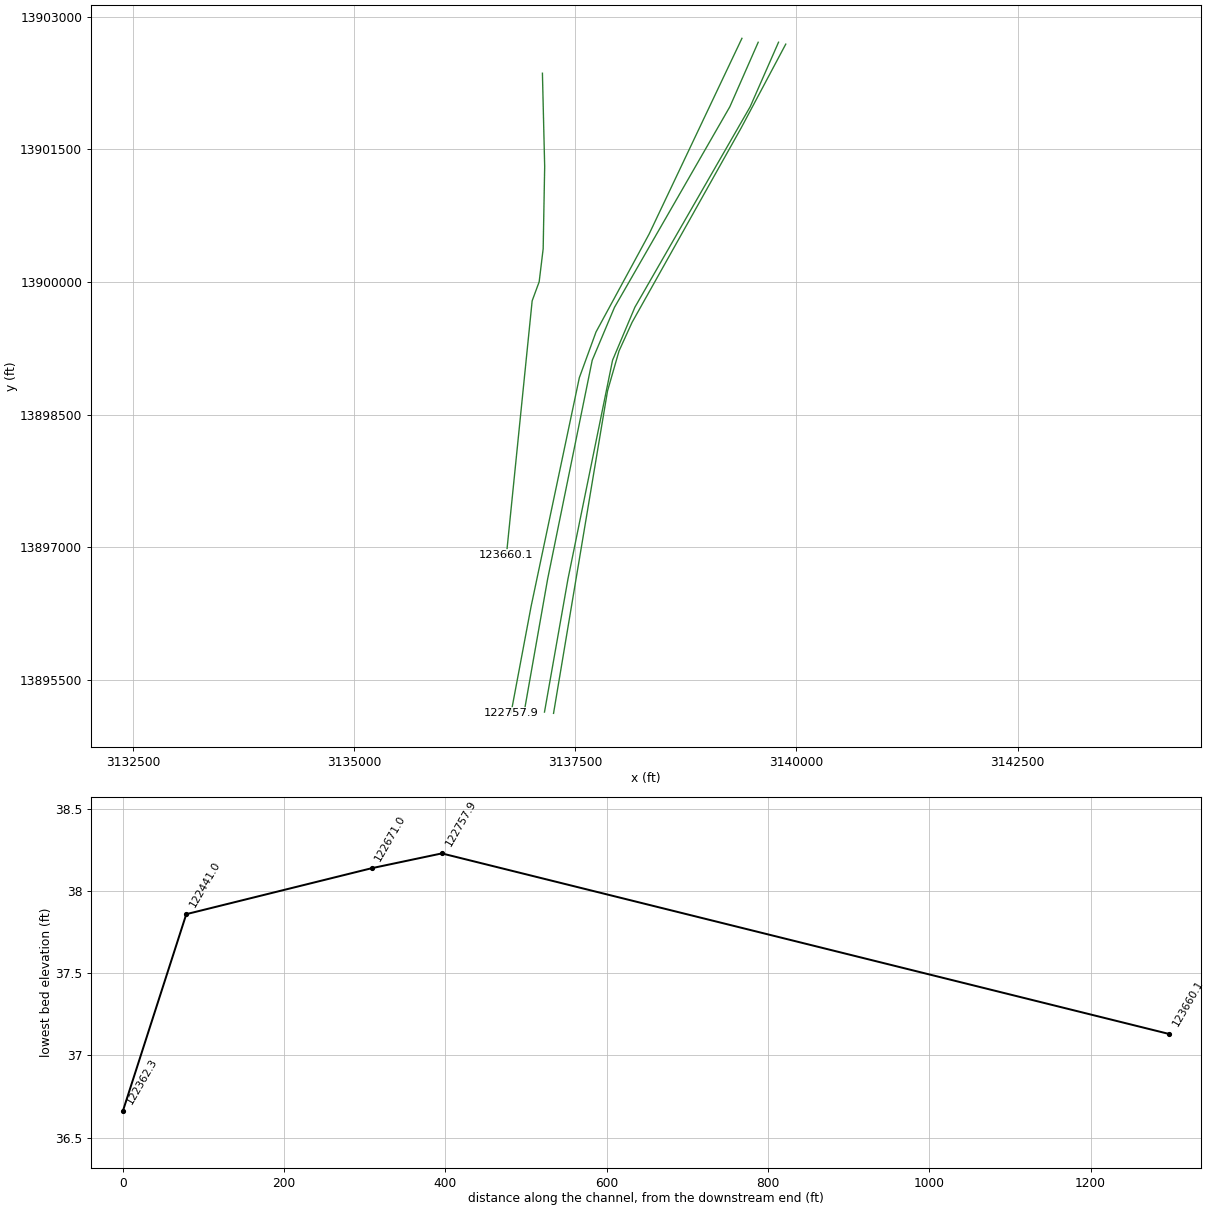
HEC-RAS study P100-00-00.prj: P100-00-00

--- P100-00-00.g01 (geometry) --- (continued)

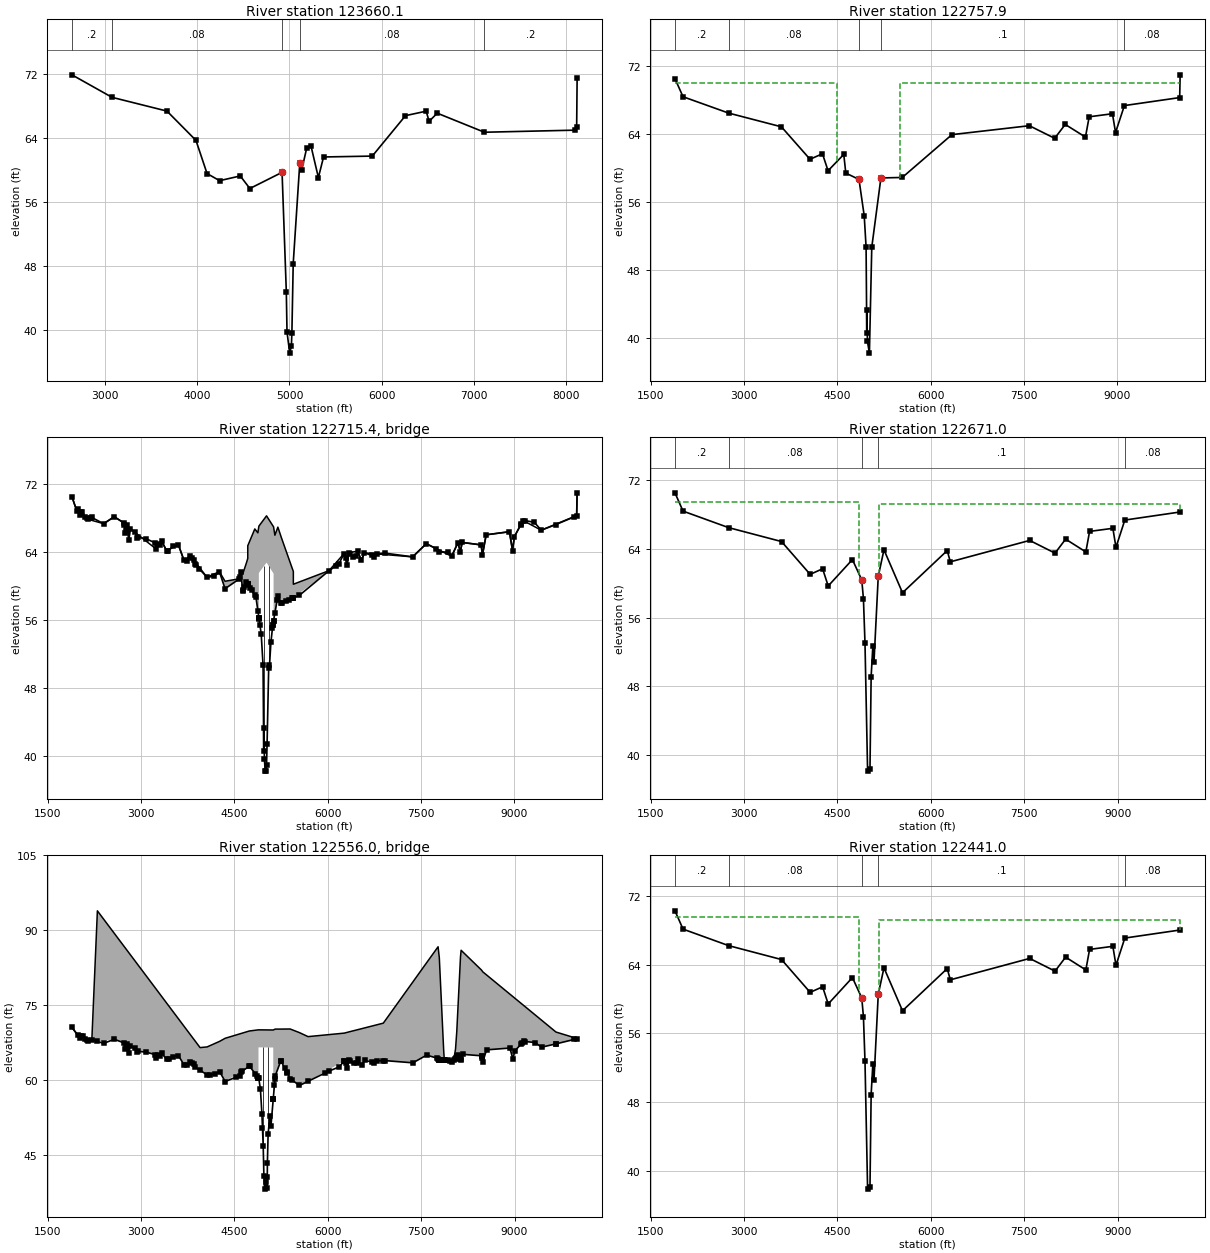
Type RM Length L Ch R = 1 ,123660.1,1087.9,902.2,700.5
BEGIN DESCRIPTION:
Cross Section 123660.1
END DESCRIPTION:
XS GIS Cut Line= 6
      3137127.64     13902361.69      3137153.11     13901305.67
      3137136.12     13900376.96      3137090.82     13900003.21
      3137011.54     13899788.02      3136721.01      13896918.7
#Sta/Elev= 30
  2642.6   71.89  3077.1   69.08  3672.7   67.36  3986.9    63.7  4106.9   59.56
  4242.9   58.67  4466.9   59.26  4570.9   57.69    4920   59.71  4965.9   44.82
  4973.5   39.76  5003.1   37.13    5021   38.05  5026.4   39.67  5040.7   48.32
  5111.9   60.86  5133.2   60.03  5188.3   62.81  5233.6   62.99  5313.6   59.06
  5369.6   61.63  5897.6   61.74  6257.6   66.79  6481.6   67.35  6513.6   66.08
  6601.6    67.1  7112.5   64.72  8097.6   64.98  8112.5   65.33  8117.6    71.5
#Mann= 5 , 1 , 0
  2642.6      .2       0  3077.1     .08       0    4920    .032       0
  5111.9     .08       0  7112.5      .2       0
#XS Ineff= 2 , 0
       0                  6481.6       0   67.35
Permanent Ineff=
       F       F
Bank Sta=4920,5111.9
XS Rating Curve= 0 ,0
Exp/Cntr=0.5,0.3

Type RM Length L Ch R = 1 ,122757.9,86.9,86.9,86.9
BEGIN DESCRIPTION:
Upstream Section of Bridge/Culvert/Weir
END DESCRIPTION:
XS GIS Cut Line= 6
      3139383.55     13902756.24      3138333.81     13900542.67
      3137733.55     13899435.58      3137544.96     13898918.33
      3136999.32     13896331.67      3136773.63     13895131.42
#Sta/Elev= 30
  1888.4   70.54  2018.4   68.41  2750.4   66.49  3600.7   64.87  4060.7   61.05
  4260.7    61.7  4350.7    59.7  4603.4   61.62 4636.19   59.42  4848.1   58.68
 4932.45   54.38 4962.33   50.71 4973.24   40.58 4974.19   43.35 4984.24    39.6
 5015.76   38.23 5053.78    50.7 5200.74   58.85  5544.5   58.91  6342.9   63.95
  7587.8      65  7995.3   63.52  8165.3   65.15  8490.3   63.66  8550.3   66.05
  8924.4   66.41  8974.4    64.2  9116.5   67.37 10005.6   68.31 10013.4   70.99
#Mann= 5 , 1 , 0
  1888.4      .2       0  2750.4     .08       0  4848.1    .032       0
 5200.74      .1       0  9116.5     .08       0
#XS Ineff= 2 , 0
       0    4500      70    5500       0      70
Permanent Ineff=
       F       F
Bank Sta=4848.1,5200.74
XS Rating Curve= 0 ,0
Exp/Cntr=0.5,0.3

Type RM Length L Ch R = 3 ,122715.4,,,
BEGIN DESCRIPTION:
EASTEX FREEWAY (SOUTHBOUND)   Skew Angle 30 Degrees
Structure ID: P00-33
END DESCRIPTION:
Bridge Culvert--1,0,-1,-1, 0
Deck Dist Width WeirC Skew NumUp NumDn MinLoCord MaxHiCord MaxSubmerge Is_Ogee
10,65,2.6,0, 60, 60, , , 0.95, 0, 1,1,,
  1888.4  1968.4  2148.4  2398.4  2568.4  2724.5  2744.5  2774.5  2804.5  2824.5
  3240.7  3330.7  3410.7  3600.7  3690.7  3790.7  4060.7  4260.7  4350.7  4583.4
  4603.4 4636.19 4694.04 4716.19  4716.3  4829.6  4878.8 4894.95 4895.04  5018.3
 5131.78 5131.89  5152.3 5200.74  5258.4  5449.4 5449.51  6023.1  6262.9  6312.9
  6342.9  6482.9  6542.9  6592.9  7367.8  7587.8  7995.3  8095.3  8135.3  8165.3
  8470.3  8490.3  8550.3  8924.4  8974.4  9004.4  9144.4  9435.6 10005.6 10013.4
   70.55   68.83   67.88   67.37   68.19   67.46   66.33   67.25   65.47   66.79
    64.4   65.34   64.19   64.89   63.05    63.6   61.07   61.72   60.59   60.89
   61.64   61.46   62.74   63.27   64.77   66.75   66.29   67.07   67.08   68.29
   66.99   66.98   66.01   66.96    65.7   61.74   60.24   61.84   63.83   62.52
   63.96   64.13   63.05   63.93   63.46   65.01   63.53   65.11   64.09   65.16
   64.87   63.67   66.06   66.42   64.21   65.84   67.74    66.6   68.32      71
   70.55   68.83   67.88   67.36   68.18   67.45   66.32   67.24   65.46   66.78
   64.39   65.33   64.18   64.88   63.04   63.59   61.06   61.71   59.71   60.88
   61.63   59.43   60.47   60.23   60.23   58.92    57.1   56.27   61.58   62.79
   61.49   55.97   56.82   58.86   58.04   58.63   58.63   61.83   63.83   62.52
   63.96   64.13   63.05   63.93   63.46   65.01   63.53   65.11   64.09   65.16
   64.87   63.67   66.06   66.42   64.21   65.84   67.74    66.6   68.32      71
  1888.4  1968.4  2148.4  2398.4  2568.4  2724.5  2744.5  2774.5  2804.5  2824.5
  3240.7  3330.7  3410.7  3600.7  3690.7  3790.7  4060.7  4260.7  4350.7  4583.4
  4603.4 4636.19 4694.04 4716.19  4716.3  4829.6  4878.8 4894.95 4895.04  5018.3
 5131.78 5131.89  5152.3 5200.74  5258.4  5449.4 5449.51  6023.1  6262.9  6312.9
  6342.9  6482.9  6542.9  6592.9  7367.8  7587.8  7995.3  8095.3  8135.3  8165.3
  8470.3  8490.3  8550.3  8924.4  8974.4  9004.4  9144.4  9435.6 10005.6 10013.4
   70.55   68.83   67.88   67.37   68.19   67.46   66.33   67.25   65.47   66.79
    64.4   65.34   64.19   64.89   63.05    63.6   61.07   61.72   60.59   60.89
   61.64   61.46   62.74   63.27   64.77   66.75   66.29   67.07   67.08   68.29
   66.99   66.98   66.01   66.96    65.7   61.74   60.24   61.84   63.83   62.52
   63.96   64.13   63.05   63.93   63.46   65.01   63.53   65.11   64.09   65.16
   64.87   63.67   66.06   66.42   64.21   65.84   67.74    66.6   68.32      71
   70.43   68.71   67.76   67.24   68.06   67.33    66.2   67.12   65.34   66.66
   64.27   65.21   64.06   64.76   62.92   63.47   60.94   61.59   59.59   60.76
   61.51   59.31   60.35   60.11   60.11    58.8   56.98   56.15   61.46   62.67
   61.37   55.85    56.7   58.74   57.92   58.51   58.51   61.71   63.71    62.4
   63.84   64.01   62.93   63.81   63.34   64.89   63.41   64.99   63.97   65.04
   64.75   63.55   65.94    66.3   64.09   65.72   67.62   66.48    68.2   70.88
Pier Skew, UpSta & Num, DnSta & Num=  ,4974.2, 2 ,4974.2, 2 , 0 , 0 , 0 ,,
       2       2
   39.63   63.63
       2       2
   39.51   63.51
Pier Skew, UpSta & Num, DnSta & Num=  ,5053.8, 2 ,5053.8, 2 , 0 , 0 , 0 ,,
       2       2
   49.36   63.62
       2       2
   49.24    63.5
Abutment Skew #Up #Dn= , 2 , 2
  5118.9 5131.98
   55.42   61.49
  5118.9 5131.98
    55.3   61.37
BR Coef= 1 , 1 , 0 ,1.25, 0 ,,,0.8,-1,2,0,
WSPro=,,,, 1 ,,,, 0 ,,,, 0 ,,,,-1 ,-1 ,-1 , 0 , 0 , 0 , 0 , 0
BR U #Sta/Elev= 137
  1888.4   70.55  1968.4   68.83  1978.4   69.05  2018.4   68.42  2038.4   68.76
  2058.4   68.79  2098.4   68.16  2128.4   68.05  2148.4   67.88  2201.8   68.08
  2208.4    68.1  2398.4   67.36  2568.4   68.18  2724.5   67.45  2727.8   67.26
  2744.5   66.32  2750.4    66.5  2774.5   67.24  2804.5   65.46  2824.5   66.78
  2904.5   66.34  2934.5   65.72  2954.5   65.77  3084.5   65.59  3220.7   65.12
  3240.7   64.39  3270.7   64.98  3300.7   64.85  3330.7   65.33  3410.7   64.18
  3440.7   64.18  3510.7   64.71  3600.7   64.88  3690.7   63.04  3740.7   62.95
  3790.7   63.59  3820.7   63.34  3850.7   63.14  3870.7   62.57  3876.8   62.52
  3931.8   62.08  4060.7   61.06  4180.7   61.18  4260.7   61.71  4350.7   59.71
  4583.4   60.88  4590.1   61.13  4603.4   61.63 4636.19   59.43 4636.97    59.6
  4656.7    59.9 4694.04   60.47 4716.19   60.23  4716.3   60.23 4716.41   60.23
  4725.1   60.14 4756.91    59.8  4780.7   59.51  4829.6   58.92  4848.1   58.69
  4878.8    57.1 4894.95   56.27 4895.04   56.26 4895.13   56.26  4896.6   56.18
  4912.1   55.41 4932.45   54.39 4962.33   50.72 4973.24   40.59 4974.19   43.36
 4984.24   39.61  4997.4   38.25 5015.76   38.24  5018.3   38.96 5026.85   41.39
 5053.78   50.71 5063.74   50.42 5089.28   53.45    5114   55.09  5118.8   55.41
  5118.9   55.42 5131.78   55.96 5131.89   55.97  5152.3   56.82  5190.4   58.43
 5200.74   58.86  5258.4   58.04  5260.7   58.05  5326.7   58.25  5378.4   58.41
  5431.4   58.57 5449.29   58.63  5449.4   58.63 5449.51   58.63  5544.5   58.92
  6023.1   61.83  6135.5   62.41  6183.1   62.65  6262.9   63.83  6292.9   63.34
  6312.9   62.52  6342.9   63.96  6362.9    63.8  6412.9   63.45  6462.9   63.51
  6482.9   64.13  6542.9   63.05  6592.9   63.93  6712.9   63.63  6742.9   63.44
  6792.9   63.84  6922.9    63.9  7367.8   63.46  7587.8   65.01  7747.8   64.42
  7785.3   64.02  7935.3   64.04  7995.3   63.53  8095.3   65.11  8135.3   64.09
  8165.3   65.16  8470.3   64.87  8490.3   63.67  8550.3   66.06  8924.4   66.42
  8974.4   64.21  9004.4   65.84  9104.4   67.22  9116.5   67.38  9144.4   67.74
  9174.4   67.73  9325.6   67.53  9435.6    66.6  9665.6   67.25  9955.6   68.14
 10005.6   68.32 10013.4      71
BR U #Mann= 5
  1888.4      .2  2750.4     .08  4848.1    .032 5200.74      .1  9116.5     .08
BR U Banks=4848.1,5200.74
BR D #Sta/Elev= 137
  1888.4   70.43  1968.4   68.71  1978.4   68.93  2018.4    68.3  2038.4   68.64
  2058.4   68.67  2098.4   68.04  2128.4   67.93  2148.4   67.76  2201.8   67.96
  2208.4   67.98  2398.4   67.24  2568.4   68.06  2724.5   67.33  2727.8   67.14
  2744.5    66.2  2750.4   66.38  2774.5   67.12  2804.5   65.34  2824.5   66.66
  2904.5   66.22  2934.5    65.6  2954.5   65.65  3084.5   65.47  3220.7      65
  3240.7   64.27  3270.7   64.86  3300.7   64.73  3330.7   65.21  3410.7   64.06
  3440.7   64.06  3510.7   64.59  3600.7   64.76  3690.7   62.92  3740.7   62.83
  3790.7   63.47  3820.7   63.22  3850.7   63.02  3870.7   62.45  3876.8    62.4
  3931.8   61.96  4060.7   60.94  4180.7   61.06  4260.7   61.59  4350.7   59.59
  4583.4   60.76  4590.1   61.01  4603.4   61.51 4636.19   59.31 4636.97   59.48
  4656.7   59.78 4694.04   60.35 4716.19   60.11  4716.3   60.11 4716.41   60.11
  4725.1   60.02 4756.91   59.68  4780.7   59.39  4829.6    58.8  4848.1   58.57
  4878.8   56.98 4894.95   56.15 4895.04   56.14 4895.13   56.14  4896.6   56.06
  4912.1   55.29 4932.45   54.27 4962.33    50.6 4973.24   40.47 4974.19   43.24
 4984.24   39.49  4997.4   38.13 5015.76   38.12  5018.3   38.84 5026.85   41.27
 5053.78   50.59 5063.74    50.3 5089.28   53.33    5114   54.97  5118.8   55.29
  5118.9    55.3 5131.78   55.84 5131.89   55.85  5152.3    56.7  5190.4   58.31
 5200.74   58.74  5258.4   57.92  5260.7   57.93  5326.7   58.13  5378.4   58.29
  5431.4   58.45 5449.29   58.51  5449.4   58.51 5449.51   58.51  5544.5    58.8
  6023.1   61.71  6135.5   62.29  6183.1   62.53  6262.9   63.71  6292.9   63.22
  6312.9    62.4  6342.9   63.84  6362.9   63.68  6412.9   63.33  6462.9   63.39
  6482.9   64.01  6542.9   62.93  6592.9   63.81  6712.9   63.51  6742.9   63.32
  6792.9   63.72  6922.9   63.78  7367.8   63.34  7587.8   64.89  7747.8    64.3
  7785.3    63.9  7935.3   63.92  7995.3   63.41  8095.3   64.99  8135.3   63.97
  8165.3   65.04  8470.3   64.75  8490.3   63.55  8550.3   65.94  8924.4    66.3
  8974.4   64.09  9004.4   65.72  9104.4    67.1  9116.5   67.26  9144.4   67.62
  9174.4   67.61  9325.6   67.41  9435.6   66.48  9665.6   67.13  9955.6   68.02
 10005.6    68.2 10013.4   70.88
BR D #Mann= 5
  1888.4      .2  2750.4     .08  4848.1    .032 5200.74      .1  9116.5     .08
BR D Banks=4848.1,5200.74
BC Design=,, 0 ,, 0 ,,,,,,
BC HTab HWMax=70.99
BC Use User HTab Curves=0
BC User HTab FreeFlow(D)= 0

Type RM Length L Ch R = 1 ,122671.0,230,230,230
BEGIN DESCRIPTION:
Upstream Section of Bridge/Culvert/Weir
END DESCRIPTION:
XS GIS Cut Line= 6
      3139567.52     13902711.99      3139247.13     13901983.03
      3137942.91     13899714.97      3137690.77     13899116.13
      3137186.49     13896642.01      3136920.99     13895137.51
#Sta/Elev= 30
  1888.4   70.53  2018.4    68.4  2750.4   66.48  3600.7   64.86  4060.7   61.04
  4260.7   61.69  4350.7   59.69 4739.51   62.76 4889.59    60.4  4916.6   58.23
 4941.55   53.09 4983.63   38.14 5021.91   38.36 5040.53   49.15 5068.33   52.76
 5086.25   50.83 5154.84   60.81 5246.55    63.9  5544.5    58.9  6262.9   63.81
  6312.9    62.5  7587.8   64.99  7995.3   63.51  8165.3   65.14  8490.3   63.65
  8550.3   66.04  8924.4    66.4  8974.4   64.19  9116.5   67.36 10005.6    68.3
#Mann= 5 , 1 , 0
  1888.4      .2       0  2750.4     .08       0 4889.59    .032       0
 5154.84      .1       0  9116.5     .08       0
#XS Ineff= 2 , 0
       0    4850    69.5    5160       0    69.2
Permanent Ineff=
       F       F
Bank Sta=4889.59,5154.84
XS Rating Curve= 0 ,0
Exp/Cntr=0.5,0.3

Type RM Length L Ch R = 3 ,122556.0,,,
BEGIN DESCRIPTION:
HIGHWAY 59    Skew Angle 30 Degrees
Structure ID: P00-32
END DESCRIPTION:
Bridge Culvert--1,0,-1,-1, 0
Deck Dist Width WeirC Skew NumUp NumDn MinLoCord MaxHiCord MaxSubmerge Is_Ogee
10,210,2.6,0, 60, 60, , , 0.95, 0, 1,1,,
  1888.4  2018.4  2208.4  2297.5  2568.4  2724.5  2744.5  2774.5  2804.5  2824.5
  3240.7  3330.7  3410.7  3600.7  3690.7  3790.7  3947.5  4060.7  4260.7  4350.7
 4739.51 4885.94 4886.03 5123.12 5123.23 5154.84 5246.55 5394.29  5544.5  5682.6
  6262.9  6312.9  6342.9  6482.9  6542.9  6592.9  6891.5  7367.8  7587.8  7771.5
  7791.5  7861.7  7871.7  7995.3  8021.7  8051.7  8071.7  8131.7  8141.7  8165.3
  8470.3  8490.3  8550.3  8924.4  8974.4  9004.4  9144.4  9435.6  9665.6 10005.6
   70.55   68.42    68.1    93.9    89.4   86.81   86.48   85.98   85.48   85.15
   78.24   76.74   75.41   72.26   70.76    69.1    66.5   66.64   67.75   68.37
   69.83   70.06   70.06   70.03   70.03   70.21   70.21   70.23    69.5    68.7
    69.4   69.56   69.66    70.1   70.29   70.45    71.4   79.68   83.51    86.7
    84.5    65.9   64.04   63.54   63.96    66.2    69.7    84.7      86   85.71
   82.02   81.67   81.06   77.22   76.71    76.4   74.97   71.98   69.62   68.32
   70.54   68.41   68.09   67.74   68.17   67.44   66.31   67.23   65.45   66.77
   64.38   65.32   64.17   64.87   63.03   63.58   61.95   61.05    61.7    59.7
   62.77   60.47   66.55   66.52   56.22   60.82   63.91   60.27   58.91   59.75
   63.82   62.51   63.95   64.12   63.04   63.92   63.88   63.45      65   64.16
   64.01   64.02   64.02   63.52   63.94   64.41   64.73   64.17   64.31   65.15
   64.86   63.66   66.05   66.41    64.2   65.83   67.73   66.59   67.24   68.31
  1888.4  2018.4  2208.4  2297.5  2568.4  2724.5  2744.5  2774.5  2804.5  2824.5
  3240.7  3330.7  3410.7  3600.7  3690.7  3790.7  3947.5  4060.7  4260.7  4350.7
 4739.51 4885.94 4886.03 5123.12 5123.23 5154.84 5246.55 5394.29  5544.5  5682.6
  6262.9  6312.9  6342.9  6482.9  6542.9  6592.9  6891.5  7367.8  7587.8  7771.5
  7791.5  7861.7  7871.7  7995.3  8021.7  8051.7  8071.7  8131.7  8141.7  8165.3
  8470.3  8490.3  8550.3  8924.4  8974.4  9004.4  9144.4  9435.6  9665.6 10005.6
   70.55   68.42    68.1    93.9    89.4   86.81   86.48   85.98   85.48   85.15
   78.24   76.74   75.41   72.26   70.76    69.1    66.5   66.64   67.75   68.37
   69.83   70.06   70.06   70.03   70.03   70.21   70.21   70.23    69.5    68.7
    69.4   69.56   69.66    70.1   70.29   70.45    71.4   79.68   83.51    86.7
    84.5    65.9   64.04   63.54   63.96    66.2    69.7    84.7      86   85.71
   82.02   81.67   81.06   77.22   76.71    76.4   74.97   71.98   69.62   68.32
    70.4   68.27   67.95    67.6   68.03    67.3   66.17   67.09   65.31   66.63
   64.24   65.18   64.03   64.73   62.89   63.44   61.81   60.91   61.56   59.56
   62.63   60.33   66.41   66.38   56.08   60.68   63.77   60.13   58.77   59.61
   63.68   62.37   63.81   63.98    62.9   63.78   63.74   63.31   64.86   64.02
   63.87   63.88   63.88   63.38    63.8   64.27   64.59   64.03   64.17   65.01
   64.72   63.52   65.91   66.27   64.06   65.69   67.59   66.45    67.1   68.17
Pier Skew, UpSta & Num, DnSta & Num=  ,4961.7, 2 ,4961.7, 2 , 0 , 0 , 0 ,,
       3       3
   44.94   67.74
       3       3
    44.8    67.6
Pier Skew, UpSta & Num, DnSta & Num=  ,5040.5, 2 ,5040.5, 2 , 0 , 0 , 0 ,,
       3       3
   47.41   67.63
       3       3
   47.27   67.49
BR Coef= 1 , 1 , 0 ,1.25, 0 ,,,0.8,0,2,0,
WSPro=,,,, 1 ,,,, 0 ,,,, 0 ,,,,-1 ,-1 ,-1 , 0 , 0 , 0 , 0 , 0
BR U #Sta/Elev= 144
  1888.4   70.54  1978.4   69.04  2018.4   68.41  2038.4   68.75  2058.4   68.78
  2098.4   68.15  2128.4   68.04  2148.4   67.87  2208.4   68.09  2297.5   67.74
  2398.4   67.35  2568.4   68.17  2724.5   67.44  2744.5   66.31  2750.4   66.49
  2774.5   67.23  2804.5   65.45  2824.5   66.77  2904.5   66.33  2934.5   65.71
  2954.5   65.76  3084.5   65.58  3220.7   65.11  3240.7   64.38  3270.7   64.97
  3300.7   64.84  3330.7   65.32  3410.7   64.17  3440.7   64.17  3510.7    64.7
  3600.7   64.87  3690.7   63.03  3740.7   62.94  3790.7   63.58  3820.7   63.33
  3850.7   63.13  3870.7   62.56  3947.5   61.95  4060.7   61.05  4106.8    61.1
  4180.7   61.17  4260.7    61.7  4350.7    59.7  4519.7   60.55  4583.4   60.87
  4603.4   61.62  4619.7   61.76 4739.51   62.77  4741.7   62.74  4833.5   61.29
  4868.4   60.74 4885.94   60.47 4886.03   60.47 4886.12   60.46 4889.59   60.41
  4916.6   58.24 4941.55    53.1    4950   50.44 4961.72   46.75 4972.72   40.82
 4983.63   38.15  5003.9   39.61 5021.91   38.37 5027.28   40.67 5029.18   43.48
 5040.53   49.16 5068.33   52.77 5086.25   50.84 5123.05   56.19 5123.12    56.2
 5123.23   56.22  5142.3      59  5150.5   60.19 5154.84   60.82 5246.55   63.91
  5251.2   63.79 5305.09   62.37  5341.3   61.62 5351.51   61.41 5394.29   60.27
  5420.8   60.03  5544.5   58.91  5682.6   59.75  5951.9   61.39  6023.1   61.82
  6183.1   62.64  6261.5    63.8  6262.9   63.82  6292.9   63.33  6312.9   62.51
  6342.9   63.95  6362.9   63.79  6412.9   63.44  6462.9    63.5  6482.9   64.12
  6542.9   63.04  6592.9   63.92  6712.9   63.62  6742.9   63.43  6792.9   63.83
  6891.5   63.88  6922.9   63.89  7367.8   63.45  7587.8      65  7747.8   64.41
  7771.5   64.16  7781.5   64.05  7785.3   64.01  7791.5   64.01  7831.7   64.02
  7861.7   64.02  7871.7   64.02  7881.7   64.02  7935.3   64.03  7961.7   63.81
  7995.3   63.52  8021.7   63.94  8041.7   64.25  8051.7   64.41  8071.7   64.73
  8095.3    65.1  8111.7   64.68  8131.7   64.17  8135.3   64.08  8141.7   64.31
  8165.3   65.15  8470.3   64.86  8471.7   64.78  8477.8   64.41  8490.3   63.66
  8550.3   66.05  8924.4   66.41  8974.4    64.2  9004.4   65.83  9104.4   67.21
  9116.5   67.37  9144.4   67.73  9174.4   67.72  9325.6   67.52  9435.6   66.59
  9665.6   67.24  9667.8   67.25  9955.6   68.13 10005.6   68.31
BR U #Mann= 5
  1888.4      .2  2750.4     .08 4889.59    .032 5154.84      .1  9116.5     .08
BR U Banks=4889.59,5154.84
BR D #Sta/Elev= 144
  1888.4    70.4  1978.4    68.9  2018.4   68.27  2038.4   68.61  2058.4   68.64
  2098.4   68.01  2128.4    67.9  2148.4   67.73  2208.4   67.95  2297.5    67.6
  2398.4   67.21  2568.4   68.03  2724.5    67.3  2744.5   66.17  2750.4   66.35
  2774.5   67.09  2804.5   65.31  2824.5   66.63  2904.5   66.19  2934.5   65.57
  2954.5   65.62  3084.5   65.44  3220.7   64.97  3240.7   64.24  3270.7   64.83
  3300.7    64.7  3330.7   65.18  3410.7   64.03  3440.7   64.03  3510.7   64.56
  3600.7   64.73  3690.7   62.89  3740.7    62.8  3790.7   63.44  3820.7   63.19
  3850.7   62.99  3870.7   62.42  3947.5   61.81  4060.7   60.91  4106.8   60.96
  4180.7   61.03  4260.7   61.56  4350.7   59.56  4519.7   60.41  4583.4   60.73
  4603.4   61.48  4619.7   61.62 4739.51   62.63  4741.7    62.6  4833.5   61.15
  4868.4    60.6 4885.94   60.33 4886.03   60.33 4886.12   60.32 4889.59   60.27
  4916.6    58.1 4941.55   52.96    4950    50.3 4961.72   46.61 4972.72   40.68
 4983.63   38.01  5003.9   39.47 5021.91   38.23 5027.28   40.53 5029.18   43.34
 5040.53   49.02 5068.33   52.63 5086.25    50.7 5123.05   56.05 5123.12   56.06
 5123.23   56.08  5142.3   58.86  5150.5   60.05 5154.84   60.68 5246.55   63.77
  5251.2   63.65 5305.09   62.23  5341.3   61.48 5351.51   61.27 5394.29   60.13
  5420.8   59.89  5544.5   58.77  5682.6   59.61  5951.9   61.25  6023.1   61.68
  6183.1    62.5  6261.5   63.66  6262.9   63.68  6292.9   63.19  6312.9   62.37
  6342.9   63.81  6362.9   63.65  6412.9    63.3  6462.9   63.36  6482.9   63.98
  6542.9    62.9  6592.9   63.78  6712.9   63.48  6742.9   63.29  6792.9   63.69
  6891.5   63.74  6922.9   63.75  7367.8   63.31  7587.8   64.86  7747.8   64.27
  7771.5   64.02  7781.5   63.91  7785.3   63.87  7791.5   63.87  7831.7   63.88
  7861.7   63.88  7871.7   63.88  7881.7   63.88  7935.3   63.89  7961.7   63.67
  7995.3   63.38  8021.7    63.8  8041.7   64.11  8051.7   64.27  8071.7   64.59
  8095.3   64.96  8111.7   64.54  8131.7   64.03  8135.3   63.94  8141.7   64.17
  8165.3   65.01  8470.3   64.72  8471.7   64.64  8477.8   64.27  8490.3   63.52
  8550.3   65.91  8924.4   66.27  8974.4   64.06  9004.4   65.69  9104.4   67.07
  9116.5   67.23  9144.4   67.59  9174.4   67.58  9325.6   67.38  9435.6   66.45
  9665.6    67.1  9667.8   67.11  9955.6   67.99 10005.6   68.17
BR D #Mann= 5
  1888.4      .2  2750.4     .08 4889.59    .032 5154.84      .1  9116.5     .08
BR D Banks=4889.59,5154.84
BC Design=,, 0 ,, 0 ,,,,,,
BC HTab HWMax=70.53
BC Use User HTab Curves=0
BC User HTab FreeFlow(D)= 0

Type RM Length L Ch R = 1 ,122441.0,78.7,78.7,78.7
BEGIN DESCRIPTION:
Downstream Section of Bridge/Culvert/Weir
END DESCRIPTION:
XS GIS Cut Line= 6
      3139797.52     13902712.12      3139477.13     13901983.17
      3138172.91     13899715.11      3137920.77     13899116.27
      3137416.49     13896642.15      3137150.99     13895137.65
#Sta/Elev= 30
  1888.4   70.25  2018.4   68.12  2750.4    66.2  3600.7   64.58  4060.7   60.76
  4260.7   61.41  4350.7   59.41 4739.51   62.48 4889.59   60.12  4916.6   57.95
 4941.55   52.81 4983.63   37.86 5021.91   38.08 5040.53   48.87 5068.33   52.48
 5086.25   50.55 5154.84   60.53 5246.55   63.62  5544.5   58.62  6262.9   63.53
  6312.9   62.22  7587.8   64.71  7995.3   63.23  8165.3   64.86  8490.3   63.37
  8550.3   65.76  8924.4   66.12  8974.4   63.91  9116.5   67.08 10005.6   68.02
#Mann= 5 , 1 , 0
  1888.4      .2       0  2750.4     .08       0 4889.59    .032       0
 5154.84      .1       0  9116.5     .08       0
#XS Ineff= 2 , 0
       0    4850    69.5    5160       0    69.2
Permanent Ineff=
       F       F
Bank Sta=4889.59,5154.84
XS Rating Curve= 0 ,0
Exp/Cntr=0.5,0.3

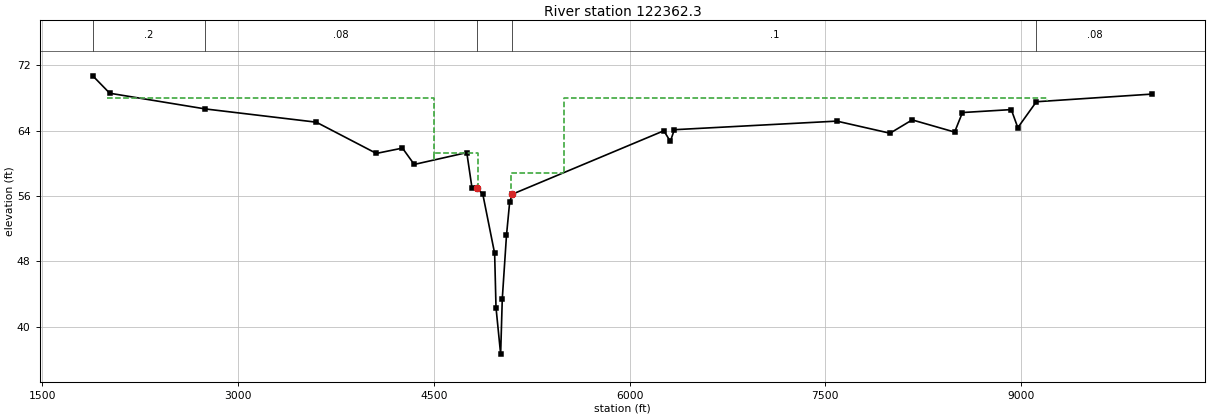
Type RM Length L Ch R = 1 ,122362.3,85,85,85
BEGIN DESCRIPTION:
Upstream Section of Bridge/Culvert/Weir
END DESCRIPTION:
XS GIS Cut Line= 6
       3139879.2      13902690.7      3139375.69     13901744.39
      3138141.25     13899544.49      3137994.02     13899221.71
      3137863.77     13898768.68      3137253.28     13895123.07
#Sta/Elev= 30
  1888.4    70.7  2018.4   68.57  2750.4   66.65  3600.7   65.03  4060.7   61.21
  4260.7   61.86  4350.7   59.86  4753.4   61.31  4793.4   56.98 4833.12   56.94
 4876.42    56.2 4966.75   48.98 4977.31   42.34 5012.73   36.66 5025.37   43.44
 5057.59    51.2 5082.18    55.3 5103.31   56.23  6262.9   63.98  6312.9   62.67
  6342.9   64.11  7587.8   65.16  7995.3   63.68  8165.3   65.31  8490.3   63.82
  8550.3   66.21  8924.4   66.57  8974.4   64.36  9116.5   67.53 10005.6   68.47
#Mann= 5 , 1 , 0
  1888.4      .2       0  2750.4     .08       0 4833.12    .032       0
 5103.31      .1       0  9116.5     .08       0
#XS Ineff= 4 ,-1
    2000    4500      68  4500.1    4840    61.2    5095    5500    58.8
  5500.1    9200      68
Permanent Ineff=
       F       F       F       F
Bank Sta=4833.12,5103.31
XS Rating Curve= 0 ,0
Exp/Cntr=0.5,0.3