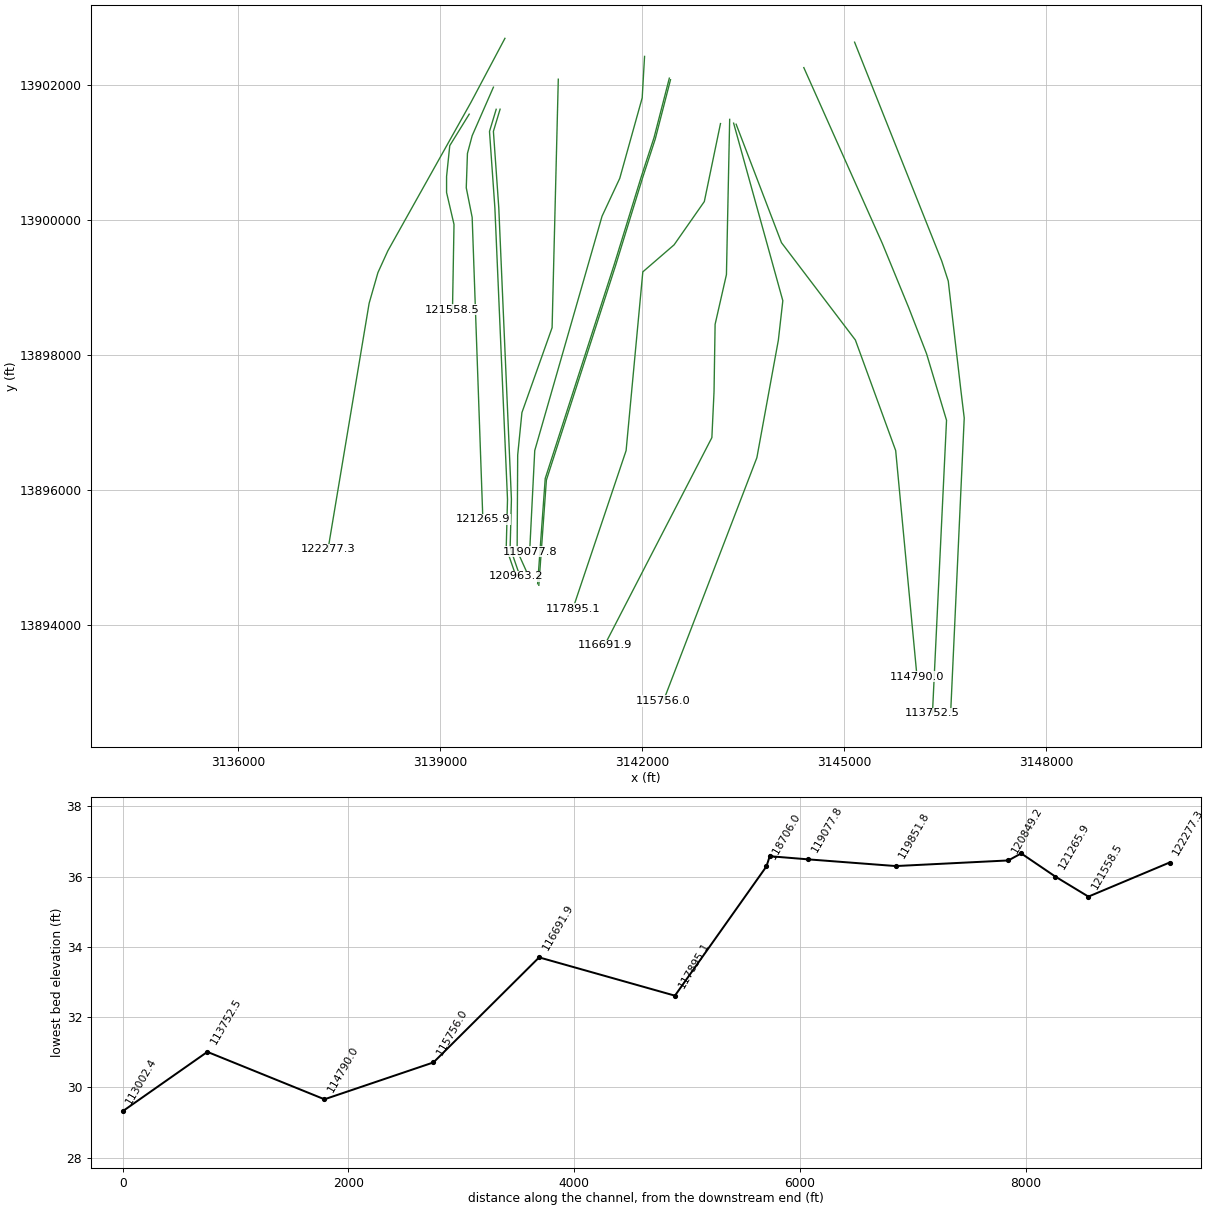
HEC-RAS study P100-00-00.prj: P100-00-00

--- P100-00-00.g01 (geometry) --- (continued)

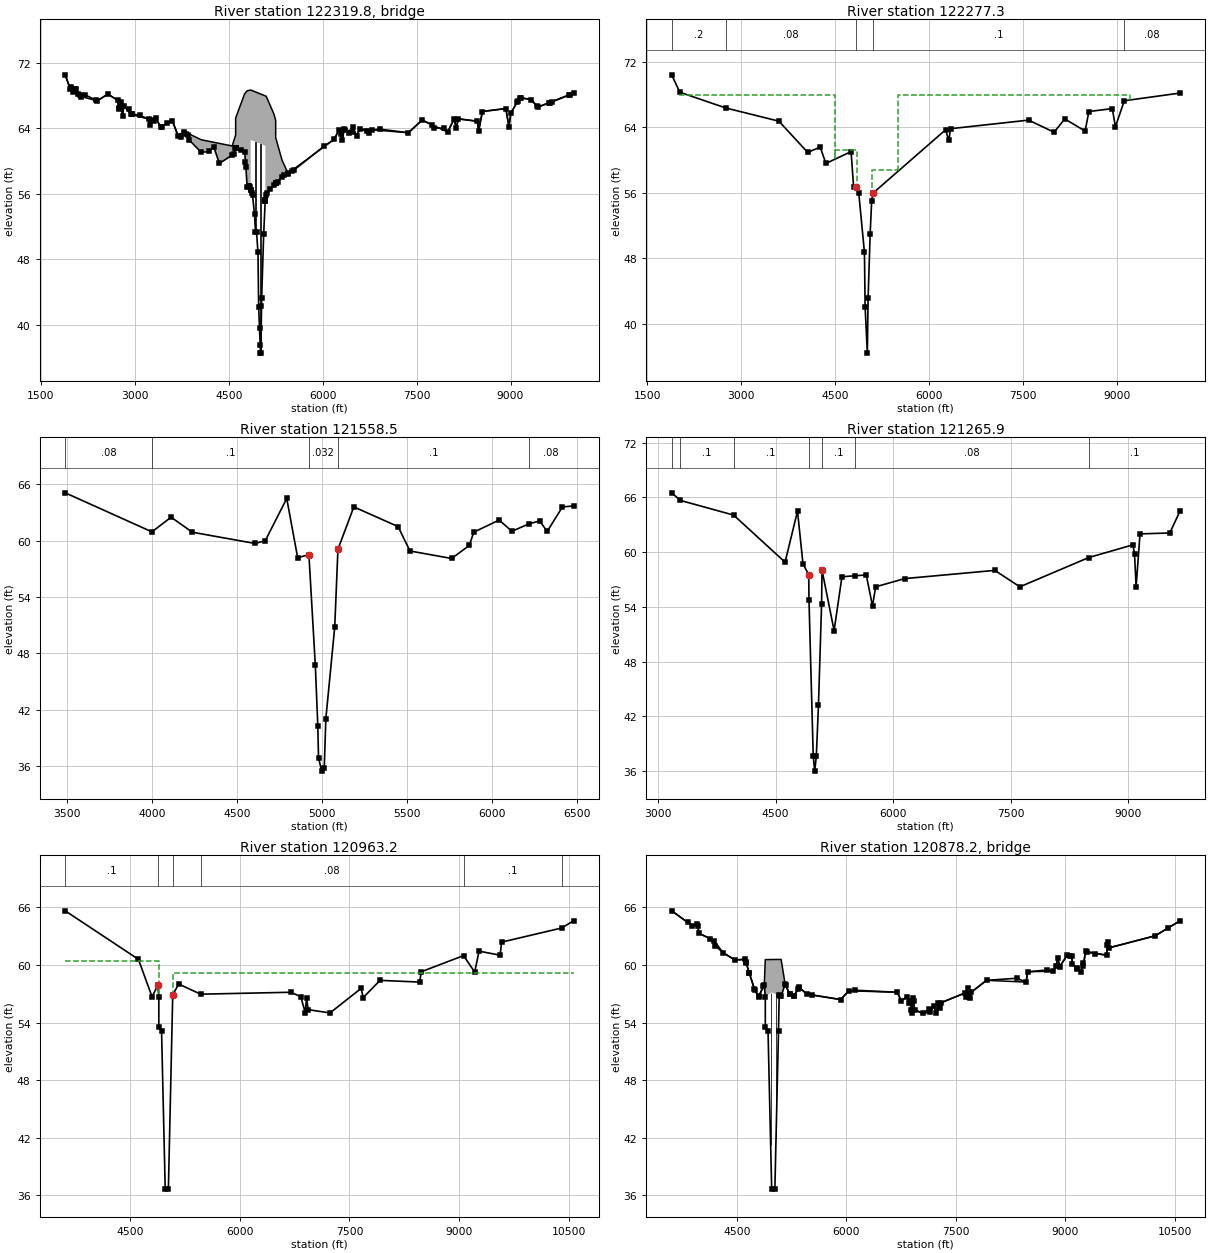
Type RM Length L Ch R = 3 ,122319.8,,,
BEGIN DESCRIPTION:
EASTEX FREEWAY (NORTHBOUND)    Skew Factor 30 Degrees
Structure ID: P00-31
END DESCRIPTION:
Bridge Culvert--1,0,-1,-1, 0
Deck Dist Width WeirC Skew NumUp NumDn MinLoCord MaxHiCord MaxSubmerge Is_Ogee
10,65,2.6,0, 60, 60, , , 0.95, 0, 1,1,,
  1888.4  1968.4  2148.4  2398.4  2568.4  2724.5  2744.5  2774.5  2804.5  2824.5
  2934.5  3220.7  3240.7  3330.7  3410.7  3600.7  3690.7  3790.7  4060.7  4260.7
  4350.7  4554.5 4610.09  4610.2  4753.4  4793.4 4850.61  4850.7 5084.67 5084.78
  5097.9  5223.1  5249.4 5249.51  5351.1 5447.12  6183.1  6262.9  6312.9  6342.9
  6462.9  6482.9  6542.9  6592.9  7367.8  7587.8  7995.3  8095.3  8135.3  8165.3
  8470.3  8490.3  8550.3  8924.4  8974.4  9004.4  9144.4  9325.6  9435.6 10005.6
   70.55   68.83   67.88   67.37   68.19   67.46   66.33   67.25   65.47   66.79
   65.73   65.13    64.4   65.34   64.19   64.89   63.18    63.6   62.61    62.3
   62.16   61.85   63.18   65.28   68.22    68.6   68.69   68.69   67.97   67.97
   67.93   65.72   64.97   62.87   60.11   58.51   62.66   63.84   62.53   63.97
   63.52   64.14   63.06   63.94   63.47   65.02   63.54   65.12    64.1   65.17
   64.88   63.68   66.07   66.43   64.22   65.85   67.75   67.54   66.61   68.32
   70.55   68.83   67.88   67.36   68.18   67.45   66.32   67.24   65.46   66.78
   65.72   65.12   64.39   65.33   64.18   64.88   63.04   63.59   61.06   61.71
   59.71   60.73   61.61   61.61   61.16   56.83   56.49   62.59   61.87   55.26
   55.84   57.04   57.26   57.26   58.08   58.51   62.65   63.83   62.52   63.96
   63.51   64.13   63.05   63.93   63.46   65.01   63.53   65.11   64.09   65.16
   64.87   63.67   66.06   66.42   64.21   65.84   67.74   67.53    66.6   68.32
  1888.4  1968.4  2148.4  2398.4  2568.4  2724.5  2744.5  2774.5  2804.5  2824.5
  2934.5  3220.7  3240.7  3330.7  3410.7  3600.7  3690.7  3790.7  4060.7  4260.7
  4350.7  4554.5 4610.09  4610.2  4753.4  4793.4 4850.61  4850.7 5084.67 5084.78
  5097.9  5223.1  5249.4 5249.51  5351.1 5447.12  6183.1  6262.9  6312.9  6342.9
  6462.9  6482.9  6542.9  6592.9  7367.8  7587.8  7995.3  8095.3  8135.3  8165.3
  8470.3  8490.3  8550.3  8924.4  8974.4  9004.4  9144.4  9325.6  9435.6 10005.6
   70.55   68.83   67.88   67.37   68.19   67.46   66.33   67.25   65.47   66.79
   65.73   65.13    64.4   65.34   64.19   64.89   63.18    63.6   62.61    62.3
   62.16   61.85   63.18   65.28   68.22    68.6   68.69   68.69   67.97   67.97
   67.93   65.72   64.97   62.87   60.11   58.51   62.66   63.84   62.53   63.97
   63.52   64.14   63.06   63.94   63.47   65.02   63.54   65.12    64.1   65.17
   64.88   63.68   66.07   66.43   64.22   65.85   67.75   67.54   66.61   68.32
   70.45   68.73   67.78   67.26   68.08   67.35   66.22   67.14   65.36   66.68
   65.62   65.02   64.29   65.23   64.08   64.78   62.94   63.49   60.96   61.61
   59.61   60.63   61.51   61.51   61.06   56.73   56.39   62.49   61.77   55.16
   55.74   56.94   57.16   57.16   57.98   58.41   62.55   63.73   62.42   63.86
   63.41   64.03   62.95   63.83   63.36   64.91   63.43   65.01   63.99   65.06
   64.77   63.57   65.96   66.32   64.11   65.74   67.64   67.43    66.5   68.22
Pier Skew, UpSta & Num, DnSta & Num=  ,4926.9, 2 ,4926.9, 2 , 0 , 0 , 0 ,,
       2       2
   50.29   63.35
       2       2
   50.19   63.25
Pier Skew, UpSta & Num, DnSta & Num=  ,5006.4, 2 ,5006.4, 2 , 0 , 0 , 0 ,,
       2       2
   35.57   63.11
       2       2
   35.47   63.01
Abutment Skew #Up #Dn= , 2 , 2
  4850.5 4879.89
   62.59    55.8
  4850.5 4879.89
   62.49    55.7
Abutment Skew #Up #Dn= , 2 , 2
 5082.18 5084.87
   55.15   61.87
 5082.18 5084.87
   55.05   61.77
BR Coef= 1 , 1 , 0 ,1.25, 0 ,,,0.8,0,2,0,
WSPro=,,,, 1 ,,,, 0 ,,,, 0 ,,,,-1 ,-1 ,-1 , 0 , 0 , 0 , 0 , 0
BR U #Sta/Elev= 136
  1888.4   70.55  1968.4   68.83  1978.4   69.05  2018.4   68.42  2038.4   68.76
  2058.4   68.79  2098.4   68.16  2128.4   68.05  2148.4   67.88  2208.4    68.1
  2375.2   67.45  2398.4   67.36  2568.4   68.18  2724.5   67.45  2744.5   66.32
  2750.4    66.5  2774.5   67.24  2804.5   65.46  2824.5   66.78  2904.5   66.34
  2934.5   65.72  2954.5   65.77  2960.3   65.76  3084.5   65.59  3220.7   65.12
  3240.7   64.39  3270.7   64.98  3300.7   64.85  3330.7   65.33  3410.7   64.18
  3440.7   64.18  3510.7   64.71  3600.7   64.88  3690.7   63.04  3740.7   62.95
  3790.7   63.59  3820.7   63.34  3850.7   63.14  3870.7   62.57  4060.7   61.06
  4180.7   61.18  4260.7   61.71  4350.7   59.71  4554.5   60.73  4583.4   60.88
  4603.4   61.63 4610.09   61.61  4610.2   61.61 4610.31   61.61  4614.4    61.6
  4695.3   61.34  4753.4   61.16  4766.3   59.94  4773.4   59.27  4793.4   56.83
  4823.4   56.95  4823.6   56.95 4833.12   56.79 4850.61   56.49  4850.7   56.49
 4876.42   56.05 4879.89    55.8 4911.41    53.5 4926.91   51.29 4943.36   51.32
 4966.75   48.83 4977.31   42.19 4991.51   39.59 5002.34   37.51 5006.41   36.58
 5012.73   36.51 5022.69   42.27 5025.37   43.29 5057.59   51.05 5082.08   55.13
 5082.18   55.15 5084.67   55.26 5084.78   55.26  5097.9   55.84 5103.31   56.08
  5160.3   56.54  5223.1   57.04 5249.29   57.26  5249.4   57.26 5249.51   57.26
  5279.8    57.5  5351.1   58.08 5377.75   58.29  5438.1   58.48 5447.12   58.51
  5512.5   58.79  5544.5   58.92  6023.1   61.83  6183.1   62.65  6262.9   63.83
  6292.9   63.34  6312.9   62.52  6342.9   63.96  6362.9    63.8  6412.9   63.45
  6462.9   63.51  6482.9   64.13  6542.9   63.05  6592.9   63.93  6712.9   63.63
  6742.9   63.44  6792.9   63.84  6922.9    63.9  7367.8   63.46  7587.8   65.01
  7747.8   64.42  7785.3   64.02  7935.3   64.04  7995.3   63.53  8095.3   65.11
  8135.3   64.09  8165.3   65.16  8470.3   64.87  8490.3   63.67  8550.3   66.06
  8924.4   66.42  8974.4   64.21  9004.4   65.84  9104.4   67.22  9116.5   67.38
  9144.4   67.74  9174.4   67.73  9325.6   67.53  9426.3   66.68  9435.6    66.6
  9616.3   67.11  9626.3   67.14  9665.6   67.25  9936.3   68.08  9955.6   68.14
 10005.6   68.32
BR U #Mann= 5
  1888.4      .2  2750.4     .08 4833.12    .032 5103.31      .1  9116.5     .08
BR U Banks=4833.12,5103.31
BR D #Sta/Elev= 136
  1888.4   70.45  1968.4   68.73  1978.4   68.95  2018.4   68.32  2038.4   68.66
  2058.4   68.69  2098.4   68.06  2128.4   67.95  2148.4   67.78  2208.4      68
  2375.2   67.35  2398.4   67.26  2568.4   68.08  2724.5   67.35  2744.5   66.22
  2750.4    66.4  2774.5   67.14  2804.5   65.36  2824.5   66.68  2904.5   66.24
  2934.5   65.62  2954.5   65.67  2960.3   65.66  3084.5   65.49  3220.7   65.02
  3240.7   64.29  3270.7   64.88  3300.7   64.75  3330.7   65.23  3410.7   64.08
  3440.7   64.08  3510.7   64.61  3600.7   64.78  3690.7   62.94  3740.7   62.85
  3790.7   63.49  3820.7   63.24  3850.7   63.04  3870.7   62.47  4060.7   60.96
  4180.7   61.08  4260.7   61.61  4350.7   59.61  4554.5   60.63  4583.4   60.78
  4603.4   61.53 4610.09   61.51  4610.2   61.51 4610.31   61.51  4614.4    61.5
  4695.3   61.24  4753.4   61.06  4766.3   59.84  4773.4   59.17  4793.4   56.73
  4823.4   56.85  4823.6   56.85 4833.12   56.69 4850.61   56.39  4850.7   56.39
 4876.42   55.95 4879.89    55.7 4911.41    53.4 4926.91   51.19 4943.36   51.22
 4966.75   48.73 4977.31   42.09 4991.51   39.49 5002.34   37.41 5006.41   36.48
 5012.73   36.41 5022.69   42.17 5025.37   43.19 5057.59   50.95 5082.08   55.03
 5082.18   55.05 5084.67   55.16 5084.78   55.16  5097.9   55.74 5103.31   55.98
  5160.3   56.44  5223.1   56.94 5249.29   57.16  5249.4   57.16 5249.51   57.16
  5279.8    57.4  5351.1   57.98 5377.75   58.19  5438.1   58.38 5447.12   58.41
  5512.5   58.69  5544.5   58.82  6023.1   61.73  6183.1   62.55  6262.9   63.73
  6292.9   63.24  6312.9   62.42  6342.9   63.86  6362.9    63.7  6412.9   63.35
  6462.9   63.41  6482.9   64.03  6542.9   62.95  6592.9   63.83  6712.9   63.53
  6742.9   63.34  6792.9   63.74  6922.9    63.8  7367.8   63.36  7587.8   64.91
  7747.8   64.32  7785.3   63.92  7935.3   63.94  7995.3   63.43  8095.3   65.01
  8135.3   63.99  8165.3   65.06  8470.3   64.77  8490.3   63.57  8550.3   65.96
  8924.4   66.32  8974.4   64.11  9004.4   65.74  9104.4   67.12  9116.5   67.28
  9144.4   67.64  9174.4   67.63  9325.6   67.43  9426.3   66.58  9435.6    66.5
  9616.3   67.01  9626.3   67.04  9665.6   67.15  9936.3   67.98  9955.6   68.04
 10005.6   68.22
BR D #Mann= 5
  1888.4      .2  2750.4     .08 4833.12    .032 5103.31      .1  9116.5     .08
BR D Banks=4833.12,5103.31
BC Design=,, 0 ,, 0 ,,,,,,
BC HTab HWMax=70.7
BC Use User HTab Curves=0
BC User HTab FreeFlow(D)= 0

Type RM Length L Ch R = 1 ,122277.3,718.8,718.8,718.8
BEGIN DESCRIPTION:
Downstream Section of Bridge/Culvert/Weir
END DESCRIPTION:
XS GIS Cut Line= 6
       3139964.2     13902690.75      3139460.69     13901744.45
      3138226.25     13899544.55      3138079.02     13899221.77
      3137948.77     13898768.74      3137338.28     13895123.12
#Sta/Elev= 30
  1888.4   70.44  2018.4   68.31  2750.4   66.39  3600.7   64.77  4060.7   60.95
  4260.7    61.6  4350.7    59.6  4753.4   61.05  4793.4   56.72 4833.12   56.68
 4876.42   55.94 4966.75   48.72 4977.31   42.08 5012.73    36.4 5025.37   43.18
 5057.59   50.94 5082.18   55.04 5103.31   55.97  6262.9   63.72  6312.9   62.41
  6342.9   63.85  7587.8    64.9  7995.3   63.42  8165.3   65.05  8490.3   63.56
  8550.3   65.95  8924.4   66.31  8974.4    64.1  9116.5   67.27 10005.6   68.21
#Mann= 5 , 1 , 0
  1888.4      .2       0  2750.4     .08       0 4833.12    .032       0
 5103.31      .1       0  9116.5     .08       0
#XS Ineff= 4 ,-1
    2000    4500      68  4500.1    4840    61.2    5095    5500    58.8
  5500.1    9200      68
Permanent Ineff=
       F       F       F       F
Bank Sta=4833.12,5103.31
XS Rating Curve= 0 ,0
Exp/Cntr=0.5,0.3

Type RM Length L Ch R = 1 ,121558.5,290.3,292.6,446.8
BEGIN DESCRIPTION:
Cross Section 121558.5
END DESCRIPTION:
XS GIS Cut Line= 6
      3139433.95     13901568.14      3139145.26     13901101.81
      3139097.99      13900644.8      3139097.99     13900408.42
       3139208.3     13899935.66      3139185.79     13898673.01
#Sta/Elev= 30
  3489.9    65.1  4000.4   60.94  4113.3    62.5  4238.3    60.9  4607.8    59.7
  4667.8      60  4794.1    64.5  4858.3   58.19  4924.6    58.5  4962.4   46.71
    4977   40.27  4981.2   36.83  5000.2   35.43    5015   35.79  5024.3   41.02
  5076.6   50.79  5095.5   59.08  5189.1    63.6  5449.6    61.5  5519.6    58.9
  5764.6    58.1  5869.6    59.5  5894.6    60.9  6044.6    62.2  6119.6      61
  6219.5   61.79  6282.5    62.1  6327.5      61  6417.5    63.6  6482.5    63.7
#Mann= 5 , 1 , 0
  3489.9     .08       0  4000.4      .1       0  4924.6    .032       0
  5095.5      .1       0  6219.5     .08       0
Bank Sta=4924.6,5095.5
XS Rating Curve= 0 ,0
Exp/Cntr=0.3,0.1

Type RM Length L Ch R = 1 ,121265.9,304.8,302.7,301.3
BEGIN DESCRIPTION:
Cross Section 121265.9-Interpolated
END DESCRIPTION:
XS GIS Cut Line= 6
      3139793.29     13901967.53      3139477.85     13901249.04
      3139407.75     13900986.17      3139390.23     13900477.97
      3139477.85     13900039.86       3139636.5     13895571.02
#Sta/Elev= 30
  3174.6    66.5  3285.3   65.67  3964.6   64.06  4621.3    58.9  4779.8    64.5
  4849.8    58.7  4922.8   57.54  4926.2   54.75  4980.3   37.68    4999      36
  5019.7   37.62    5047   43.21  5087.2   54.36  5092.5   58.02  5246.6    51.4
  5346.6    57.3  5510.7   57.41  5656.6    57.5  5736.6    54.1  5776.6    56.2
  6146.6    57.1  7296.6      58  7616.6    56.2  8495.9   59.41    9059    60.8
    9079    59.8    9099    56.2    9149      62    9529    62.1    9659    64.5
#Mann= 7 , 1 , 0
  3174.6      .2       0  3285.3      .1       0  3964.6      .1       0
  4922.8    .032       0  5092.5      .1       0  5510.7     .08       0
  8495.9      .1       0
Bank Sta=4922.8,5092.5
XS Rating Curve= 0 ,0
Exp/Cntr=0.5,0.3

Type RM Length L Ch R = 1 ,120963.2,114,114,114
BEGIN DESCRIPTION:
Upstream Section of Bridge/Culvert/Weir
END DESCRIPTION:
XS GIS Cut Line= 6
      3139834.43     13901640.09      3139735.06     13901312.16
      3139814.88     13900180.44      3140002.39     13895865.02
      3139983.36     13895146.81      3140128.15     13894728.71
#Sta/Elev= 30
  3608.1   65.64  4610.4   60.59  4797.6   56.68  4875.7   57.89    4890   56.71
    4890   53.59  4927.5    53.1  4977.4   36.66  5020.9   36.66  5080.3   56.88
  5161.5   58.02  5462.4   56.96  6693.7   57.16  6833.7   56.71  6893.7   55.05
  6913.7   56.57  6933.7   55.35  7233.7   55.01  7659.1   57.56  7689.1   56.61
  7919.1    58.4  8462.1   58.22  8482.1   59.29  9062.7   60.98  9214.8   59.26
  9274.8   61.44  9563.3   61.02  9583.3   62.38 10404.7   63.85 10568.3    64.6
#Mann= 6 ,-1 , 0
  3608.1      .1       0  4875.7     .03       0  5080.3      .1       0
  5462.4     .08       0  9062.7      .1       0 10404.7      .1       0
#XS Ineff= 2 , 0
       0    4890    60.4    5080       0    59.2
Permanent Ineff=
       F       F
Bank Sta=4875.7,5080.3
XS Rating Curve= 0 ,0
Exp/Cntr=0.5,0.3

Type RM Length L Ch R = 3 ,120878.2,,,
BEGIN DESCRIPTION:
HOMESTEAD ROAD
Structure ID: P00-30
END DESCRIPTION:
Bridge Culvert--1,0,-1,-1, 0
Deck Dist Width WeirC Skew NumUp NumDn MinLoCord MaxHiCord MaxSubmerge Is_Ogee
10,94,2.6,0, 60, 60, , , 0.95, 0, 1,1,,
  3608.1  3888.1  3958.1  3985.1  4185.1  4314.9  4474.9  4610.4  4743.5  4797.6
  4875.7    4890  4977.4  5106.6  5161.5  5224.7  5281.9  5352.5  5462.4  5922.4
  6032.4  6693.7  6753.7  6833.7  6853.7  6873.7  6893.7  6913.7  6933.7  7043.7
  7143.7  7193.7  7233.7  7253.7  7279.1  7299.1  7629.1  7639.1  7659.1  7689.1
  7709.1  7919.1  8462.1  8482.1  8832.1  8872.1  8892.1  8922.1  9024.8  9084.8
  9094.8  9214.8  9234.8  9244.8  9274.8  9563.3  9583.3  9598.3 10228.3 10568.3
   65.64   64.09   64.23   63.29   62.55   61.27   60.52   60.59   57.44   56.68
   57.89   60.56   60.57   60.58   58.02   56.96    56.8   57.66   56.96    56.4
   57.31   57.16   56.29   56.71      56   56.22   55.05   56.57   55.35   54.96
   55.06   55.73   55.01   56.02   55.49   56.08    57.1   56.66   57.56   56.61
   57.16    58.4   58.22   59.29   59.36   59.85   60.75   59.84   61.03   60.95
   60.13   59.26   60.19   59.89   61.44   61.02   62.38   61.79   63.04    64.6
   65.64   64.09   64.23   63.29   62.55   61.27   60.52   60.59   57.44   56.68
   57.89   56.71   57.14   56.73   58.02   56.96    56.8   57.66   56.96    56.4
   57.31   57.16   56.29   56.71      56   56.22   55.05   56.57   55.35   54.96
   55.06   55.73   55.01   56.02   55.49   56.08    57.1   56.66   57.56   56.61
   57.16    58.4   58.22   59.29   59.36   59.85   60.75   59.84   61.03   60.95
   60.13   59.26   60.19   59.89   61.44   61.02   62.38   61.79   63.04    64.6
  3608.1  3888.1  3958.1  3985.1  4185.1  4314.9  4474.9  4610.4  4743.5  4797.6
  4875.7    4890  4977.4  5106.6  5161.5  5224.7  5281.9  5352.5  5462.4  5922.4
  6032.4  6693.7  6753.7  6833.7  6853.7  6873.7  6893.7  6913.7  6933.7  7043.7
  7143.7  7193.7  7233.7  7253.7  7279.1  7299.1  7629.1  7639.1  7659.1  7689.1
  7709.1  7919.1  8462.1  8482.1  8832.1  8872.1  8892.1  8922.1  9024.8  9084.8
  9094.8  9214.8  9234.8  9244.8  9274.8  9563.3  9583.3  9598.3 10228.3 10568.3
   65.46   63.91   64.05   63.11   62.37   61.09   60.34   60.41   57.26    56.5
   57.71   60.36   60.37   60.38   57.84   56.78   56.62   57.48   56.78   56.22
   57.13   56.98   56.11   56.53   55.82   56.04   54.87   56.39   55.17   54.78
   54.88   55.55   54.83   55.84   55.31    55.9   56.92   56.48   57.38   56.43
   56.98   58.22   58.04   59.11   59.18   59.67   60.57   59.66   60.85   60.77
   59.95   59.08   60.01   59.71   61.26   60.84    62.2   61.61   62.86   64.42
   65.46   63.91   64.05   63.11   62.37   61.09   60.34   60.41   57.26    56.5
   57.71   56.51   56.94   56.53   57.84   56.78   56.62   57.48   56.78   56.22
   57.13   56.98   56.11   56.53   55.82   56.04   54.87   56.39   55.17   54.78
   54.88   55.55   54.83   55.84   55.31    55.9   56.92   56.48   57.38   56.43
   56.98   58.22   58.04   59.11   59.18   59.67   60.57   59.66   60.85   60.77
   59.95   59.08   60.01   59.71   61.26   60.84    62.2   61.61   62.86   64.42
Pier Skew, UpSta & Num, DnSta & Num=  ,4963.42, 2 ,4963.42, 2 , 0 , 0 , 0 ,,
     1.5     1.5
   17.14   57.14
     1.5     1.5
   16.94   56.94
Pier Skew, UpSta & Num, DnSta & Num=  ,5036.75, 2 ,5036.75, 2 , 0 , 0 , 0 ,,
     1.5     1.5
   17.14   57.14
     1.5     1.5
   16.94   56.94
BR Coef= 1 , 1 , 0 ,1.25, 0 ,,,0.8,0,2,0,
WSPro=,,,, 1 ,,,, 0 ,,,, 0 ,,,,-1 ,-1 ,-1 , 0 , 0 , 0 , 0 , 0
BR U #Sta/Elev= 98
  3608.1   65.64  3828.1   64.44  3888.1   64.09  3958.1   64.23  3965.1   64.03
  3985.1   63.29  4134.3   62.74  4185.1   62.55  4205.1      62  4314.9   61.27
  4474.9   60.52  4610.4   60.59  4627.7   60.26  4629.4   60.23  4669.6    59.2
  4671.5   59.15  4739.5   57.54  4743.5   57.44  4797.6   56.68  4805.1   56.81
    4863    57.8  4875.7   57.89    4890   56.71    4890   53.59  4927.5    53.1
  4977.4   36.66  5020.9   36.66  5070.8   53.13  5080.3   56.88  5092.5   56.81
  5106.6   56.73  5161.5   58.02  5167.4   57.92  5224.7   56.96    5226   56.96
  5281.9    56.8  5282.5   56.81    5343    57.5  5348.3   57.56  5352.5   57.66
  5462.4   56.96  5530.2   56.88  5922.4    56.4  6032.4   57.31  6122.4   57.37
  6693.7   57.16  6753.7   56.29  6833.7   56.71  6853.7      56  6873.7   56.22
  6883.7   55.36  6893.7   55.05  6903.7    56.1  6913.7   56.57  6923.7   56.24
  6933.7   55.35  7043.7   54.96  7133.7   55.38  7143.7   55.06  7193.7   55.73
  7233.7   55.01  7253.7   56.02  7279.1   55.49  7299.1   56.08  7629.1    57.1
  7639.1   56.66  7659.1   57.56  7679.1   56.67  7689.1   56.61  7709.1   57.16
  7919.1    58.4  8332.1   58.62  8462.1   58.22  8482.1   59.29  8752.1   59.48
  8832.1   59.36  8872.1   59.85  8892.1   60.75  8922.1   59.84  9024.8   61.03
  9062.7   60.98  9084.8   60.95  9094.8   60.13  9154.8   59.64  9164.8   59.55
  9214.8   59.26  9234.8   60.19  9244.8   59.89  9274.8   61.44  9294.8   61.31
  9405.3   61.19  9563.3   61.02  9573.3   62.05  9583.3   62.38  9598.3   61.79
 10228.3   63.04 10404.7   63.85 10568.3    64.6
BR U #Mann= 6
  3608.1      .1  4875.7     .03  5080.3      .1  5462.4     .08  9062.7      .1
 10404.7      .1
BR U Banks=4875.7,5080.3
BR D #Sta/Elev= 98
  3608.1   65.46  3828.1   64.26  3888.1   63.91  3958.1   64.05  3965.1   63.85
  3985.1   63.11  4134.3   62.56  4185.1   62.37  4205.1   61.82  4314.9   61.09
  4474.9   60.34  4610.4   60.41  4627.7   60.08  4629.4   60.05  4669.6   59.02
  4671.5   58.97  4739.5   57.36  4743.5   57.26  4797.6    56.5  4805.1   56.63
    4863   57.62  4875.7   57.71    4890   56.51    4890   53.39  4927.5    52.9
  4977.4   36.46  5020.9   36.46  5070.8   52.93  5080.3   56.68  5092.5   56.61
  5106.6   56.53  5161.5   57.84  5167.4   57.74  5224.7   56.78    5226   56.78
  5281.9   56.62  5282.5   56.63    5343   57.32  5348.3   57.38  5352.5   57.48
  5462.4   56.78  5530.2    56.7  5922.4   56.22  6032.4   57.13  6122.4   57.19
  6693.7   56.98  6753.7   56.11  6833.7   56.53  6853.7   55.82  6873.7   56.04
  6883.7   55.18  6893.7   54.87  6903.7   55.92  6913.7   56.39  6923.7   56.06
  6933.7   55.17  7043.7   54.78  7133.7    55.2  7143.7   54.88  7193.7   55.55
  7233.7   54.83  7253.7   55.84  7279.1   55.31  7299.1    55.9  7629.1   56.92
  7639.1   56.48  7659.1   57.38  7679.1   56.49  7689.1   56.43  7709.1   56.98
  7919.1   58.22  8332.1   58.44  8462.1   58.04  8482.1   59.11  8752.1    59.3
  8832.1   59.18  8872.1   59.67  8892.1   60.57  8922.1   59.66  9024.8   60.85
  9062.7    60.8  9084.8   60.77  9094.8   59.95  9154.8   59.46  9164.8   59.37
  9214.8   59.08  9234.8   60.01  9244.8   59.71  9274.8   61.26  9294.8   61.13
  9405.3   61.01  9563.3   60.84  9573.3   61.87  9583.3    62.2  9598.3   61.61
 10228.3   62.86 10404.7   63.67 10568.3   64.42
BR D #Mann= 6
  3608.1      .1  4875.7     .03  5080.3      .1  5462.4     .08  9062.7      .1
 10404.7      .1
BR D Banks=4875.7,5080.3
BC Design=,, 0 ,, 0 ,,,,,,
BC HTab HWMax=65.64
BC Use User HTab Curves=0
BC User HTab FreeFlow(D)= 0

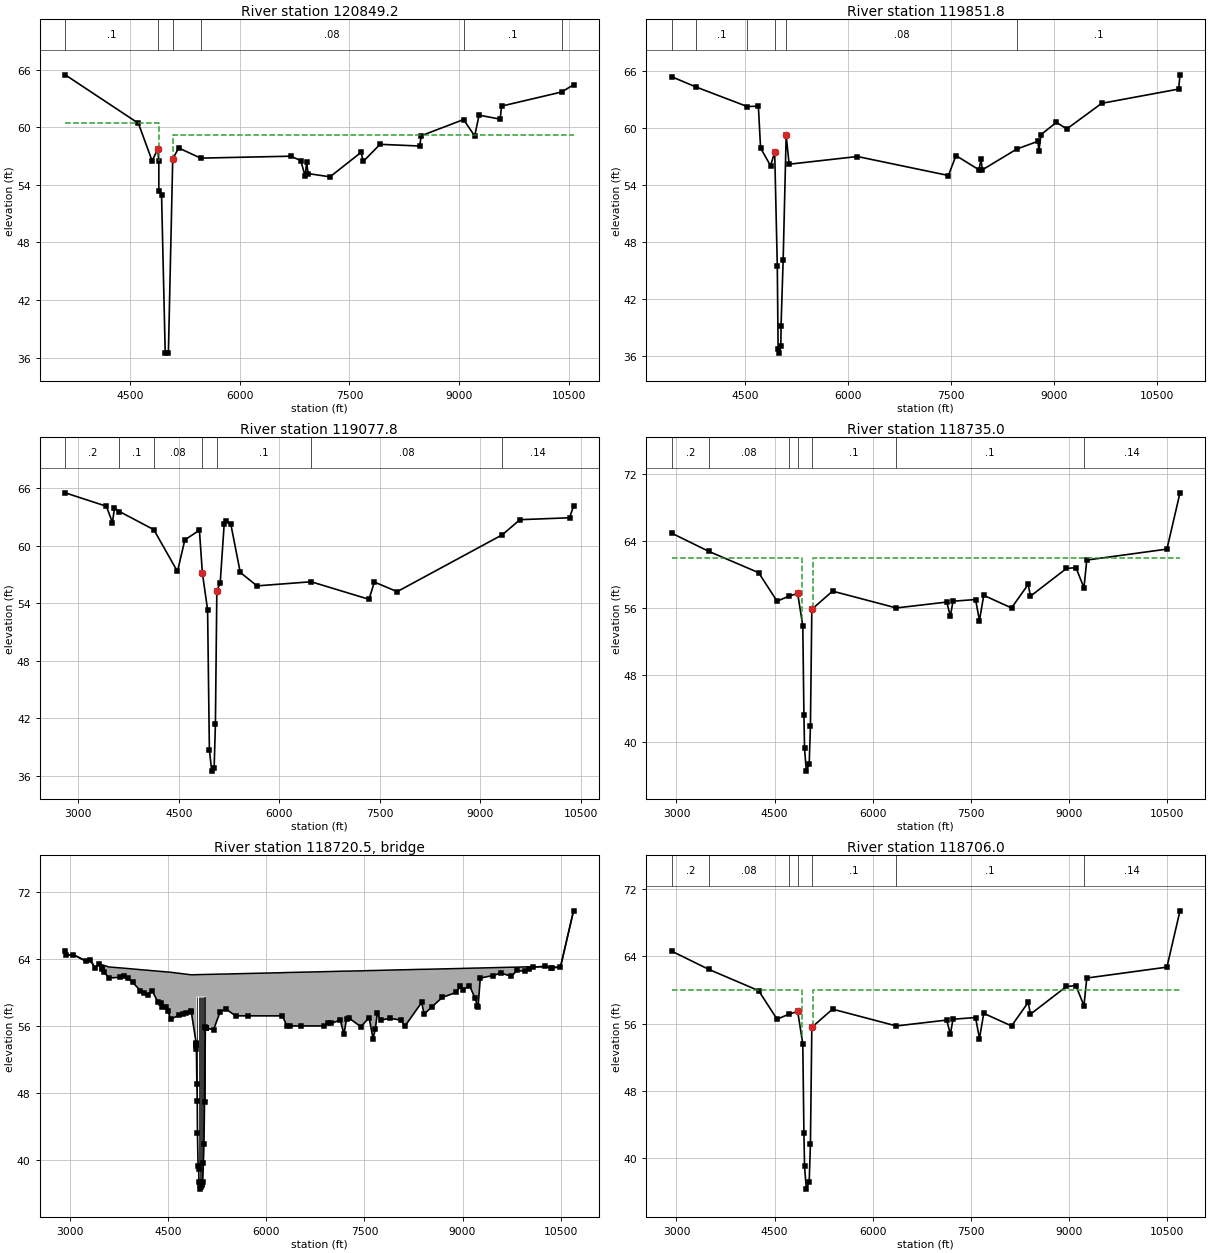
Type RM Length L Ch R = 1 ,120849.2,997.4,997.4,997.4
BEGIN DESCRIPTION:
Downstream Section of Bridge/Culvert/Weir
END DESCRIPTION:
XS GIS Cut Line= 6
       3139892.4     13901641.76      3139793.04     13901313.82
      3139872.86      13900182.1      3140060.37     13895866.68
      3140041.34     13895148.47      3140186.12     13894730.38
#Sta/Elev= 30
  3608.1   65.46  4610.4   60.41  4797.6    56.5  4875.7   57.71    4890   56.51
    4890   53.39  4927.5    52.9  4977.4   36.46  5020.9   36.46  5080.3   56.68
  5161.5   57.84  5462.4   56.78  6693.7   56.98  6833.7   56.53  6893.7   54.87
  6913.7   56.39  6933.7   55.17  7233.7   54.83  7659.1   57.38  7689.1   56.43
  7919.1   58.22  8462.1   58.04  8482.1   59.11  9062.7    60.8  9214.8   59.08
  9274.8   61.26  9563.3   60.84  9583.3    62.2 10404.7   63.67 10568.3   64.42
#Mann= 6 ,-1 , 0
  3608.1      .1       0  4875.7     .03       0  5080.3      .1       0
  5462.4     .08       0  9062.7      .1       0 10404.7      .1       0
#XS Ineff= 2 , 0
       0    4890    60.4    5080       0    59.2
Permanent Ineff=
       F       F
Bank Sta=4875.7,5080.3
XS Rating Curve= 0 ,0
Exp/Cntr=0.5,0.3

Type RM Length L Ch R = 1 ,119851.8,953.3,774,349.5
BEGIN DESCRIPTION:
Cross Section 119851.8
END DESCRIPTION:
XS GIS Cut Line= 6
      3140756.14      13902085.3      3140664.07     13898406.97
      3140216.31     13897149.47      3140153.54     13896521.77
      3140145.17     13895105.25      3140287.05     13894790.78
#Sta/Elev= 30
  3427.6    65.4  3778.8   64.33  4530.5   62.26    4692    62.3    4724    57.9
  4870.3   56.02  4929.9   57.47    4968   45.48    4980   36.71  4998.8    36.3
  5019.8      37  5022.7   39.19  5053.6   46.13  5097.3   59.22  5140.7   56.19
  6136.3      57  7463.9      55  7573.9    57.1  7908.9    55.6  7938.9    56.7
  7958.9    55.6  8462.1   57.79  8768.8    58.6  8783.8    57.6  8813.8    59.3
  9038.8    60.6  9189.6    59.9  9699.6    62.6 10821.1    64.1 10841.1    65.6
#Mann= 6 , 1 , 0
  3427.6      .2       0  3778.8      .1       0  4530.5     .07       0
  4929.9    .032       0  5097.3     .08       0  8462.1      .1       0
Bank Sta=4929.9,5097.3
XS Rating Curve= 0 ,0
Exp/Cntr=0.3,0.1

Type RM Length L Ch R = 1 ,119077.8,342.9,342.8,290.1
BEGIN DESCRIPTION:
Cross Section 119077.8-Interpolated
END DESCRIPTION:
XS GIS Cut Line= 6
      3142036.39     13902423.16      3142001.34     13901809.82
      3141668.38     13900618.16      3141405.52     13900057.39
      3140406.63     13896587.58      3140330.97     13895089.51
#Sta/Elev= 30
    2807    65.5  3421.4    64.1  3511.4    62.4  3541.4    63.9  3616.3   63.55
  4128.5   61.66  4481.4    57.3  4591.4    60.6  4808.6    61.6  4852.6   57.16
  4930.6   53.31  4957.4   38.72  4992.2   36.49  5028.5   36.86  5047.2   41.38
  5068.7   55.28  5118.6    56.1  5178.6    62.3  5208.6    62.6    5278    62.2
    5418    57.2    5668    55.8  6474.4   56.23    7338    54.4    7418    56.2
    7758    55.2  9327.4   61.13  9588.7    62.7 10328.7    62.9 10388.7    64.1
#Mann= 7 , 1 , 0
    2807      .2       0  3616.3      .1       0  4128.5     .08       0
  4852.6    .035       0  5068.7      .1       0  6474.4     .08       0
  9327.4     .14       0
Bank Sta=4852.6,5068.7
XS Rating Curve= 0 ,0
Exp/Cntr=0.5,0.3

Type RM Length L Ch R = 1 ,118735.0,29,29,29
BEGIN DESCRIPTION:
Upstream Section of Bridge/Culvert/Weir
END DESCRIPTION:
XS GIS Cut Line= 6
      3142404.15     13902101.23      3142177.11     13901221.37
      3141991.38     13900654.09      3141586.78     13899343.87
      3140562.14     13896174.19      3140449.51     13894616.03
#Sta/Elev= 30
  2926.3    64.9  3494.4   62.73  4255.1    60.2  4537.7    56.8  4719.3   57.41
  4852.6   57.72  4930.5   53.87  4947.8   43.27  4957.4   39.28  4984.5   36.58
  5028.5   37.42  5047.2   41.94  5068.7   55.84  5385.6      58  6360.2      56
  7131.4    56.7  7186.4      55  7226.4    56.8  7571.4      57  7631.4    54.5
  7696.4    57.5    8121      56    8376    58.8    8411    57.4    8961    60.7
    9106    60.8  9228.6    58.4  9271.6    61.7 10496.6      63 10696.6    69.7
#Mann= 7 , 1 , 0
  2926.3      .2       0  3494.4     .08       0  4719.3      .1       0
  4852.6    .032       0  5068.7      .1       0  6360.2      .1       0
  9228.6     .14       0
#XS Ineff= 2 , 0
       0    4920      62    5083       0      62
Permanent Ineff=
       F       F
Bank Sta=4852.6,5068.7
XS Rating Curve= 0 ,0
Exp/Cntr=0.5,0.3

Type RM Length L Ch R = 3 ,118720.5,,,
BEGIN DESCRIPTION:
SOUTHERN PACIFIC RAILROAD - Skewed 30 Degrees
Structure ID: P00-29
END DESCRIPTION:
Bridge Culvert--1,0,-1,-1, 0
Deck Dist Width WeirC Skew NumUp NumDn MinLoCord MaxHiCord MaxSubmerge Is_Ogee
10,9,2.6,0, 60, 60, , , 0.95, 0, 1,1,,
  2926.3  2936.3  3046.3    3247    3307    3382  3440.7  3595.7  3830.7  4075.7
  4185.1  4255.1  4345.1  4385.1  4410.1  4460.1  4537.7  4849.9 4930.71  4930.8
  4966.1 5072.49  5072.6    5073  5194.4  5295.6  5385.6  5530.6  6244.3  6317.2
  6887.2  7131.4  7186.4  7226.4  7271.4  7446.4  7571.4  7631.4  7666.4  7696.4
  7746.4  8052.9    8121    8376    8411    8691    8906    8961    9006    9106
  9191.6  9236.6  9271.6  9586.6  9746.6  9831.6  9961.6 10081.6 10496.6 10696.6
    64.9    64.4    64.5    63.7    63.9    62.9    63.4   63.02   62.87    62.7
   62.63   62.58   62.52   62.49   62.48   62.44   62.39   62.09    62.1    62.1
   62.11   62.13   62.13   62.13   62.15   62.17   62.18   62.21   62.34   62.36
   62.46   62.51   62.52   62.52   62.53   62.56   62.59    62.6    62.6   62.61
   62.62   62.68   62.69   62.74   62.74   62.79   62.83   62.84   62.85   62.87
   62.89   62.89    62.9   62.96   62.99      63   63.03   63.05      63    69.7
    64.9    64.4    64.5    63.7    63.9    62.9    63.4    61.7      62    60.2
    59.7    60.2    58.8    58.7    58.3    58.3    56.8   57.71   53.76   59.47
   59.48    59.5   55.75   55.74   55.56    57.7      58    57.2    57.2      56
      56    56.7      55    56.8    56.9    55.9      57    54.5    55.6    57.5
    56.7    56.7      56    58.8    57.4    59.4      60    60.7    60.3    60.8
    59.3    58.2    61.7    62.3    61.9    62.6    62.5      63      63    69.7
  2926.3  2936.3  3046.3    3247    3307    3382  3440.7  3595.7  3830.7  4075.7
  4185.1  4255.1  4345.1  4385.1  4410.1  4460.1  4537.7  4849.9 4930.71  4930.8
  4966.1 5072.49  5072.6    5073  5194.4  5295.6  5385.6  5530.6  6244.3  6317.2
  6887.2  7131.4  7186.4  7226.4  7271.4  7446.4  7571.4  7631.4  7666.4  7696.4
  7746.4  8052.9    8121    8376    8411    8691    8906    8961    9006    9106
  9191.6  9236.6  9271.6  9586.6  9746.6  9831.6  9961.6 10081.6 10496.6 10696.6
    64.9    64.4    64.5    63.7    63.9    62.9    63.4   63.02   62.87    62.7
   62.63   62.58   62.52   62.49   62.48   62.44   62.39   62.09    62.1    62.1
   62.11   62.13   62.13   62.13   62.15   62.17   62.18   62.21   62.34   62.36
   62.46   62.51   62.52   62.52   62.53   62.56   62.59    62.6    62.6   62.61
   62.62   62.68   62.69   62.74   62.74   62.79   62.83   62.84   62.85   62.87
   62.89   62.89    62.9   62.96   62.99      63   63.03   63.05      63    69.7
   64.66   64.16   64.26   63.46   63.66   62.66   63.16   61.46   61.76   59.96
   59.46   59.96   58.56   58.46   58.06   58.06   56.56   57.47   53.52   59.23
   59.24   59.26   55.51    55.5   55.32   57.46   57.76   56.96   56.96   55.76
   55.76   56.46   54.76   56.56   56.66   55.66   56.76   54.26   55.36   57.26
   56.46   56.46   55.76   58.56   57.16   59.16   59.76   60.46   60.06   60.56
   59.06   57.96   61.46   62.06   61.66   62.36   62.26   62.76   62.76   69.46
Pier Skew, UpSta & Num, DnSta & Num=  ,4947.8, 2 ,4947.8, 2 , 0 , 0 , 0 ,,
     1.3     1.3
      42   60.47
     1.3     1.3
   41.76   60.23
Pier Skew, UpSta & Num, DnSta & Num=  ,4966.1, 2 ,4966.1, 2 , 0 , 0 , 0 ,,
     1.3     1.3
   37.79   60.48
     1.3     1.3
   37.55   60.24
Pier Skew, UpSta & Num, DnSta & Num=  ,4984.5, 2 ,4984.5, 2 , 0 , 0 , 0 ,,
     1.3     1.3
   35.62   60.48
     1.3     1.3
   35.38   60.24
Pier Skew, UpSta & Num, DnSta & Num=  ,5002.3, 2 ,5002.3, 2 , 0 , 0 , 0 ,,
     1.3     1.3
    35.8   60.48
     1.3     1.3
   35.56   60.24
Pier Skew, UpSta & Num, DnSta & Num=  ,5019.8, 2 ,5019.8, 2 , 0 , 0 , 0 ,,
     1.3     1.3
   36.15   60.49
     1.3     1.3
   35.91   60.25
Pier Skew, UpSta & Num, DnSta & Num=  ,5038.2, 2 ,5038.2, 2 , 0 , 0 , 0 ,,
     1.3     1.3
   38.58   60.49
     1.3     1.3
   38.34   60.25
Pier Skew, UpSta & Num, DnSta & Num=  ,5055.7, 2 ,5055.7, 2 , 0 , 0 , 0 ,,
     1.3     1.3
   45.51   60.49
     1.3     1.3
   45.27   60.25
Abutment Skew #Up #Dn= , 2 , 2
  4930.6  4931.6
   59.47   53.27
  4930.6  4931.6
   59.23   53.03
BR Coef= 1 , 1 , 0 ,1.25, 0 ,,,0.8,0,2,0,
WSPro=,,,, 1 ,,,, 0 ,,,, 0 ,,,,-1 ,-1 ,-1 , 0 , 0 , 0 , 0 , 0
BR U #Sta/Elev= 105
  2926.3    64.9  2936.3    64.4  3046.3    64.5    3247    63.7    3307    63.9
    3382    62.9  3440.7    63.4  3483.7   62.86  3494.4   62.73  3520.7    62.4
  3595.7    61.7  3770.7    61.8  3830.7      62  3880.7    61.7  3955.7    61.2
  4075.7    60.2  4125.1    59.9  4185.1    59.7  4255.1    60.2  4345.1    58.8
  4385.1    58.7  4410.1    58.3  4460.1    58.3  4495.1    57.8  4537.7    56.8
  4672.7    57.3  4719.3   57.41  4775.6   57.54  4849.9   57.71  4852.6   57.72
    4928   53.99  4930.5   53.87  4930.6   53.82 4930.71   53.76  4930.8   53.71
  4931.6   53.27  4939.3   49.06  4944.8   47.02  4947.8   43.27  4957.4   39.28
  4966.1   38.98  4971.5   37.38  4984.5   36.58  4992.2   37.05  5002.3   36.78
  5011.1   37.08  5019.8   37.16  5028.5   37.42  5038.2   39.73  5047.2   41.94
  5055.7   46.89  5068.7   55.84    5072   55.76 5072.49   55.75  5072.6   55.75
    5073   55.74  5194.4   55.56  5295.6    57.7  5385.6      58  5530.6    57.2
  5719.3    57.2  6244.3    57.2  6317.2      56  6360.2      56  6537.2      56
  6887.2      56  6941.4    56.3  6991.4    56.3  7131.4    56.7  7186.4      55
  7226.4    56.8  7271.4    56.9  7446.4    55.9  7571.4      57  7631.4    54.5
  7666.4    55.6  7696.4    57.5  7746.4    56.7  7897.9    56.9  8052.9    56.7
    8121      56    8376    58.8    8411    57.4    8536    58.3    8691    59.4
    8906      60    8961    60.7    9006    60.3    9106    60.8  9191.6    59.3
  9228.6    58.4  9236.6    58.2  9271.6    61.7  9466.6      62  9586.6    62.3
  9746.6    61.9  9831.6    62.6  9961.6    62.5 10021.6    62.8 10081.6      63
 10261.6    63.1 10354.4   62.92 10366.6    62.9 10496.6      63 10696.6    69.7
BR U #Mann= 7
  2926.3      .2  3494.4     .08  4719.3      .1  4852.6    .032  5068.7      .1
  6360.2      .1  9228.6     .14
BR U Banks=4852.6,5068.7
BR D #Sta/Elev= 105
  2926.3   64.66  2936.3   64.16  3046.3   64.26    3247   63.46    3307   63.66
    3382   62.66  3440.7   63.16  3483.7   62.62  3494.4   62.49  3520.7   62.16
  3595.7   61.46  3770.7   61.56  3830.7   61.76  3880.7   61.46  3955.7   60.96
  4075.7   59.96  4125.1   59.66  4185.1   59.46  4255.1   59.96  4345.1   58.56
  4385.1   58.46  4410.1   58.06  4460.1   58.06  4495.1   57.56  4537.7   56.56
  4672.7   57.06  4719.3   57.17  4775.6    57.3  4849.9   57.47  4852.6   57.48
    4928   53.75  4930.5   53.63  4930.6   53.58 4930.71   53.52  4930.8   53.47
  4931.6   53.03  4939.3   48.82  4944.8   46.78  4947.8   43.03  4957.4   39.04
  4966.1   38.74  4971.5   37.14  4984.5   36.34  4992.2   36.81  5002.3   36.54
  5011.1   36.84  5019.8   36.92  5028.5   37.18  5038.2   39.49  5047.2    41.7
  5055.7   46.65  5068.7    55.6    5072   55.52 5072.49   55.51  5072.6   55.51
    5073    55.5  5194.4   55.32  5295.6   57.46  5385.6   57.76  5530.6   56.96
  5719.3   56.96  6244.3   56.96  6317.2   55.76  6360.2   55.76  6537.2   55.76
  6887.2   55.76  6941.4   56.06  6991.4   56.06  7131.4   56.46  7186.4   54.76
  7226.4   56.56  7271.4   56.66  7446.4   55.66  7571.4   56.76  7631.4   54.26
  7666.4   55.36  7696.4   57.26  7746.4   56.46  7897.9   56.66  8052.9   56.46
    8121   55.76    8376   58.56    8411   57.16    8536   58.06    8691   59.16
    8906   59.76    8961   60.46    9006   60.06    9106   60.56  9191.6   59.06
  9228.6   58.16  9236.6   57.96  9271.6   61.46  9466.6   61.76  9586.6   62.06
  9746.6   61.66  9831.6   62.36  9961.6   62.26 10021.6   62.56 10081.6   62.76
 10261.6   62.86 10354.4   62.68 10366.6   62.66 10496.6   62.76 10696.6   69.46
BR D #Mann= 7
  2926.3      .2  3494.4     .08  4719.3      .1  4852.6    .032  5068.7      .1
  6360.2      .1  9228.6     .14
BR D Banks=4852.6,5068.7
BC Design=,, 0 ,, 0 ,,,,,,
BC HTab HWMax=69.7
BC Use User HTab Curves=0
BC User HTab FreeFlow(D)= 0

Type RM Length L Ch R = 1 ,118706.0,810.9,810.9,810.9
BEGIN DESCRIPTION:
Downstream Section of Bridge/Culvert/Weir
END DESCRIPTION:
XS GIS Cut Line= 6
      3142421.66     13902078.12      3142194.61     13901198.25
      3142008.88     13900630.97      3141604.28     13899320.75
      3140579.64     13896151.07      3140467.02     13894592.91
#Sta/Elev= 30
  2926.3   64.61  3494.4   62.44  4255.1   59.91  4537.7   56.51  4719.3   57.12
  4852.6   57.43  4930.5   53.58  4947.8   42.98  4957.4   38.99  4984.5   36.29
  5028.5   37.13  5047.2   41.65  5068.7   55.55  5385.6   57.71  6360.2   55.71
  7131.4   56.41  7186.4   54.71  7226.4   56.51  7571.4   56.71  7631.4   54.21
  7696.4   57.21    8121   55.71    8376   58.51    8411   57.11    8961   60.41
    9106   60.51  9228.6   58.11  9271.6   61.41 10496.6   62.71 10696.6   69.41
#Mann= 7 , 1 , 0
  2926.3      .2       0  3494.4     .08       0  4719.3      .1       0
  4852.6    .032       0  5068.7      .1       0  6360.2      .1       0
  9228.6     .14       0
#XS Ineff= 2 , 0
       0    4920      60    5083       0      60
Permanent Ineff=
       F       F
Bank Sta=4852.6,5068.7
XS Rating Curve= 0 ,0
Exp/Cntr=0.5,0.3

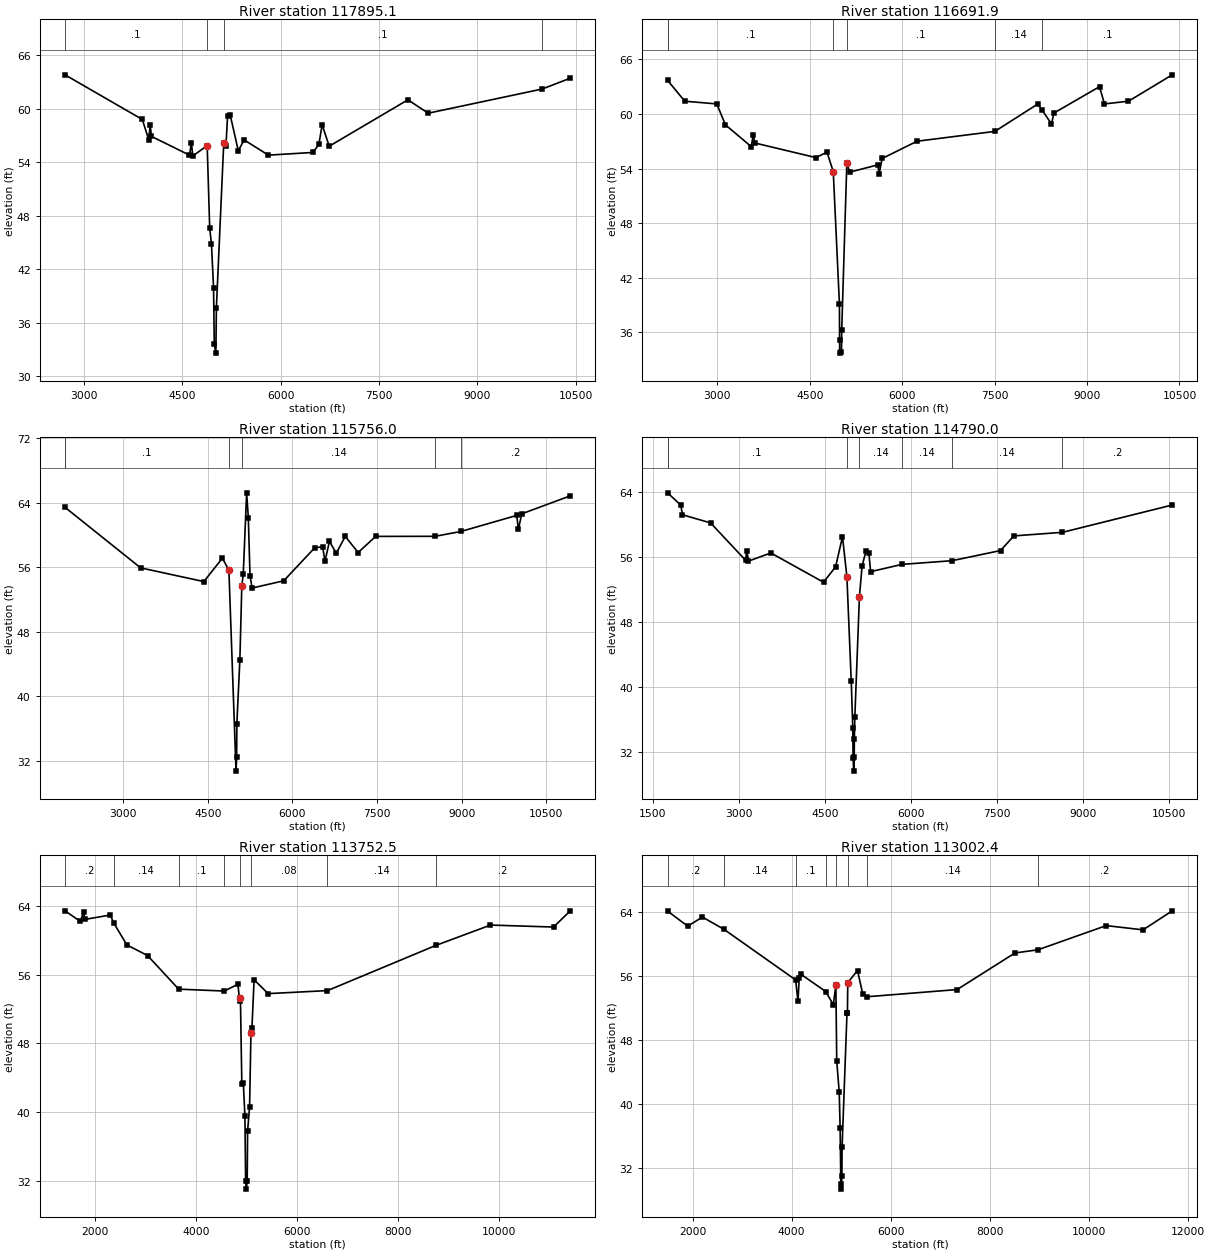
Type RM Length L Ch R = 1 ,117895.1,744.5,1203.2,1424.2
BEGIN DESCRIPTION:
Cross Section 117895.1
END DESCRIPTION:
XS GIS Cut Line= 6
      3143163.26     13901428.75      3142923.34     13900274.16
        3142475.     13899633.68      3142010.65     13899233.37
      3141762.46     13896587.35      3140972.87     13894246.95
#Sta/Elev= 30
  2708.7    63.8    3888    58.8    3988    56.5    4008    58.2    4028    56.9
    4608    54.8    4638    56.2    4658    54.7  4878.4   55.87  4916.9   46.61
  4943.4   44.86  4975.6   39.94  4986.6   33.62    5011   32.61  5018.7   37.67
    5131   56.13  5164.7   55.83  5189.8    59.2  5229.8    59.3  5352.9    55.3
  5442.9    56.5  5812.9    54.8  6492.9    55.1  6582.9      56  6632.9    58.2
    6741    55.8    7942      61    8252    59.5  9991.9   62.21   10412    63.4
#Mann= 4 , 1 , 0
  2708.7      .1       0  4878.4    .032       0    5131      .1       0
  9991.9      .1       0
Bank Sta=4878.4,5131
XS Rating Curve= 0 ,0
Exp/Cntr=0.3,0.1

Type RM Length L Ch R = 1 ,116691.9,821.6,935.9,941.9
BEGIN DESCRIPTION:
Cross Section 116691.9
END DESCRIPTION:
XS GIS Cut Line= 6
      3143299.63     13901491.09      3143251.59     13899193.34
      3143083.47     13898456.78      3143067.45     13897460.02
      3143035.43      13896779.5      3141443.65     13893707.41
#Sta/Elev= 30
  2190.7    63.7  2470.7    61.4  2990.7    61.1  3130.7    58.8  3550.7    56.4
  3580.7    57.7  3610.7    56.8    4599    55.2    4779    55.8  4880.8   53.66
    4981   39.08  4983.2   35.19  4985.4    33.7  5013.5   33.77  5018.2   36.29
  5101.3   54.63  5147.1    53.6  5604.5    54.4  5624.5    53.4  5674.5    55.1
  6241.4      57  7503.8   58.08  8202.6    61.1    8275   60.38  8422.6    58.9
  8462.6    60.1  9202.6      63  9282.6    61.1  9672.6    61.4 10382.6    64.3
#Mann= 6 , 1 , 0
  2190.7      .2       0  2190.7      .1       0  4880.8    .032       0
  5101.3      .1       0  7503.8     .14       0    8275      .1       0
Bank Sta=4880.8,5101.3
XS Rating Curve= 0 ,0
Exp/Cntr=0.3,0.1

Type RM Length L Ch R = 1 ,115756.0,411.8,966,1521.3
BEGIN DESCRIPTION:
Cross Section 115756.0
Located At: 4TH XS DS HOMESTEAD ROAD
END DESCRIPTION:
XS GIS Cut Line= 5
      3143358.17     13901435.25      3144088.44     13898806.27
      3144022.05     13898222.05      3143703.39     13896482.68
      3142315.92      13892880.7
#Sta/Elev= 30
  1971.4    63.4  3311.4    55.9  4431.4    54.2  4759.9    57.1  4875.6   55.61
    5002   30.71  5012.9   32.43  5016.5   36.58  5070.3   44.53  5104.4   53.67
  5129.9    55.1  5189.9    65.2  5219.9    62.1  5249.9    54.9  5287.9    53.4
  5847.9    54.3  6397.9    58.4  6537.9    58.5  6577.9    56.7  6657.9    59.2
  6777.9    57.7  6937.9    59.8  7166.2    57.8  7476.2    59.8    8529   59.81
  8987.3   60.41  9976.2    62.4 10006.2    60.7 10066.2    62.6 10916.2    64.8
#Mann= 6 , 1 , 0
  1971.4      .2       0  1971.4      .1       0  4875.6    .035       0
  5104.4     .14       0    8529      .1       0  8987.3      .2       0
Bank Sta=4875.6,5104.4
XS Rating Curve= 0 ,0
Exp/Cntr=0.3,0.1

Type RM Length L Ch R = 1 ,114790.0,1279.9,1037.5,914.9
BEGIN DESCRIPTION:
Cross Section 114790.0
END DESCRIPTION:
XS GIS Cut Line= 5
       3143395.7     13901419.04      3144068.22      13899665.7
      3145165.06      13898224.6      3145763.42     13896587.43
      3146079.62     13893242.36
#Sta/Elev= 30
  1758.8    63.9  1988.8    62.4  2018.8    61.2  2508.8    60.2  3118.8    55.6
  3138.8    56.8  3168.8    55.5  3558.8    56.5  4476.7    52.9  4686.7    54.8
  4806.7    58.5  4883.5   53.58  4959.2   40.74  4985.5   34.99  4991.2   31.28
  5002.3   29.66  5010.5   31.35  5013.4   33.62  5021.6   36.29    5102   51.14
  5147.6   54.85  5216.7    56.8  5266.7    56.5  5296.7    54.2  5845.4    55.1
  6716.1   55.55  7560.8    56.8  7790.8    58.6  8638.5   59.04 10550.8    62.4
#Mann= 7 , 1 , 0
  1758.8      .2       0  1758.8      .1       0  4883.5    .035       0
    5102     .14       0  5845.4     .14       0  6716.1     .14       0
  8638.5      .2       0
Bank Sta=4883.5,5102
XS Rating Curve= 0 ,0
Exp/Cntr=0.3,0.1

Type RM Length L Ch R = 1 ,113752.5,910.5,750.1,409
BEGIN DESCRIPTION:
Cross Section 113752.5
END DESCRIPTION:
XS GIS Cut Line= 6
      3144400.02     13902257.08      3145565.36     13899653.69
      3145957.66     13898700.96      3146221.86     13898020.44
      3146518.09     13897035.69      3146309.16     13892696.69
#Sta/Elev= 30
  1412.5   63.45  1716.5   62.21  1780.5   63.35  1804.5   62.45  2308.5   62.96
  2372.7   62.07  2636.5   59.47  3044.5   58.24    3661   54.32  4562.7    54.1
  4832.8   54.89  4866.2   52.99  4882.3   53.28  4910.3    43.3  4939.7   43.39
  4971.4   39.55  4985.5   31.95  5000.3   31.01  5016.4   31.96  5024.5   37.78
  5063.8   40.63  5090.8    49.2  5110.8   49.85  5152.8   55.41  5431.1    53.8
  6604.6   54.15  8744.9   59.41  9829.5   61.79 11077.5   61.56 11397.5   63.39
#Mann= 8 , 1 , 0
  1412.5      .2       0  2372.7     .14       0    3661      .1       0
  4562.7     .14       0  4882.3    .035       0  5090.8     .08       0
  6604.6     .14       0  8744.9      .2       0
Bank Sta=4882.3,5090.8
XS Rating Curve= 0 ,0
Exp/Cntr=0.3,0.1

Type RM Length L Ch R = 1 ,113002.4,737.1,722.4,678.3
BEGIN DESCRIPTION:
Cross Section 113002.4
END DESCRIPTION:
XS GIS Cut Line= 6
      3145153.42     13902633.78      3146447.63     13899391.89
      3146543.71     13899097.27      3146729.45     13897492.84
      3146780.69     13897070.12      3146580.59     13892735.04
#Sta/Elev= 30
  1495.6   64.11  1903.6   62.22  2199.6   63.36  2630.6   61.84  4079.4    55.5
  4127.6    52.8  4151.6   55.69  4191.6   56.18  4688.2   54.04  4839.6   52.39
  4891.9   54.83  4908.9   45.35  4959.4   41.43  4977.6   36.94  4991.7      30
  5002.3   29.32  5012.7   30.91  5017.1   34.57  5116.2   51.39  5125.1   51.33
  5131.2   55.15  5328.2   56.67  5432.2   53.78  5520.7   53.39  7337.1   54.29
  8505.1   58.87  8965.9   59.26 10345.1   62.29 11089.1   61.76 11676.8   64.14
#Mann= 8 , 1 , 0
  1495.6      .2       0  2630.6     .14       0  4079.4      .1       0
  4688.2     .14       0  4891.9    .035       0  5131.2     .08       0
  5520.7     .14       0  8965.9      .2       0
Bank Sta=4891.9,5131.2
XS Rating Curve= 0 ,0
Exp/Cntr=0.3,0.1