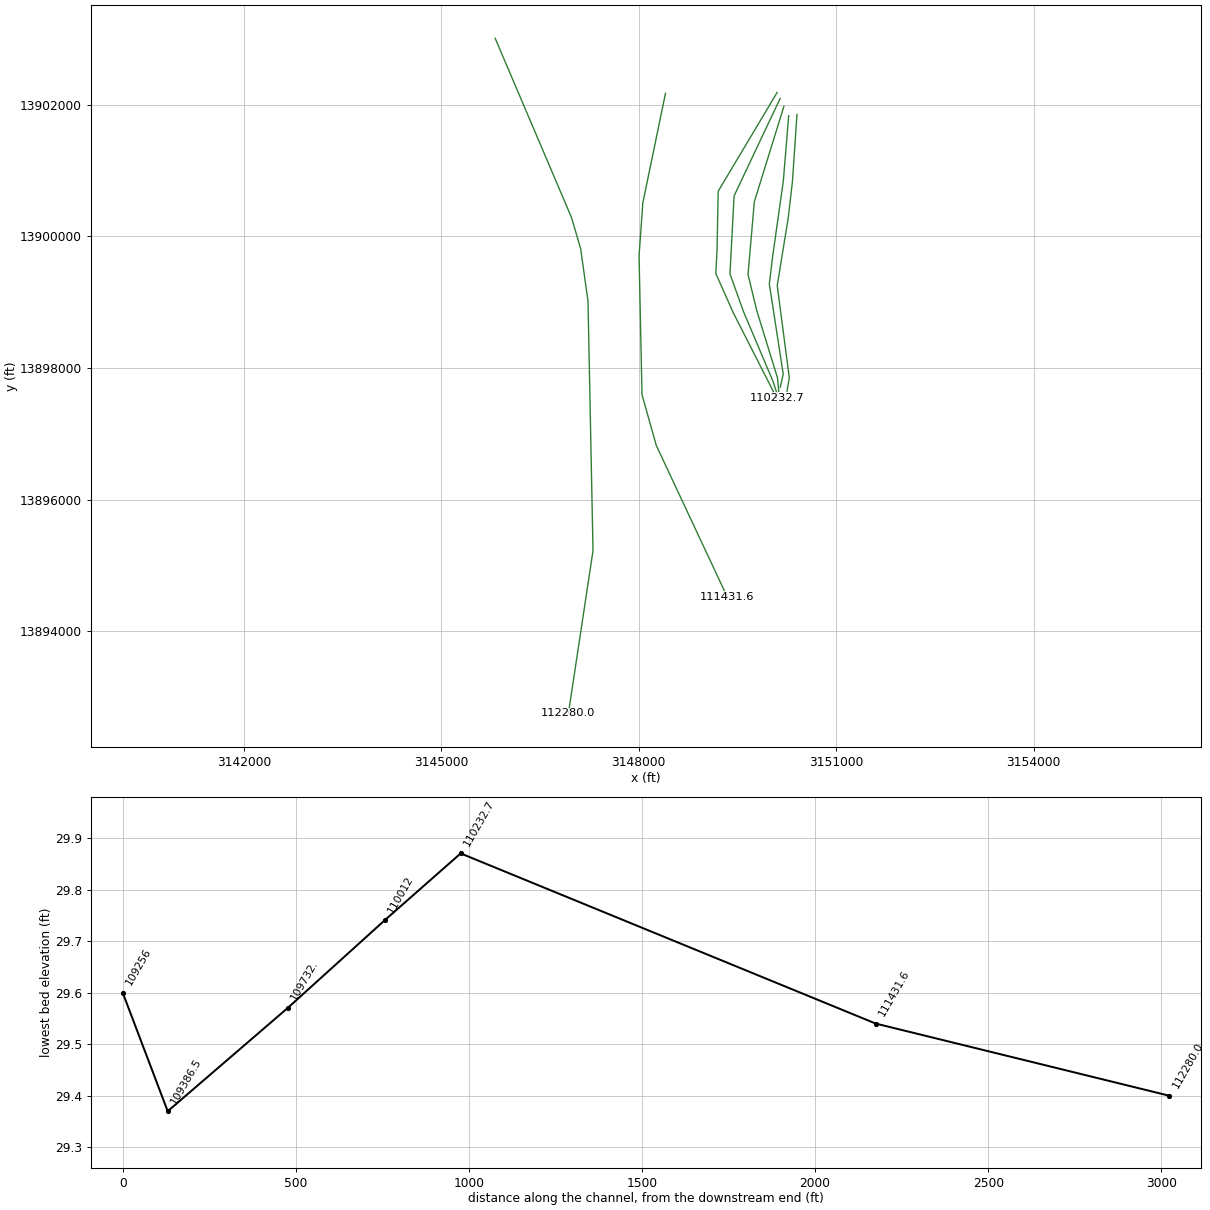
HEC-RAS study P100-00-00.prj: P100-00-00

--- P100-00-00.g01 (geometry) --- (continued)

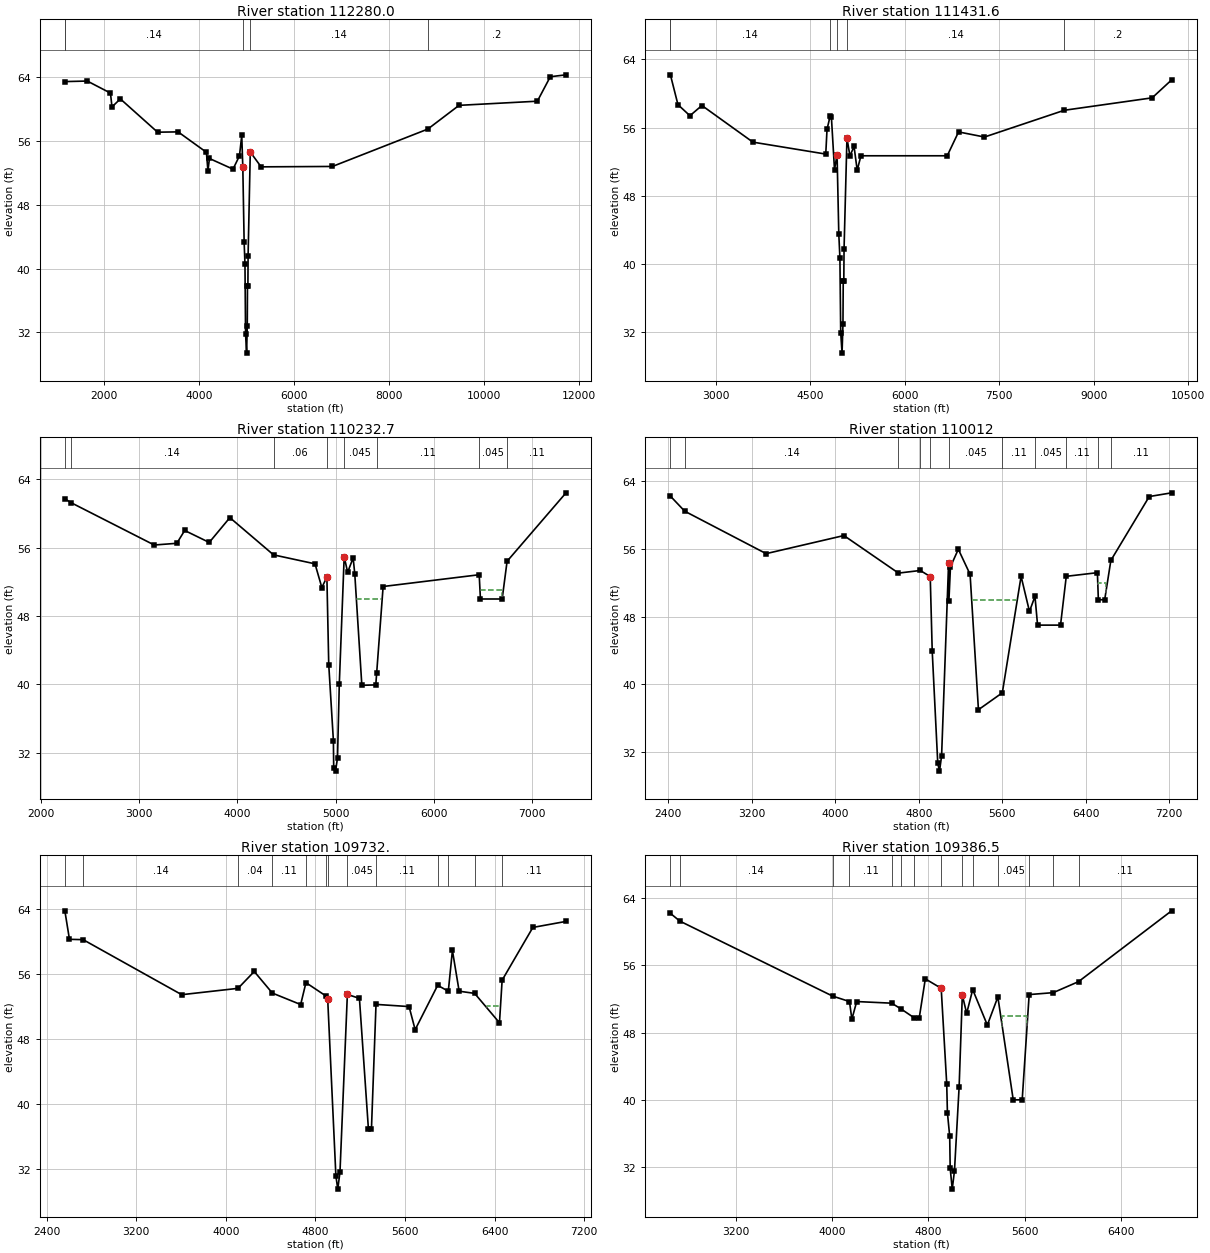
Type RM Length L Ch R = 1 ,112280.0,1042.3,848.4,815
BEGIN DESCRIPTION:
Cross Section 112280.0-Interpolated
END DESCRIPTION:
XS GIS Cut Line= 6
      3145818.19     13903010.48      3146976.58     13900291.26
      3147116.49     13899815.57      3147228.41      13899018.1
       3147304.4     13895225.55      3146930.81      13892754.5
#Sta/Elev= 30
  1178.8   63.48  1650.8   63.55  2138.8   62.04  2170.8    60.3  2346.8   61.31
  3130.8   57.13  3562.8   57.17  4158.5   54.61  4190.5   52.28  4222.5   53.83
  4718.3   52.49  4854.3   54.16  4902.3   56.72    4925    52.7  4952.7   43.34
  4970.2   40.58  4982.8   31.79  5004.3    29.4  5018.5   32.77    5023   37.85
    5032   37.86    5036   41.64    5082   54.64  5310.3   52.78  6811.6   52.83
  8818.8   57.52  9476.9    60.5 11124.9   61.02 11396.9   64.09 11728.1   64.33
#Mann= 5 , 1 , 0
  1178.8      .2       0  1178.8     .14       0    4925    .035       0
    5082     .14       0  8818.8      .2       0
Bank Sta=4925,5082
XS Rating Curve= 0 ,0
Exp/Cntr=0.3,0.1

Type RM Length L Ch R = 1 ,111431.6,1154.5,1198.9,1540.7
BEGIN DESCRIPTION:
Cross Section 111431.6
END DESCRIPTION:
XS GIS Cut Line= 6
      3148405.49     13902174.13      3148061.67     13900512.75
      3148004.02     13899705.73      3148048.86     13897595.32
      3148266.62     13896823.53      3149343.41     13894525.04
#Sta/Elev= 30
  2278.9    62.2  2398.9    58.7  2588.9    57.4  2778.9    58.6  3588.9    54.3
  4745.5    52.9  4765.5    55.8  4816.4   57.39  4834.6    57.3  4884.3   51.06
    4925   52.84  4952.7   43.48  4970.2   40.72  4982.8   31.93  5004.3   29.54
  5018.5   32.91    5023   37.99    5032      38    5036   41.78    5082   54.78
  5129.3   52.68  5194.6    53.8  5244.6      51    5304    52.7    6674    52.7
    6854    55.5  7265.7    54.9  8532.5   58.04  9927.6    59.5 10235.9    61.6
#Mann= 6 , 1 , 0
  2278.9      .2       0  2278.9     .14       0  4816.4     .07       0
    4925    .035       0    5082     .14       0  8532.5      .2       0
Bank Sta=4925,5082
XS Rating Curve= 0 ,0
Exp/Cntr=0.3,0.1

Type RM Length L Ch R = 1 ,110232.7,241.94,220,161.79
BEGIN DESCRIPTION:
Cross Section 110232.7
END DESCRIPTION:
XS GIS Cut Line= 6
      3150100.97     13902187.08      3149206.23     13900686.73
      3149188.93      13899798.6      3149169.71     13899439.93
      3149432.31     13898847.48      3150094.45     13897546.24
#Sta/Elev= 30
  2243.8    61.7    2307  61.249  3153.8    56.3  3383.8    56.5  3463.8      58
  3713.8    56.6  3923.8    59.5  4368.3  55.149  4790.7    54.1  4860.2   51.33
  4911.6   52.55  4930.5   42.32  4977.8   33.45    4981   30.29  4999.3   29.87
  5019.7    31.4  5037.8      40  5087.7   54.94  5122.9   53.11    5179    54.8
 5195.49   52.93  5267.5    39.9 5409.41   39.95  5418.3  41.309 5484.19   51.45
  6462.3  52.826 6474.89   49.99 6696.12   49.99  6746.2    54.4  7346.2    62.4
#Mann= 8 ,-1 , 0
  2243.8    .045       0    2307     .14       0  4368.3     .06       0
  4911.6    .035       0  5087.7    .045       0  5418.3     .11       0
  6462.3    .045       0  6746.2     .11       0
#XS Ineff= 2 ,-1
 5211.87 5476.71      50 6470.43 6699.42      51
Permanent Ineff=
       T       T
Bank Sta=4911.6,5087.7
XS Rating Curve= 0 ,0
Exp/Cntr=0.3,0.1

Type RM Length L Ch R = 1 ,110012  ,307.93,280,205.91
XS GIS Cut Line= 6
 3150146.896494313902095.5025965 3149447.857255613900616.6283199
  3149385.24362213899431.7619517 3149591.330133313898857.3273544
 3150036.738435813897805.1270892 3150108.8038169  13897588.97386
#Sta/Elev= 30
 2420.27   62.25 2557.27   60.47 3337.74   55.45 4083.16   57.59 4606.07   53.15
 4815.07   53.46 4910.51   52.74 4929.64    43.9 4982.74   30.66 4999.27   29.74
 5019.39   31.52 5086.45    54.3 5089.48   49.85 5104.52    53.9  5179.7   55.97
  5292.6      53  5372.6      37 5601.45      39 5781.32   52.77 5861.55   48.62
 5914.45    50.4 5939.27      47 6159.27      47 6214.45   52.77  6512.7    53.2
 6521.95      50  6582.6      50 6641.75   54.65 7009.56    62.2 7223.56   62.64
#Mann= 11 ,-1 , 0
 2420.27    .045       0 2557.27     .14       0 4606.07     .04       0
 4815.07    .045       0 4910.51    .035       0 5086.45    .045       0
 5601.45     .11       0 5914.45    .045       0 6214.45     .11       0
 6521.95    .045       0 6641.75     .11       0
#XS Ineff= 3 ,-1
 5307.06    5744      50 5913.13    6180      49    6517    6592      52
Permanent Ineff=
       T       T       T
Bank Sta=4910.51,5086.45
XS Rating Curve= 0 ,0
Exp/Cntr=0.3,0.1

Type RM Length L Ch R = 1 ,109732. ,380.73,346.2,254.6
XS GIS Cut Line= 6
  3150205.34839613901978.9495374 3149755.382853713900527.4079998
  3149659.55914113899421.3662538 3149793.7193939 13898869.860351
  3150107.28017513897851.6445189  3150127.072311  13897643.36242
#Sta/Elev= 30
 2563.18   63.75  2604.3   60.25 2726.18   60.21 3606.44   53.45 4109.18   54.23
 4253.67    56.3 4415.18   53.65 4667.99   52.24 4715.18   54.93 4897.18   53.26
 4909.12   52.98 4982.45   31.19 4999.24   29.57    5019   31.67 5084.86   53.48
 5192.57      53 5272.57      37    5300      37 5340.59   52.26 5635.81   51.99
 5689.86   49.15 5890.86    54.6 5985.86   53.88 6022.57   58.88 6082.57   53.88
 6220.86   53.61 6442.57      50 6466.31   55.23 6740.59   61.71 7036.57   62.45
#Mann= 13 ,-1 , 0
 2563.18     .04       0 2726.18     .14       0 4109.18     .04       0
 4415.18     .11       0 4715.18     .04       0 4897.18    .045       0
 4909.12    .035       0 5084.86    .045       0 5340.59     .11       0
 5890.86     .04       0 5985.86     .11       0 6220.86    .045       0
 6466.31     .11       0
#XS Ineff= 2 ,-1
 5205.35    5340      49    6330    6460      52
Permanent Ineff=
       T       T
Bank Sta=4909.12,5084.86
XS Rating Curve= 0 ,0
Exp/Cntr=0.3,0.1

Type RM Length L Ch R = 1 ,109386.5,151.11,130,110.79
BEGIN DESCRIPTION:
Cross Section 109386.5
END DESCRIPTION:
XS GIS Cut Line= 6
      3150277.62     13901834.84      3150195.62     13900840.58
      3150034.37     13899702.53      3149983.13     13899279.81
       3150194.5     13897909.16      3150149.66     13897710.61
#Sta/Elev= 30
  2657.9    62.2  2736.2  61.277  4005.2  52.351  4145.5    51.7  4165.5    49.6
  4205.5    51.7  4496.2  51.506  4576.2  50.797  4684.2  49.752  4725.5    49.8
  4775.5    54.4  4907.4   53.28  4953.3   41.92  4959.1   38.48  4978.1   35.65
  4982.1   31.85  4999.2   29.37  5017.8   31.56  5056.4   41.54  5082.9   52.47
  5118.9   50.29  5169.2  53.119  5290.8    48.9  5378.2   52.25 5505.85      40
  5580.3      40  5638.2   52.53  5838.2   52.76  6048.2   54.07  6821.2    62.5
#Mann= 14 ,-1 , 0
  2657.9     .04       0  2736.2     .14       0  4005.2     .04       0
  4145.5     .11       0  4496.2    .045       0  4576.2     .04       0
  4684.2    .045       0  4907.4    .035       0  5082.9    .045       0
  5169.2     .11       0  5378.2    .045       0  5638.2     .11       0
  5838.2     .04       0  6048.2     .11       0
#XS Ineff= 1 ,-1
 5415.55  5620.2      50
Permanent Ineff=
       T
Bank Sta=4907.4,5082.9
XS Rating Curve= 0 ,0
Exp/Cntr=0.3,0.1

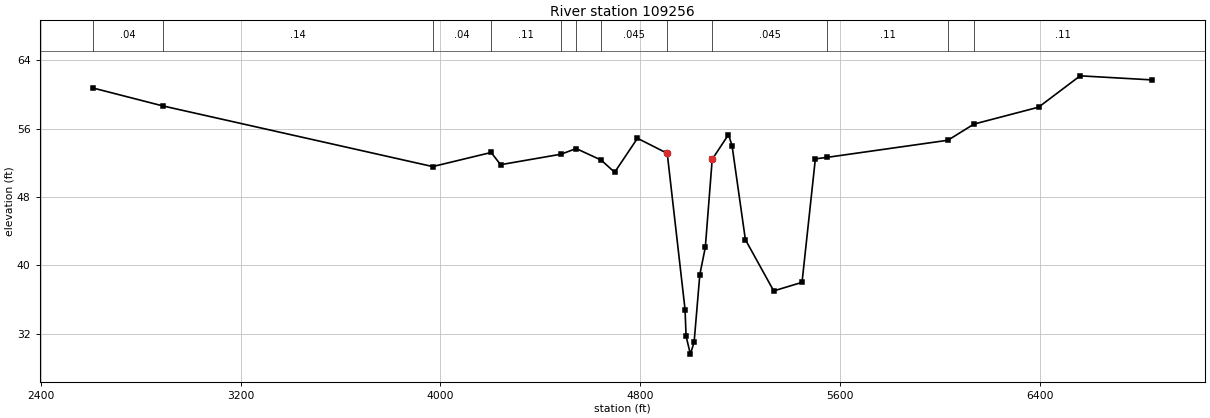
Type RM Length L Ch R = 1 ,109256  ,701.39,603.4,514.21
XS GIS Cut Line= 6
 3150403.325068113901854.4605338  3150334.81922813900839.8439861
 3150271.743529813900291.9384706 3150103.470649513899253.1475578
 3150286.717778813897852.6431626 3150251.5045562  13897649.21008
#Sta/Elev= 30
 2608.88   60.75 2888.88   58.65 3968.88   51.55 4202.88    53.2 4240.59   51.77
 4482.88      53 4542.88   53.66 4642.88   52.31 4696.96   50.88 4788.24   54.86
  4907.3    53.1  4978.7    34.8  4982.7    31.7    5000    29.6  5014.9      31
  5037.7    38.9  5059.7    42.1  5087.3    52.4  5152.4   55.29 5166.67      54
    5220      43 5333.33      37 5446.67      38    5500   52.45  5547.3   52.63
  6030.3   54.63  6134.3   56.52 6393.13    58.5 6559.57   62.17 6848.66   61.69
#Mann= 12 ,-1 , 0
 2608.88     .04       0 2888.88     .14       0 3968.88     .04       0
 4202.88     .11       0 4482.88    .045       0 4542.88     .04       0
 4642.88    .045       0  4907.3    .035       0  5087.3    .045       0
  5547.3     .11       0  6030.3     .04       0  6134.3     .11       0
#XS Ineff= 1 ,-1
    5180    5495      51
Permanent Ineff=
       T
Bank Sta=4907.3,5087.3
XS Rating Curve= 0 ,0
Exp/Cntr=0.3,0.1