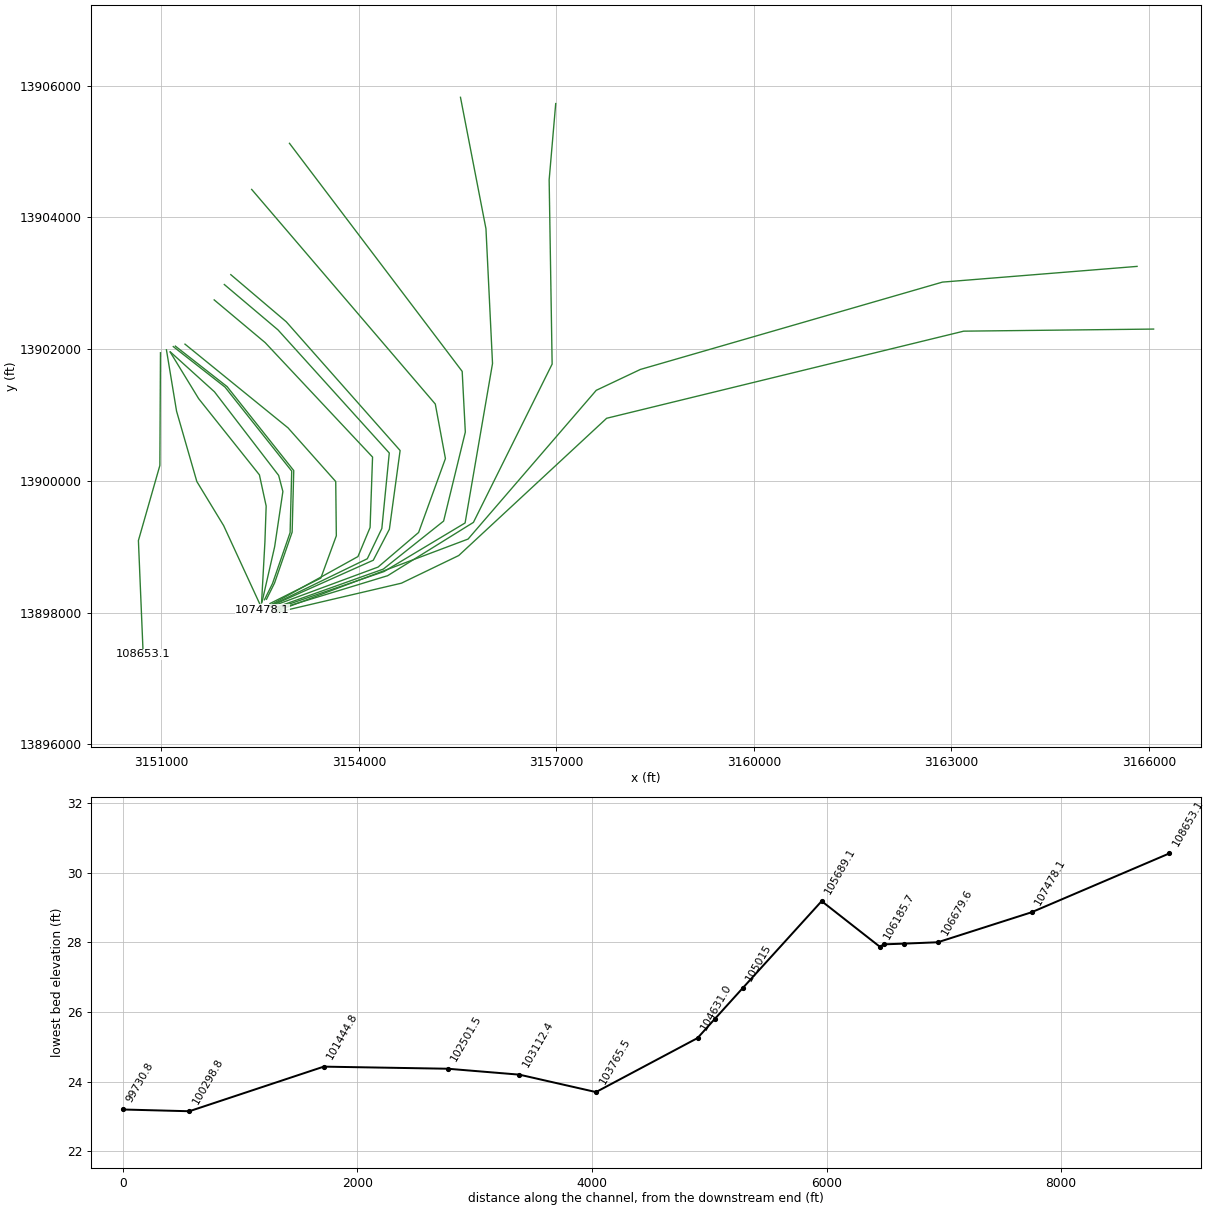
HEC-RAS study P100-00-00.prj: P100-00-00

--- P100-00-00.g01 (geometry) --- (continued)

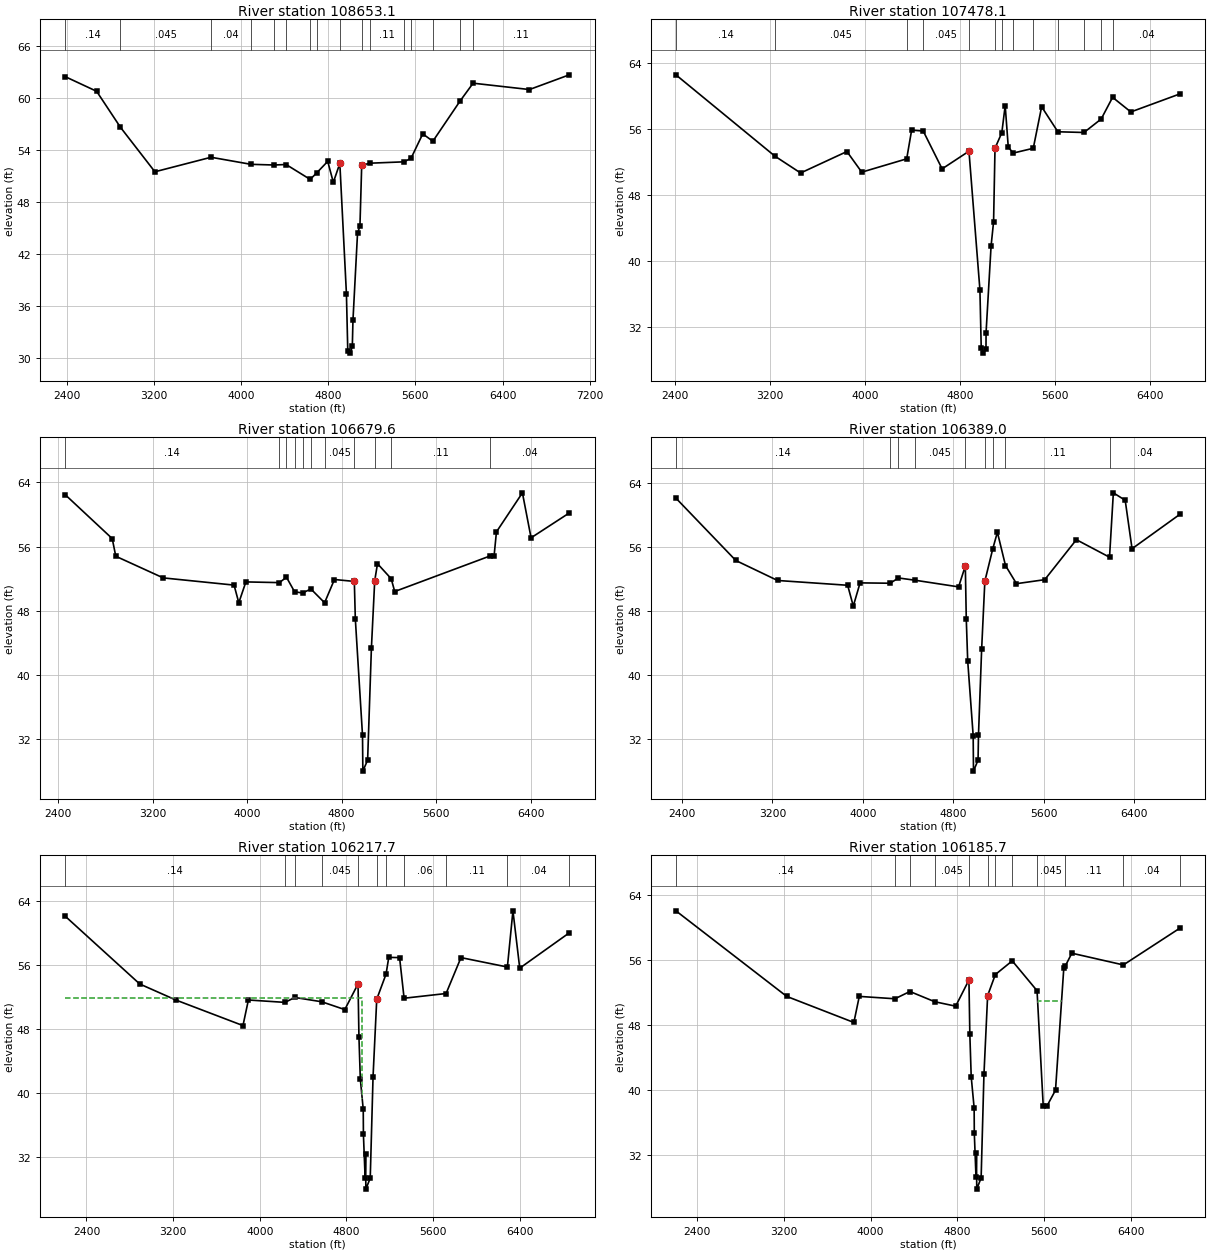
Type RM Length L Ch R = 1 ,108653.1,535.3,1175,1385.5
BEGIN DESCRIPTION:
Cross Section 108653.1
END DESCRIPTION:
XS GIS Cut Line= 4
      3150986.79     13901945.53      3150977.73     13900234.33
      3150651.79     13899093.53      3150724.22     13897364.22
#Sta/Elev= 30
  2384.5    62.5  2674.5    60.8  2893.8  56.631  3209.5    51.5  3724.8  53.177
  4090.8  52.362  4301.8  52.282  4413.8  52.339  4634.8  50.618  4693.8  51.364
  4795.7    52.7  4847.1   50.28  4906.9   52.47  4967.3   37.42  4979.7   30.84
  5003.8   30.55  5021.5   31.35  5027.4   34.35  5069.2   44.38  5091.5   45.26
  5107.6   52.27  5187.8  52.494  5496.8   52.65  5560.8   53.07 5667.82   55.88
  5760.8   55.03  6010.8   59.68    6130  61.734  6647.2      61    7013    62.7
#Mann= 16 ,-1 , 0
  2384.5     .14       0  2893.8    .045       0  3724.8     .04       0
  4090.8    .045       0  4301.8     .04       0  4413.8    .045       0
  4634.8     .06       0  4693.8    .045       0  4906.9    .035       0
  5107.6    .045       0  5187.8     .11       0  5496.8     .06       0
  5560.8     .04       0  5760.8     .06       0  6010.8     .04       0
    6130     .11       0
Bank Sta=4906.9,5107.6
XS Rating Curve= 0 ,0
Exp/Cntr=0.3,0.1

Type RM Length L Ch R = 1 ,107478.1,805.91,798.48,629.08
BEGIN DESCRIPTION:
Cross Section 107478.1
END DESCRIPTION:
XS GIS Cut Line= 5
      3151077.33      13901990.8      3151231.25     13901058.24
      3151539.08     13899989.87      3151946.51     13899319.88
      3152535.02     13898043.27
#Sta/Elev= 30
    2409    62.6  3242.6  52.743  3459.2    50.7  3849.2    53.3  3974.2    50.8
  4352.6  52.416  4394.2    55.9    4492   55.78    4651    51.2    4877   53.34
  4969.2   36.54  4980.2   29.52  4998.6   28.86  5020.4   29.41    5021   31.35
  5063.4   41.88  5084.3   44.78  5096.3    53.7  5153.6   55.58 5182.05   58.87
 5207.87   53.86  5248.6   53.11  5418.6  53.695 5488.94   58.73  5625.6  55.696
  5845.6   55.61  5990.6  57.245  6086.6  59.872  6240.2    58.1  6655.9    60.3
#Mann= 13 ,-1 , 0
    2409     .14       0  3242.6    .045       0  4352.6     .04       0
    4492    .045       0    4877    .035       0  5096.3    .045       0
  5153.6     .04       0  5248.6    .045       0  5418.6     .04       0
  5625.6     .11       0  5845.6     .04       0  5990.6     .11       0
  6086.6     .04       0
Bank Sta=4877,5096.3
XS Rating Curve= 0 ,0
Exp/Cntr=0.3,0.1

Type RM Length L Ch R = 1 ,106679.6,302.8,290.6,237.8
BEGIN DESCRIPTION:
Cross Section 106679.6-Interpolated
END DESCRIPTION:
XS GIS Cut Line= 6
      3151132.94       13901959.      3151566.47     13901248.92
      3152489.49      13900091.3      3152592.09     13899617.39
      3152573.17     13899072.89      3152522.01     13898145.27
#Sta/Elev= 30
  2456.7    62.5  2856.7      57  2886.7    54.8  3288.6    52.1  3888.6    51.2
  3928.6      49  3988.6    51.6  4272.3  51.511  4332.3  52.182  4401.3  50.365
    4469   50.22  4539.3  50.717  4655.3      49  4738.6    51.9  4907.1   51.66
  4915.5      47  4976.5   32.45  4979.3      28  5019.7   29.38  5051.7   43.33
  5079.8   51.75 5103.32   53.87  5219.2      52  5249.2    50.4  6059.3   54.85
 6090.92   54.87  6110.8   57.84 6330.72   62.71 6404.03    57.1  6727.9    60.2
#Mann= 11 ,-1 , 0
  2456.7     .14       0  4272.3    .045       0  4332.3     .04       0
  4401.3     .06       0    4469    .045       0  4539.3     .04       0
  4655.3    .045       0  4907.1    .035       0  5079.8    .045       0
  5219.2     .11       0  6059.3     .04       0
Bank Sta=4907.1,5079.8
XS Rating Curve= 0 ,0
Exp/Cntr=0.3,0.1

Type RM Length L Ch R = 1 ,106389.0,170.2,171.3,180.2
BEGIN DESCRIPTION:
Cross Section 106389.0-Interpolated
END DESCRIPTION:
XS GIS Cut Line= 6
      3151139.17     13901956.07      3151806.48     13901352.92
      3152781.79     13900082.46      3152845.95     13899838.63
      3152720.98     13899000.08       3152529.4     13898160.93
#Sta/Elev= 30
  2346.4    62.1  2876.4    54.3  3245.9    51.8  3865.9    51.2  3915.9    48.6
  3975.9    51.5  4242.3  51.455  4315.3  52.115  4461.3  51.833  4847.6      51
  4907.1   53.62  4915.5   46.96  4928.1   41.75  4976.5   32.41  4979.3   27.96
  5019.7   29.34  5023.6   32.51  5051.7   43.29  5079.8   51.71  5150.3  55.779
 5190.77   57.83  5262.4   53.67  5359.7    51.4  5609.7    51.9  5889.7    56.9
 6182.91   54.71 6216.71   62.76 6321.52   61.83 6382.19   55.77  6808.2    60.1
#Mann= 9 ,-1 , 0
  2346.4     .14       0  4242.3    .045       0  4315.3     .04       0
  4461.3    .045       0  4907.1    .035       0  5079.8    .045       0
  5150.3     .04       0  5262.4     .11       0 6182.91     .04       0
Bank Sta=4907.1,5079.8
XS Rating Curve= 0 ,0
Exp/Cntr=0.5,0.3

Type RM Length L Ch R = 1 ,106217.7,32,32,32
BEGIN DESCRIPTION:
Upstream Section of Bridge/Culvert/Weir
END DESCRIPTION:
XS GIS Cut Line= 6
      3151181.54     13902038.99      3151967.02      13901424.2
      3152979.99     13900148.44      3152955.61     13899213.92
      3152687.97     13898439.56        3152566.     13898193.97
#Sta/Elev= 30
  2201.6   62.09  2891.6   53.59  3224.7   51.59  3844.7   48.39  3894.7   51.59
  4233.1  51.291  4323.1  51.908  4572.1  51.368  4784.7   50.39  4907.1    53.6
  4915.5   46.94  4928.1   41.73  4955.2    37.9  4956.7   34.81  4972.4   29.38
  4976.5   32.39  4979.3   27.94  5019.7   29.32  5045.7   42.01  5079.8   51.69
 5165.75   54.83 5190.74   56.92 5290.68   56.89  5332.3   51.81 5719.98    52.4
  5857.4   56.89    6286  55.713 6337.25   62.74    6400   55.57  6857.7   59.99
#Mann= 11 ,-1 , 0
  2201.6     .14       0  4233.1     .06       0  4323.1     .04       0
  4572.1    .045       0  4907.1    .035       0  5079.8    .045       0
 5165.75     .04       0  5332.3     .06       0 5719.98     .11       0
    6286     .04       0  6857.7      .2       0
#XS Ineff= 2 , 0
       0    4946    51.9 5079.68       0    51.6
Permanent Ineff=
       F       F
Bank Sta=4907.1,5079.8
XS Rating Curve= 0 ,0
Exp/Cntr=0.5,0.3

Type RM Length L Ch R = 1 ,106185.7,496.6,496.6,496.6
BEGIN DESCRIPTION:
Downstream Section of Bridge/Culvert/Weir
END DESCRIPTION:
XS GIS Cut Line= 6
      3151212.62     13902046.63       3151998.1     13901431.84
      3153011.07     13900156.08      3152986.69     13899221.56
      3152719.05      13898447.2      3152597.08      13898201.6
#Sta/Elev= 30
  2201.6   62.02  3224.7   51.52  3844.7   48.32  3894.7   51.52  4224.1  51.229
  4362.1   52.12  4592.1  50.862  4784.7   50.32  4907.1   53.53  4915.5   46.87
  4928.1   41.66  4955.2   37.83  4956.7   34.74  4972.4   29.31  4976.5   32.32
  4979.3   27.87  5019.7   29.25  5045.7   41.94  5079.8   51.62  5150.9    54.2
    5307   55.88    5536   52.22 5593.36   38.01 5625.07   38.01 5706.39   40.01
    5783      55    5795  55.206  5857.4   56.82    6333   55.38  6857.7   59.92
#Mann= 12 ,-1 , 0
  2201.6     .14       0  4224.1     .06       0  4362.1     .04       0
  4592.1    .045       0  4907.1    .035       0  5079.8    .045       0
  5150.9     .04       0    5307     .06       0    5536    .045       0
    5795     .11       0    6333     .04       0  6857.7      .2       0
#XS Ineff= 1 ,-1
    5542    5769      51
Permanent Ineff=
       T
Bank Sta=4907.1,5079.8
XS Rating Curve= 0 ,0
Exp/Cntr=0.5,0.3

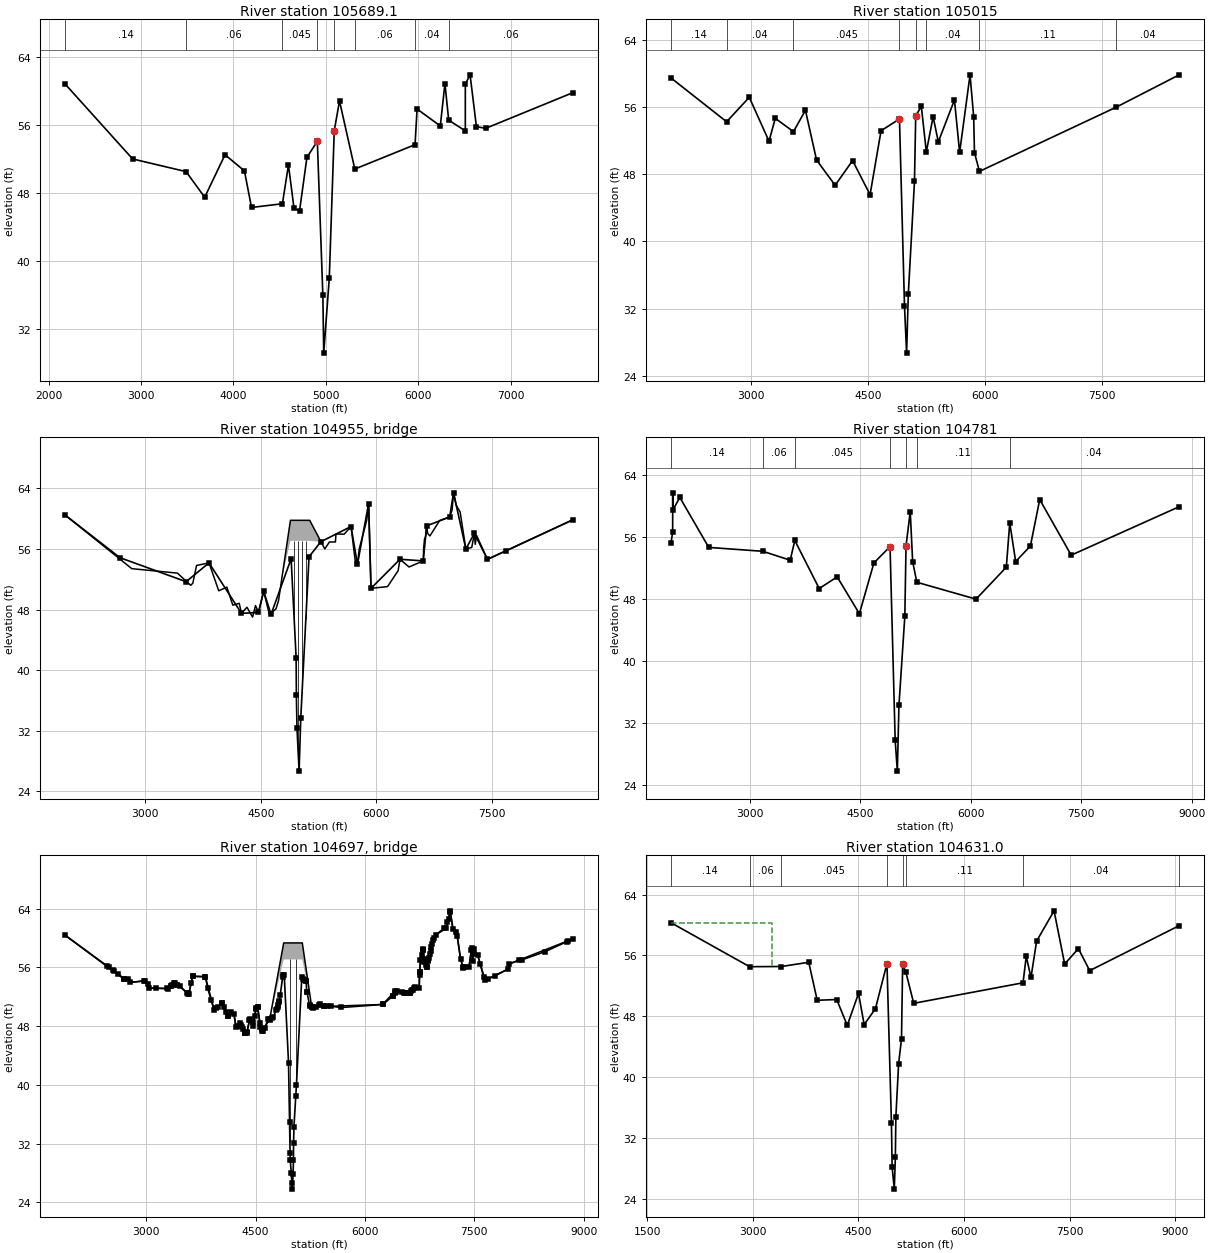
Type RM Length L Ch R = 1 ,105689.1,679.73,674,607.82
BEGIN DESCRIPTION:
Cross Section 105689.1
END DESCRIPTION:
XS GIS Cut Line= 6
      3151359.29     13902076.33      3152924.34     13900804.73
      3153648.66     13899989.87      3153657.71     13899165.96
      3153422.31     13898523.13      3152649.54     13898137.04
#Sta/Elev= 30
  2179.5    60.8  2909.5      52  3487.5  50.516  3689.5    47.5  3909.5    52.5
  4119.5    50.6    4196    46.3  4530.5  46.738    4596    51.3    4656    46.2
    4716    45.9    4796    52.2  4908.5   54.07  4968.2   35.99  4977.7   29.18
  5037.9   38.01  5091.5   55.32 5148.37   58.82    5314  50.816    5966  53.683
 5987.99   57.87 6239.39   55.88 6289.43   60.87    6330  56.567    6510    55.3
  6510.2    60.8 6561.58   61.89  6630.2    55.8  6730.2    55.6  7675.3    59.8
#Mann= 8 ,-1 , 0
  2179.5     .14       0  3487.5     .06       0  4530.5    .045       0
  4908.5    .035       0  5091.5    .045       0    5314     .06       0
    5966     .04       0    6330     .06       0
Bank Sta=4908.5,5091.5
XS Rating Curve= 0 ,0
Exp/Cntr=0.3,0.1

Type RM Length L Ch R = 1 ,105015  ,235.99,234,211.02
XS GIS Cut Line= 6
   3151802.5528213902748.5273315 3152577.108437413902099.3790097
 3154207.963367313900361.2755618 3154170.312094813899291.7719993
 3153986.2632478 13898850.250579 3152646.8136792 13898108.018697
#Sta/Elev= 30
 1978.02    59.5 2690.02   54.28 2980.56    57.2 3233.63   51.96 3314.09   54.69
 3547.02    53.1 3700.42   55.65 3843.02   49.72 4081.32    46.7 4305.09   49.65
 4529.02   45.58 4670.14   53.21 4906.14   54.61 4970.45   32.33 4997.51   26.68
 5019.28   33.69  5098.5   47.16 5114.37   54.99 5186.38   56.11 5250.45   50.69
 5337.51   54.88 5404.18   51.88 5610.84   56.88 5677.51   50.62 5810.84   59.88
 5857.51   54.88 5867.67   50.59 5931.37   48.36 7680.37      56 8488.16   59.86
#Mann= 8 ,-1 , 0
 1978.02     .14       0 2690.02     .04       0 3547.02    .045       0
 4906.14    .035       0 5114.37    .045       0 5250.45     .04       0
 5931.37     .11       0 7680.37     .04       0
Bank Sta=4906.14,5114.37
XS Rating Curve= 0 ,0
Exp/Cntr=0.3,0.1

Type RM Length L Ch R = 3 ,104955  ,,,
BEGIN DESCRIPTION:
Redstone Golf Course VEHICULAR BRIDGE
END DESCRIPTION:
Bridge Culvert--1,0,-1,-1, 0
Deck Dist Width WeirC Skew NumUp NumDn MinLoCord MaxHiCord MaxSubmerge Is_Ogee
45,24,2.6,0, 60, 60, , , 0.95, 0, 3,3,,
 1962.92 2827.08 3418.89 3591.45 3619.03 3667.04 3828.72 3955.09 4060.71 4137.52
 4220.96 4249.77 4321.05  4393.8 4432.21  4470.6 4537.83 4612.25 4698.53 4730.88
 4885.14 4885.14 5135.37 5135.37 5330.83 5390.97 5468.87  5475.7 5582.31 5671.15
 5731.28 5754.52 5777.75 5874.79 5899.39 5930.37 6144.68 6282.32 6306.66 6423.53
 6608.43 6612.71 6624.37 6641.01 6652.03 6665.62 6694.58 6821.44 6951.04 6981.87
 7001.34 7034.04 7086.95 7160.77 7237.43 7271.41 7282.57 7300.54 7441.19 8550.71
   60.48   53.41   52.82   51.21   51.49   53.83   54.17   50.49   50.97   48.59
   48.83   47.51   48.31   47.02   48.53   47.63   50.42   47.37   48.11    49.2
   59.79   59.79   59.79   59.79   56.01   56.93   56.93   57.99   57.96   58.97
   53.99   53.99   56.01   59.79   62.01  50.809   51.04   53.14   54.65   53.63
   54.43   56.01   57.31   57.73   59.06   58.05   57.73   59.77   60.23   61.14
   63.42   61.82   60.88   56.01   56.21   58.07   56.62   57.78   54.64   59.87
   60.48   53.41   52.82   51.21   51.49   53.83   54.17   50.49   50.97   48.59
   48.83   47.51   48.31   47.02   48.53   47.63   50.42   47.37   48.11    49.2
           57.08   57.08           56.01   56.93   56.93   57.99   57.96   58.97
   53.99   53.99   56.01   59.79   62.01  50.809   51.04   53.14   54.65   53.63
   54.43   56.01   57.31   57.73   59.06   58.05   57.73   59.77   60.23   61.14
   63.42   61.82   60.88   56.01   56.21   58.07   56.62   57.78   54.64   59.87
 1887.73 2562.24 2694.93 2694.97 3024.56 3132.92 3424.72 3428.67 3557.41 3585.69
 3634.91 3645.88 3812.11 3930.24 4066.06 4117.48 4232.36 4316.51 4416.03 4471.32
 4487.35 4504.49 4508.01  4527.7 4586.76 4692.47 4703.53 4725.64    4888    4888
    5139    5139 5322.56 6241.37  6417.3  6621.8 6745.06 6749.71 6762.37 6792.42
 6797.17 6807.18 6856.21  6866.2 6932.66 7117.18 7168.33 7207.33  7264.8 7311.72
 7344.98 7428.24 7465.15 7477.27 7496.78 7547.38 7649.55 7963.57  7982.6 8854.64
   60.73   55.05   54.85   53.78   53.41   52.71   52.74   52.02   51.99   51.21
   51.49   53.04   53.86   50.25   50.61   49.07   47.87   47.91   47.02   48.53
   47.63      48   48.71   49.74   47.36   47.38   48.22   48.11   59.79   59.79
   59.79   59.79   50.61   50.95    52.8   52.53   53.19   55.32   57.07   58.41
   58.44   56.82   56.06   56.98   59.72    61.3    63.7   61.26   60.34    57.2
   56.08   56.06   58.64   56.83   58.54   57.67   54.25   55.77   56.48   59.89
   60.73   55.05   54.85   53.78   53.41   52.71   52.74   52.02   51.99   51.21
   51.49   53.04   53.86   50.25   50.61   49.07   47.87   47.91   47.02   48.53
   47.63      48   48.71   49.74   47.36   47.38   48.22   48.11           57.08
   57.08           50.61   50.95    52.8   52.53   53.19   55.32   57.07   58.41
   58.44   56.82   56.06   56.98   59.72    61.3    63.7   61.26   60.34    57.2
   56.08   56.06   58.64   56.83   58.54   57.67   54.25   55.77   56.48   59.89
Pier Skew, UpSta & Num, DnSta & Num=  ,4935.14, 2 ,4938, 2 , 0 , 0 , 0 ,,
     2.5     2.5
      40      58
     2.5     2.5
      40      58
Pier Skew, UpSta & Num, DnSta & Num=  ,4985.14, 2 ,4988, 2 , 0 , 0 , 0 ,,
     2.5     2.5
      40      58
     2.5     2.5
      40      58
Pier Skew, UpSta & Num, DnSta & Num=  ,5035.14, 2 ,5038, 2 , 0 , 0 , 0 ,,
     2.5     2.5
      40      58
     2.5     2.5
      40      58
Pier Skew, UpSta & Num, DnSta & Num=  ,5085.14, 2 ,5088, 2 , 0 , 0 , 0 ,,
     2.5     2.5
      40      58
     2.5     2.5
      40      58
BR Coef=-1 , 1 , 0 ,1.25, 0 ,,,0.8,0,2,0,
WSPro=,,,, 1 ,,,, 0 ,,,, 0 ,,,,-1 ,-1 ,-1 , 0 , 0 , 0 , 0 , 0
BR U #Sta/Elev= 30
 1962.92   60.48 2674.73   54.85 3531.92  51.688 3828.72   54.17 4249.77   47.51
  4470.6   47.63 4537.83   50.42 4633.82   47.38 4894.14   54.72 4959.14   41.62
  4962.2   36.72 4970.45   32.33 4997.51   26.68 5019.28   33.69 5126.37   54.98
 5278.89   56.96 5671.15   58.97 5754.52   53.99 5899.39   62.01 5930.37  50.809
 6306.66   54.65 6608.43   54.43 6652.03   59.06 6951.04   60.23 7001.34   63.42
 7160.77   56.01 7271.41   58.07 7441.19   54.64 7679.37  55.746 8550.71   59.87
BR U #Mann= 8
 1962.92     .14 2674.73     .04 3531.92    .045 4894.14    .035 5126.37    .045
 5278.89     .04 5930.37     .11 7679.37     .04
BR U Banks=4894.14,5126.37
BR D #Sta/Elev= 200
 1887.73   60.37 2462.72    56.2 2484.84   56.11 2540.12   55.68 2562.24   55.45
 2617.53   55.14 2694.93    54.4 2694.97    54.4 2754.04   54.47 2773.72   53.95
 2975.34   54.16 2985.18   54.09 3024.56    53.8 3044.25   53.19 3132.92  53.155
 3280.98   53.13  3300.2   53.11 3334.05   53.44 3336.26   53.46 3348.32   53.56
 3380.49   53.84  3388.8   53.87 3424.72   53.56 3428.67   53.56 3457.71   53.52
 3557.41    52.5 3567.92  52.482 3579.53   52.41 3585.69   52.41  3612.7   53.82
 3634.91   54.79 3645.88   54.79 3800.68   54.75 3812.11    54.7 3841.64   53.25
 3889.14   51.55 3930.24   50.25 3955.49   50.52  3977.6   50.56 4032.89   51.15
 4038.53   51.17 4066.06   50.61 4088.18   49.89 4117.28   49.39 4117.48   49.39
 4163.45   49.91 4202.83   49.67 4232.36   47.87 4250.17   47.98 4291.43   48.45
 4305.46   48.18 4316.51   47.91 4327.57   47.55 4349.69   47.05  4350.5   47.02
 4360.74    47.1 4380.03   47.13 4382.86   47.22 4416.03    48.8 4419.41   48.94
 4458.78   47.98 4471.32   48.56 4487.35   49.39 4504.49   50.28 4508.01   50.51
  4526.6   50.65  4527.7   50.65 4559.78   48.42 4567.07   47.85 4581.89   47.55
 4586.76   47.36 4604.01   47.39 4626.12   47.79 4675.36      49 4692.47   48.88
 4703.53   48.94 4725.64   49.16 4744.27   49.18 4780.93   50.23 4789.65   50.38
 4803.04    50.6 4813.18   50.86 4823.03   51.33 4824.72   51.43 4838.29   52.24
 4870.27   54.63 4876.09   55.01    4897   54.86 4969.75   40.31 4973.15   30.77
 4975.05    29.8 4990.79   27.94 4997.95   26.61 5004.39   25.81 5014.33   27.82
  5019.6   29.72 5021.09   32.03 5026.36   34.31 5050.81   38.52 5065.63   41.21
 5071.75   41.31    5130   54.76 5151.24   54.44 5163.91   54.28 5166.46   54.26
 5186.82   54.12 5192.54   54.11 5202.05   52.71 5204.46   52.67 5240.11   50.88
    5245    50.8 5269.37   50.62 5272.18   50.57 5294.36   50.52 5322.56   50.61
 5366.63    50.9 5389.56   50.98 5438.92   50.71 5443.71   50.72 5481.53   50.79
 5530.64   50.71 5678.01   50.54 6241.37   50.95 6253.85   51.01 6385.54   52.12
 6390.87   52.16  6406.1   52.55  6417.3    52.8 6427.89   52.67  6436.7   52.81
 6508.97   52.59 6530.37  52.517 6544.23   52.47 6575.97    52.5  6621.8   52.53
 6624.97   52.58 6632.37   52.77 6642.95   52.88 6664.11   52.97 6678.45   53.22
 6688.78   53.27 6745.06   53.19 6748.96   54.98 6749.71   55.32 6750.49   55.43
 6762.37   57.07 6780.45   57.63 6791.04   58.36 6792.42   58.41 6797.17   58.44
 6805.58   57.08 6807.18   56.82 6815.71   56.71 6838.64   56.26 6852.73   56.12
 6856.21   56.06 6865.07   56.89  6866.2   56.98 6866.22   56.98 6875.65   57.34
 6891.52   57.87  6900.5   58.24 6911.34   58.71 6921.48   59.14 6932.66   59.72
  6946.3  59.954 6976.42   60.47  7090.3   61.34 7117.18    61.3 7130.36   62.12
 7150.67   62.58 7168.33    63.7 7171.81    63.6 7207.33   61.26 7245.86   60.82
  7264.8   60.34 7311.72    57.2 7344.98   56.08 7351.26   55.97 7373.87   56.06
 7428.24   56.06 7460.54   58.33 7465.15   58.64 7477.27   56.83 7489.43   57.87
 7496.78   58.54 7547.38   57.67 7582.75    56.4 7630.52   54.68 7649.55   54.25
 7683.86   54.41 7784.98   54.85 7963.57   55.77  7982.6   56.48 8117.22   56.99
 8160.55   57.05 8467.92   58.13 8766.53   59.49 8782.42   59.56 8854.64   59.89
BR D #Mann= 7
 1887.73     .14 3132.92     .06 3567.92    .045    4897    .035 5163.91    .045
 5294.36     .11 6575.97     .04
BR D Banks=4897,5130
BC Design=,, 0 ,, 0 ,,,,,,
BC HTab HWMax=59.88
BC Use User HTab Curves=0
BC User HTab FreeFlow(D)= 0

Type RM Length L Ch R = 1 ,104781  ,151.38,150.1,135.36
XS GIS Cut Line= 6
 3151956.445254313902981.9014792 3152771.734033713902292.7752255
 3154461.987700213900422.8950906 3154348.923292613899276.6866931
  3154128.39188913898817.2717319 3152645.867152413898097.9430517
#Sta/Elev= 30
 1932.85   55.32 1954.34   56.67 1955.39   61.75 1956.09   59.52 2051.77   61.15
 2444.58    54.7 3177.85    54.2 3550.12   53.05 3612.85    55.6 3943.74   49.39
 4187.64    50.9  4488.9   46.14 4686.46    52.7 4905.32    54.8 4975.05    29.8
 5004.39   25.81 5026.36   34.31  5106.3   45.86 5122.31   54.88 5179.64   59.32
  5212.2   52.86 5269.31    50.2  6073.1   48.02    6484   52.15 6530.31   57.88
 6610.67   52.88 6810.67   54.88 6937.33   60.88 7364.76    53.7 8826.35   59.94
#Mann= 7 ,-1 , 0
 1932.85     .14       0 3177.85     .06       0 3612.85    .045       0
 4905.32    .035       0 5122.31    .045       0 5269.31     .11       0
 6530.31     .04       0
Bank Sta=4905.32,5122.31
XS Rating Curve= 0 ,0
Exp/Cntr=0.3,0.1

Type RM Length L Ch R = 3 ,104697  ,,,
BEGIN DESCRIPTION:
Redstone Golf Course CARTPATH BRIDGE
END DESCRIPTION:
Bridge Culvert--1,0,-1,-1, 0
Deck Dist Width WeirC Skew NumUp NumDn MinLoCord MaxHiCord MaxSubmerge Is_Ogee
75,12,2.6,0, 60, 60, , , 0.95, 0, 3,3,,
 1887.73 2694.93 2754.04 2773.72 2975.34 3044.25  3300.2  3388.8 3585.69 3634.91
 3812.11 3930.24 4038.53 4117.28 4202.83 4232.36 4291.43  4350.5 4380.03 4419.41
 4458.78 4508.01  4526.6 4567.07 4586.76 4692.47    4886    4886    5141    5141
 5269.37 6241.37  6417.3  6621.8 6678.45 6745.06 6749.71 6762.37 6792.42 6797.17
 6807.18 6856.21  6866.2 6932.66 6976.42 7117.18 7168.33 7207.33  7264.8 7311.72
 7344.98 7428.24 7465.15 7477.27 7496.78 7547.38 7649.55 7963.57  7982.6 8854.64
   60.37    54.4   54.47   53.95   54.16   53.19   53.11   53.87   52.41   54.79
    54.7   50.25   51.17   49.39   49.67   47.87   48.45   47.02   47.13   48.94
   47.98   50.51   50.65   47.85   47.36   48.88   59.33   59.33   59.33   59.33
   50.62   50.95    52.8   52.53   53.22   53.19   55.32   57.07   58.41   58.44
   56.82   56.06   56.98   59.72   60.47    61.3    63.7   61.26   60.34    57.2
   56.08   56.06   58.64   56.83   58.54   57.67   54.25   55.77   56.48   59.89
   60.37    54.4   54.47   53.95   54.16   53.19   53.11   53.87   52.41   54.79
    54.7   50.25   51.17   49.39   49.67   47.87   48.45   47.02   47.13   48.94
   47.98   50.51   50.65   47.85   47.36   48.88           57.08   57.08
   50.62   50.95    52.8   52.53   53.22   53.19   55.32   57.07   58.41   58.44
   56.82   56.06   56.98   59.72   60.47    61.3    63.7   61.26   60.34    57.2
   56.08   56.06   58.64   56.83   58.54   57.67   54.25   55.77   56.48   59.89
  1839.5  2659.5  2719.5  2739.5  2944.3  3014.3  3274.3  3364.3  3434.3  3564.3
  3614.3  3794.3  3914.3  4024.3  4104.3  4151.2  4191.2  4221.2  4281.2  4341.2
  4371.2  4411.2  4451.2  4501.2  4521.2  4561.2  4581.2  4671.2  4888.6  4888.6
  5143.6  5143.6  5284.9  5504.9  6316.5  6832.7 6837.59 6850.89 6882.47 6887.46
 6897.98 6949.51 7029.84 7075.83 7223.75  7237.6  7277.5 7318.49 7378.88 7428.19
 7469.74 7550.63 7589.42 7602.16 7622.66 7675.84  7783.2  8113.2  8133.2  9049.6
    60.3    54.8    54.9    54.3    54.6    53.5    53.5    54.6    54.5      53
    55.4    55.1    50.1    51.3    49.9    50.5    50.2    48.1    48.5    46.8
    47.2    49.2    48.2      51    50.8    47.3    46.9    49.5   59.33   59.33
   59.33   59.33    49.7    50.5    50.9    52.4   54.88   56.92   57.99   57.99
   56.03   54.91   60.01   60.92   61.99   62.96   63.99    60.9   59.99   56.98
   55.96   55.96      59   56.96   59.02      58      54    55.6    56.4    59.9
    60.3    54.8    54.9    54.3    54.6    53.5    53.5    54.6    54.5      53
    55.4    55.1    50.1    51.3    49.9    50.5    50.2    48.1    48.5    46.8
    47.2    49.2    48.2      51    50.8    47.3    46.9    49.5           57.08
   57.08            49.7    50.5    50.9    52.4   54.88   56.92   57.99   57.99
   56.03   54.91   60.01   60.92   61.99   62.96   63.99    60.9   59.99   56.98
   55.96   55.96      59   56.96   59.02      58      54    55.6    56.4    59.9
Pier Skew, UpSta & Num, DnSta & Num=  ,4971, 2 ,4973, 2 , 0 , 0 , 0 ,,
     2.5     2.5
      40      58
     2.5     2.5
      40      58
Pier Skew, UpSta & Num, DnSta & Num=  ,5056, 2 ,5058, 2 , 0 , 0 , 0 ,,
     2.5     2.5
      40      58
     2.5     2.5
      40      58
BR Coef=-1 , 0 , 0 ,, 0 ,,,0.8,-1,,0,
WSPro=,,,, 1 ,,,, 0 ,,,, 0 ,,,,-1 ,-1 ,-1 , 0 , 0 , 0 , 0 , 0
BR U #Sta/Elev= 200
 1887.73   60.37 2462.72    56.2 2484.84   56.11 2540.12   55.68 2562.24   55.45
 2617.53   55.14 2694.93    54.4 2694.97    54.4 2754.04   54.47 2773.72   53.95
 2975.34   54.16 2985.18   54.09 3024.56    53.8 3044.25   53.19 3132.92  53.155
 3280.98   53.13  3300.2   53.11 3334.05   53.44 3336.26   53.46 3348.32   53.56
 3380.49   53.84  3388.8   53.87 3424.72   53.56 3428.67   53.56 3457.71   53.52
 3557.41    52.5 3567.92  52.482 3579.53   52.41 3585.69   52.41  3612.7   53.82
 3634.91   54.79 3645.88   54.79 3800.68   54.75 3812.11    54.7 3841.64   53.25
 3889.14   51.55 3930.24   50.25 3955.49   50.52  3977.6   50.56 4032.89   51.15
 4038.53   51.17 4066.06   50.61 4088.18   49.89 4117.28   49.39 4117.48   49.39
 4163.45   49.91 4202.83   49.67 4232.36   47.87 4250.17   47.98 4291.43   48.45
 4305.46   48.18 4316.51   47.91 4327.57   47.55 4349.69   47.05  4350.5   47.02
 4360.74    47.1 4380.03   47.13 4382.86   47.22 4416.03    48.8 4419.41   48.94
 4458.78   47.98 4471.32   48.56 4487.35   49.39 4504.49   50.28 4508.01   50.51
  4526.6   50.65  4527.7   50.65 4559.78   48.42 4567.07   47.85 4581.89   47.55
 4586.76   47.36 4604.01   47.39 4626.12   47.79 4675.36      49 4692.47   48.88
 4703.53   48.94 4725.64   49.16 4744.27   49.18 4780.93   50.23 4789.65   50.38
 4803.04    50.6 4813.18   50.86 4823.03   51.33 4824.72   51.43 4838.29   52.24
 4870.27   54.63 4876.09   55.01    4893   54.98    4952      43  4966.1      35
 4973.15   30.77 4975.05    29.8 4990.79   27.94 4997.95   26.61 5004.39   25.81
 5014.33   27.82  5019.6   29.72 5021.09   32.03 5026.36   34.31 5050.81   38.52
 5060.55      40    5134   54.69 5151.24   54.44 5163.91   54.28 5166.46   54.26
 5186.82   54.12 5192.54   54.11 5202.05   52.71 5204.46   52.67 5240.11   50.88
    5245    50.8 5269.37   50.62 5272.18   50.57 5294.36   50.52 5322.56   50.61
 5366.63    50.9 5389.56   50.98 5438.92   50.71 5443.71   50.72 5481.53   50.79
 5530.64   50.71 5678.01   50.54 6241.37   50.95 6253.85   51.01 6385.54   52.12
 6390.87   52.16  6406.1   52.55  6417.3    52.8 6427.89   52.67  6436.7   52.81
 6508.97   52.59 6530.37  52.517 6544.23   52.47 6575.97    52.5  6621.8   52.53
 6624.97   52.58 6632.37   52.77 6642.95   52.88 6664.11   52.97 6678.45   53.22
 6688.78   53.27 6745.06   53.19 6748.96   54.98 6749.71   55.32 6750.49   55.43
 6762.37   57.07 6780.45   57.63 6791.04   58.36 6792.42   58.41 6797.17   58.44
 6805.58   57.08 6807.18   56.82 6815.71   56.71 6838.64   56.26 6852.73   56.12
 6856.21   56.06 6865.07   56.89  6866.2   56.98 6866.22   56.98 6875.65   57.34
 6891.52   57.87  6900.5   58.24 6911.34   58.71 6921.48   59.14 6932.66   59.72
  6946.3  59.954 6976.42   60.47  7090.3   61.34 7117.18    61.3 7130.36   62.12
 7150.67   62.58 7168.33    63.7 7171.81    63.6 7207.33   61.26 7245.86   60.82
  7264.8   60.34 7311.72    57.2 7344.98   56.08 7351.26   55.97 7373.87   56.06
 7428.24   56.06 7460.54   58.33 7465.15   58.64 7477.27   56.83 7489.43   57.87
 7496.78   58.54 7547.38   57.67 7582.75    56.4 7630.52   54.68 7649.55   54.25
 7683.86   54.41 7784.98   54.85 7963.57   55.77  7982.6   56.48 8117.22   56.99
 8160.55   57.05 8467.92   58.13 8766.53   59.49 8782.42   59.56 8854.64   59.89
BR U #Mann= 7
 1887.73     .14 3132.92     .06 3567.92    .045    4893    .035    5134    .045
 5269.37     .11 6530.37     .04
BR U Banks=4893,5134
BR D #Sta/Elev= 95
  1839.5    60.3  2659.5    54.8  2719.5    54.9  2739.5    54.3  2944.3    54.6
  2954.3   54.52  2994.3    54.2  3014.3    53.5  3274.3    53.5  3364.3    54.6
  3404.8  54.542  3434.3    54.5  3564.3      53  3614.3    55.4  3794.3    55.1
  3824.3    53.5  3914.3    50.1  4024.3    51.3  4104.3    49.9  4151.2    50.5
  4191.2    50.2  4221.2    48.1  4281.2    48.5  4341.2    46.8  4371.2    47.2
  4411.2    49.2  4451.2    48.2  4501.2      51  4521.2    50.8  4561.2    47.3
  4581.2    46.9  4671.2    49.5  4741.2      49  4787.3   50.12  4811.2    50.7
  4821.2    51.2  4836.7   52.13  4875.1    55.1 4895.58   54.98 4955.48      43
    4976   29.23    4978   28.18  5008.8   25.25  5018.8   27.39  5024.1    29.5
  5025.6   32.16  5030.9   34.71 5063.53      40 5136.53    54.6  5157.8   54.11
  5173.8  53.775  5201.2    53.2  5211.2    51.4  5251.2    49.8  5284.9    49.7
  5504.9    50.5  5556.5    50.5  6316.5    50.9  6476.5    51.6  6706.5    51.8
  6762.7    52.5  6832.7    52.4  6836.8  54.479 6837.59   54.88 6850.89   56.92
 6882.47   57.99 6887.46   57.99  6896.3  56.343 6897.98   56.03 6949.51   54.91
    6960  56.007 6960.03   56.01 6996.05   58.05 7029.84   60.01 7075.83   60.92
  7195.5   62.02 7223.75   61.99  7237.6   62.96  7277.5   63.99 7318.49    60.9
 7378.88   59.99 7428.19   56.98 7469.74   55.96 7550.63   55.96 7589.42      59
 7602.16   56.96 7622.66   59.02 7675.84      58  7763.2    54.5  7783.2      54
  8113.2    55.6  8133.2    56.4  8643.2    58.1    8957    59.5  9049.6    59.9
BR D #Mann= 7
  1839.5     .14  2954.3     .06  3404.8    .045 4895.58    .035 5136.53    .045
  5173.8     .11  6836.8     .04
BR D Banks=4895.58,5136.53
BC Design=,, 0 ,, 0 ,,,,,,
BC HTab HWMax=61.75
BC Use User HTab Curves=0
BC User HTab FreeFlow(D)= 0

Type RM Length L Ch R = 1 ,104631.0,884.5,865.5,810.2
BEGIN DESCRIPTION:
Cross Section 104631.0
END DESCRIPTION:
XS GIS Cut Line= 6
      3152055.16      13903131.6      3152897.18     13902416.34
      3154626.48     13900460.68      3154463.51     13899265.55
      3154219.06     13898794.75      3152645.26     13898091.48
#Sta/Elev= 30
  1839.5    60.3  2954.3   54.52  3404.8  54.542  3794.3    55.1  3914.3    50.1
  4191.2    50.2  4341.2    46.8  4501.2      51  4581.2    46.9  4741.2      49
  4904.8   54.92  4968.6   33.89    4978   28.18  5008.8   25.25  5024.1    29.5
  5030.9   34.71  5070.4   41.77  5111.3   45.02  5127.4   54.81  5173.8  53.775
  5284.9    49.7  6836.8    52.4 6882.47   55.87 6949.51    53.1 7029.84   57.89
  7277.5   61.87 7428.19   54.86 7622.66    56.9  7783.2      54  9049.6    59.9
#Mann= 8 ,-1 , 0
  1839.5     .14       0  2954.3     .06       0  3404.8    .045       0
  4904.8    .035       0  5127.4    .045       0  5173.8     .11       0
  6836.8     .04       0  9049.6      .2       0
#XS Ineff= 1 ,-1
  1839.5    3279    60.3
Permanent Ineff=
       T
Bank Sta=4904.8,5127.4
XS Rating Curve= 0 ,0
Exp/Cntr=0.3,0.1

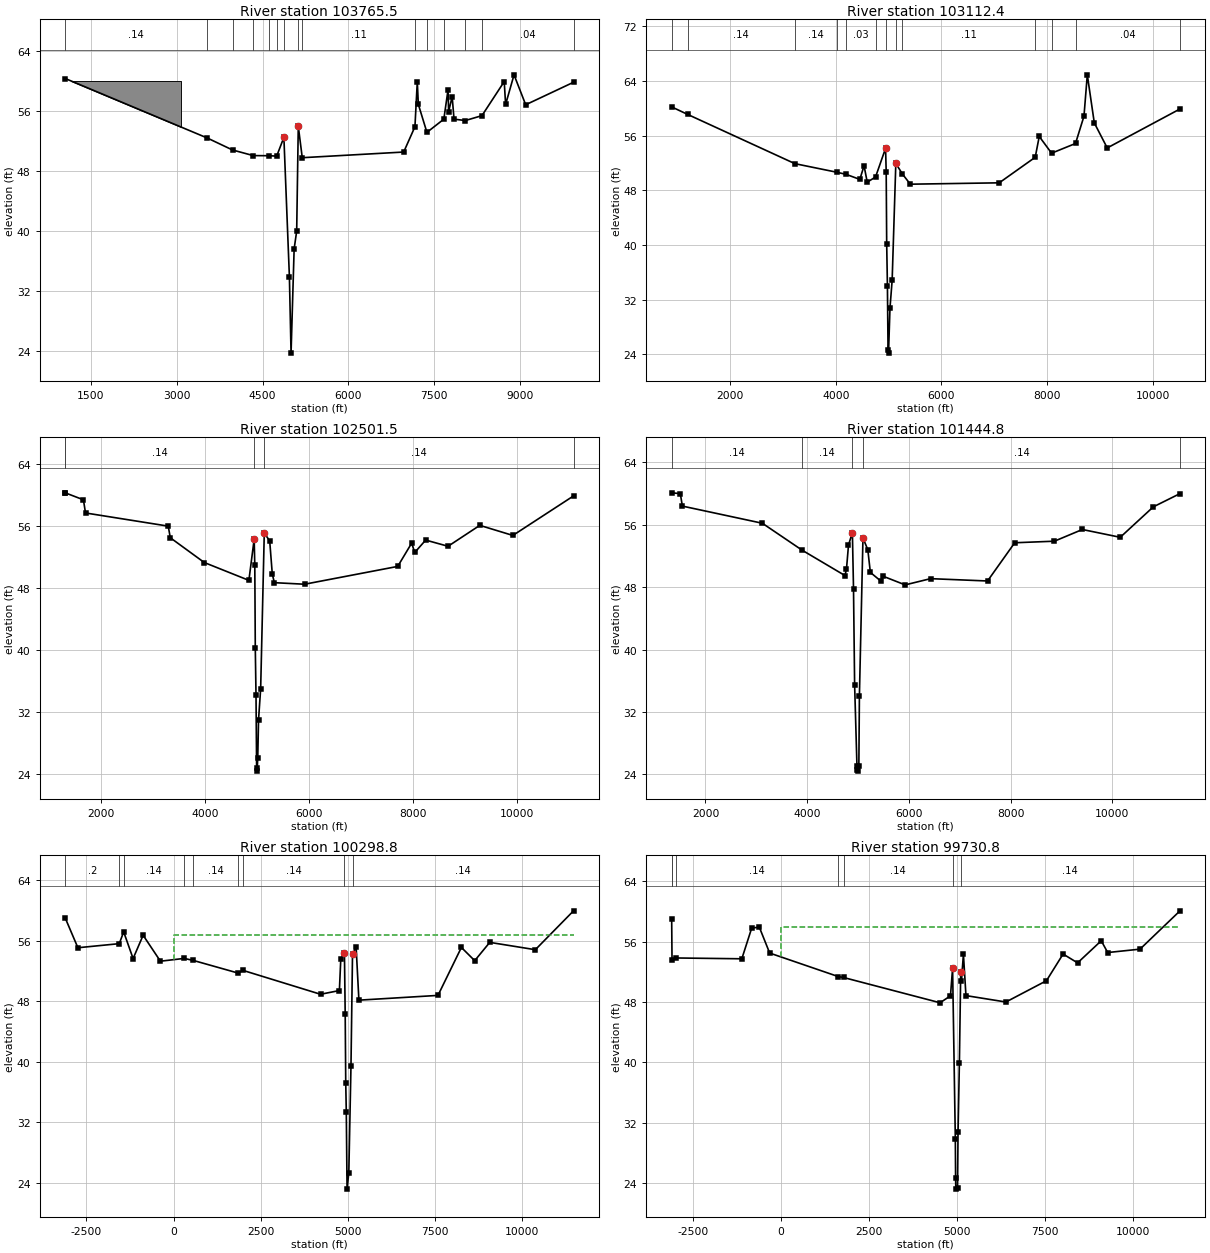
Type RM Length L Ch R = 1 ,103765.5,793.4,653.1,350
BEGIN DESCRIPTION:
Cross Section 103765.5
END DESCRIPTION:
XS GIS Cut Line= 6
      3152372.05     13904426.32      3155160.67     13901166.89
      3155314.59     13900338.45      3154907.16     13899215.76
      3154291.49     13898690.63      3152653.48     13898084.28
#Sta/Elev= 30
  1048.9    60.3  3532.7  52.372  3974.6  50.776  4337.6  50.025  4606.6  50.011
  4747.6  49.959  4873.2   52.46  4969.7   33.87  4998.6    23.7  5052.5   37.59
  5097.1   39.96  5124.9   53.94  5194.6  49.745  6968.6    50.5  7165.1  53.874
 7206.36   59.88 7224.47   56.86  7374.6   53.12  7670.4   54.88  7743.7   58.78
 7754.56   55.89 7816.15   57.88 7848.75   54.88    8047    54.7    8337   55.35
 8726.61   59.89 8750.76   56.84 8898.07   60.79  9102.1    56.8  9938.7    59.8
#Mann= 15 ,-1 , 0
  1048.9     .14       0  3532.7     .03       0  3974.6     .04       0
  4337.6    .045       0  4606.6     .03       0  4747.6    .045       0
  4873.2    .035       0  5124.9    .045       0  5194.6     .11       0
  7165.1     .04       0  7374.6     .06       0  7670.4     .04       0
    8047     .06       0    8337     .04       0  9938.7      .2       0
#Block Obstruct= 2 , 0
       0  3068.6      60               0
Bank Sta=4873.2,5124.9
XS Rating Curve= 0 ,0
Exp/Cntr=0.3,0.1

Type RM Length L Ch R = 1 ,103112.4,1058.2,610.9,229.6
BEGIN DESCRIPTION:
Cross Section 103112.4-Interpolated
END DESCRIPTION:
XS GIS Cut Line= 6
      3152946.02      13905126.3      3155569.05     13901662.64
      3155616.76     13900741.02      3155287.04     13899389.16
      3154370.91      13898659.7      3152697.23     13898062.74
#Sta/Elev= 30
   895.8    60.2  1198.6    59.1    3228    51.9  4017.7  50.652  4196.7  50.338
  4455.8    49.6  4535.8    51.6  4595.8    49.2  4752.7  49.945  4942.8   54.15
  4954.6   50.75  4964.1   40.15  4977.9   34.01  4989.6   24.64  4998.7    24.2
  5026.6   30.84  5067.3   34.84  5136.8   51.93  5261.7  50.389  5410.6    48.9
  7093.4    49.1  7774.2  52.834 7850.44   55.88    8084  53.433  8536.6   54.85
 8696.64   58.84 8759.61   64.89 8892.26   57.86  9136.7    54.2 10513.6    59.9
#Mann= 13 ,-1 , 0
   895.8     .14       0  1198.6     .14       0    3228     .14       0
  4017.7    .045       0  4196.7     .03       0  4752.7    .045       0
  4942.8    .035       0  5136.8    .045       0  5261.7     .11       0
  7774.2     .04       0    8084     .06       0  8536.6     .04       0
 10513.6      .2       0
Bank Sta=4942.8,5136.8
XS Rating Curve= 0 ,0
Exp/Cntr=0.3,0.1

Type RM Length L Ch R = 1 ,102501.5,1124.3,1056.7,500.8
BEGIN DESCRIPTION:
Cross Section 102501.5
END DESCRIPTION:
XS GIS Cut Line= 6
      3155543.21     13905825.31      3155930.26     13903828.76
      3156029.85     13901782.56      3155613.37     13899360.62
      3154382.03     13898622.72      3152701.68     13898046.72
#Sta/Elev= 30
  1310.5    60.3  1310.6    60.3  1660.6    59.4  1700.6    57.7  3290.6      56
  3330.6    54.5  3984.3    51.3    4841      49  4942.8   54.32  4954.6   50.92
  4964.1   40.32  4977.9   34.18  4989.6   24.81  4998.7   24.37  5011.4   26.05
  5026.6   31.01  5067.3   35.01  5136.8    55.1    5241    54.1    5291    49.8
    5331    48.7  5911.8    48.5  7701.8    50.8  7969.3    53.8  8029.3    52.6
  8239.3    54.2  8669.3    53.4  9279.3    56.1  9914.8    54.8 11081.1    59.9
#Mann= 5 , 1 , 0
  1310.5      .2       0  1310.6     .14       0  4942.8    .035       0
  5136.8     .14       0 11081.1      .2       0
Bank Sta=4942.8,5136.8
XS Rating Curve= 0 ,0
Exp/Cntr=0.3,0.1

Type RM Length L Ch R = 1 ,101444.8,3002,1146,594.4
BEGIN DESCRIPTION:
Cross Section 101444.8
END DESCRIPTION:
XS GIS Cut Line= 6
      3156989.57     13905730.09      3156889.98     13904571.18
      3156935.25      13901773.5      3155740.12     13899369.68
      3154436.35     13898559.34      3152709.59     13898033.08
#Sta/Elev= 30
  1335.9    60.1  1505.9      60  1545.9    58.4  3119.1    56.2  3900.7   52.75
    4743    49.5    4773    50.3    4813    53.4  4889.5   55.01  4911.6    47.8
  4933.4    35.5  4981.9   24.53  4983.4   25.11  4996.8   24.43  5016.7   25.12
  5027.5   34.09  5097.6   54.32    5193    52.8    5243    49.9  5447.1    48.8
  5497.1    49.4  5927.1    48.3  6427.1    49.1  7547.1    48.8  8081.6    53.7
  8861.6    53.9  9411.6    55.4 10156.7    54.4 10806.7    58.3 11331.8      60
#Mann= 5 , 1 , 0
  1335.9     .14       0  3900.7     .14       0  4889.5    .035       0
  5097.6     .14       0 11331.8      .2       0
Bank Sta=4889.5,5097.6
XS Rating Curve= 0 ,0
Exp/Cntr=0.3,0.1

Type RM Length L Ch R = 1 ,100298.8,710.8,568,334.3
BEGIN DESCRIPTION:
Cross Section 100298.8
END DESCRIPTION:
XS GIS Cut Line= 6
      3165819.04     13903257.22      3162863.18     13903018.59
      3158275.23     13901692.02      3157605.24     13901375.13
      3155658.64     13899116.16      3152763.01     13898025.58
#Sta/Elev= 30
 -3109.3      59 -2745.3   55.06 -1557.7    55.6 -1431.6   57.16 -1161.3   53.63
  -873.3   56.71  -377.3   53.28   306.1   53.65   560.3   53.39  1846.2   51.72
  1996.8   52.06  4217.4   48.91  4758.4    49.4  4798.4   53.54  4903.2   54.42
  4925.1   46.34  4940.8   37.19  4956.7   33.34  4978.9   23.15  5029.1   25.34
  5091.3   39.48    5135   54.17  5238.4   55.18  5318.4   48.13  7587.6   48.76
  8259.6    55.1  8641.6   53.35  9073.6   55.77 10381.5    54.8 11477.5   59.94
#Mann= 9 , 1 , 0
 -3109.3      .2       0 -1557.7     .07       0 -1431.6     .14       0
   306.1     .07       0   560.3     .14       0  1846.2     .07       0
  1996.8     .14       0  4903.2    .035       0    5135     .14       0
#XS Ineff= 2 , 0
       0  -873.3   56.71               0
Permanent Ineff=
       F       F
Bank Sta=4903.2,5135
XS Rating Curve= 0 ,0
Exp/Cntr=0.3,0.1

Type RM Length L Ch R = 1 ,99730.8 ,1363.2,719.4,452.1
BEGIN DESCRIPTION:
Cross Section 99730.8
END DESCRIPTION:
XS GIS Cut Line= 6
      3166070.35     13902305.26      3163185.92     13902273.58
      3157763.14     13900950.53      3155516.59     13898865.87
      3154645.64     13898445.78      3152752.83     13898002.41
#Sta/Elev= 30
 -3100.8      59 -3090.8   53.54   -2985   53.85 -1106.8   53.74  -826.8    57.8
  -610.8   57.95  -314.8    54.5  1636.7   51.38  1784.5   51.26  4528.5   47.91
  4824.5   48.83  4884.7   52.47  4962.7   29.79  4970.3   24.62  4976.9    23.2
  5025.6    23.3  5039.7   30.78    5078   39.97  5115.9   51.96  5136.5   50.81
  5192.5   54.33  5264.5   48.86  6400.4   48.01  7552.4   50.83    8026   54.37
  8438.2    53.2  9110.2   56.13  9294.2   54.57 10213.2   55.02 11349.2    60.1
#Mann= 7 , 1 , 0
 -3100.8      .2       0 -3090.8    .035       0   -2985     .14       0
  1636.7     .07       0  1784.5     .14       0  4884.7    .035       0
  5115.9     .14       0
#XS Ineff= 2 , 0
       0  -610.8   57.95               0
Permanent Ineff=
       F       F
Bank Sta=4884.7,5115.9
XS Rating Curve= 0 ,0
Exp/Cntr=0.3,0.1