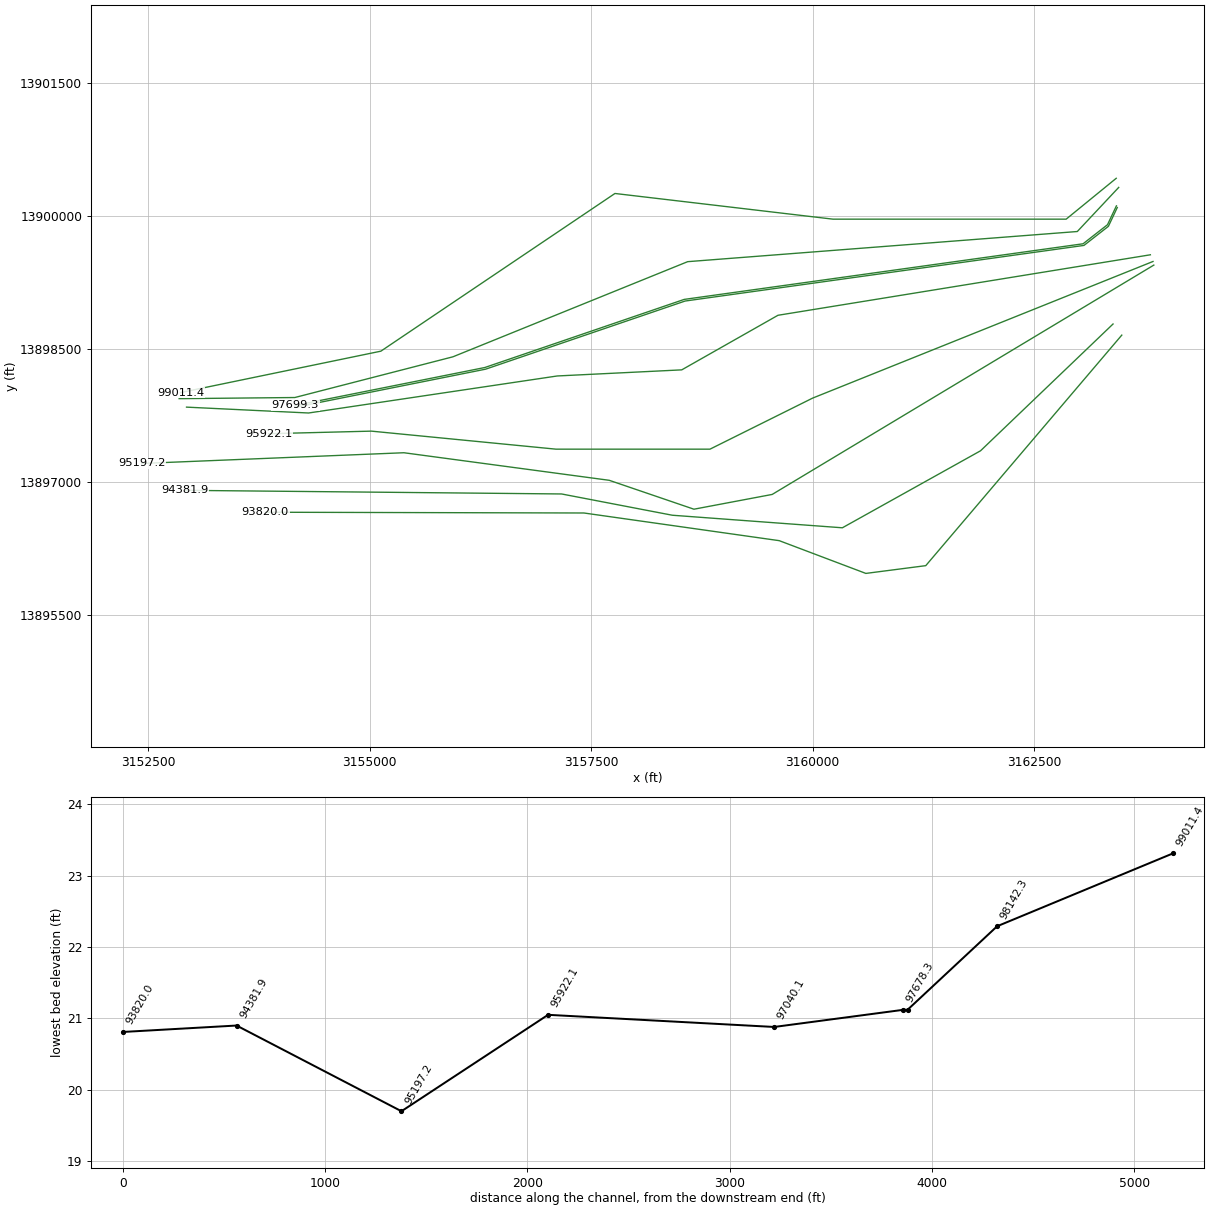
HEC-RAS study P100-00-00.prj: P100-00-00

--- P100-00-00.g01 (geometry) --- (continued)

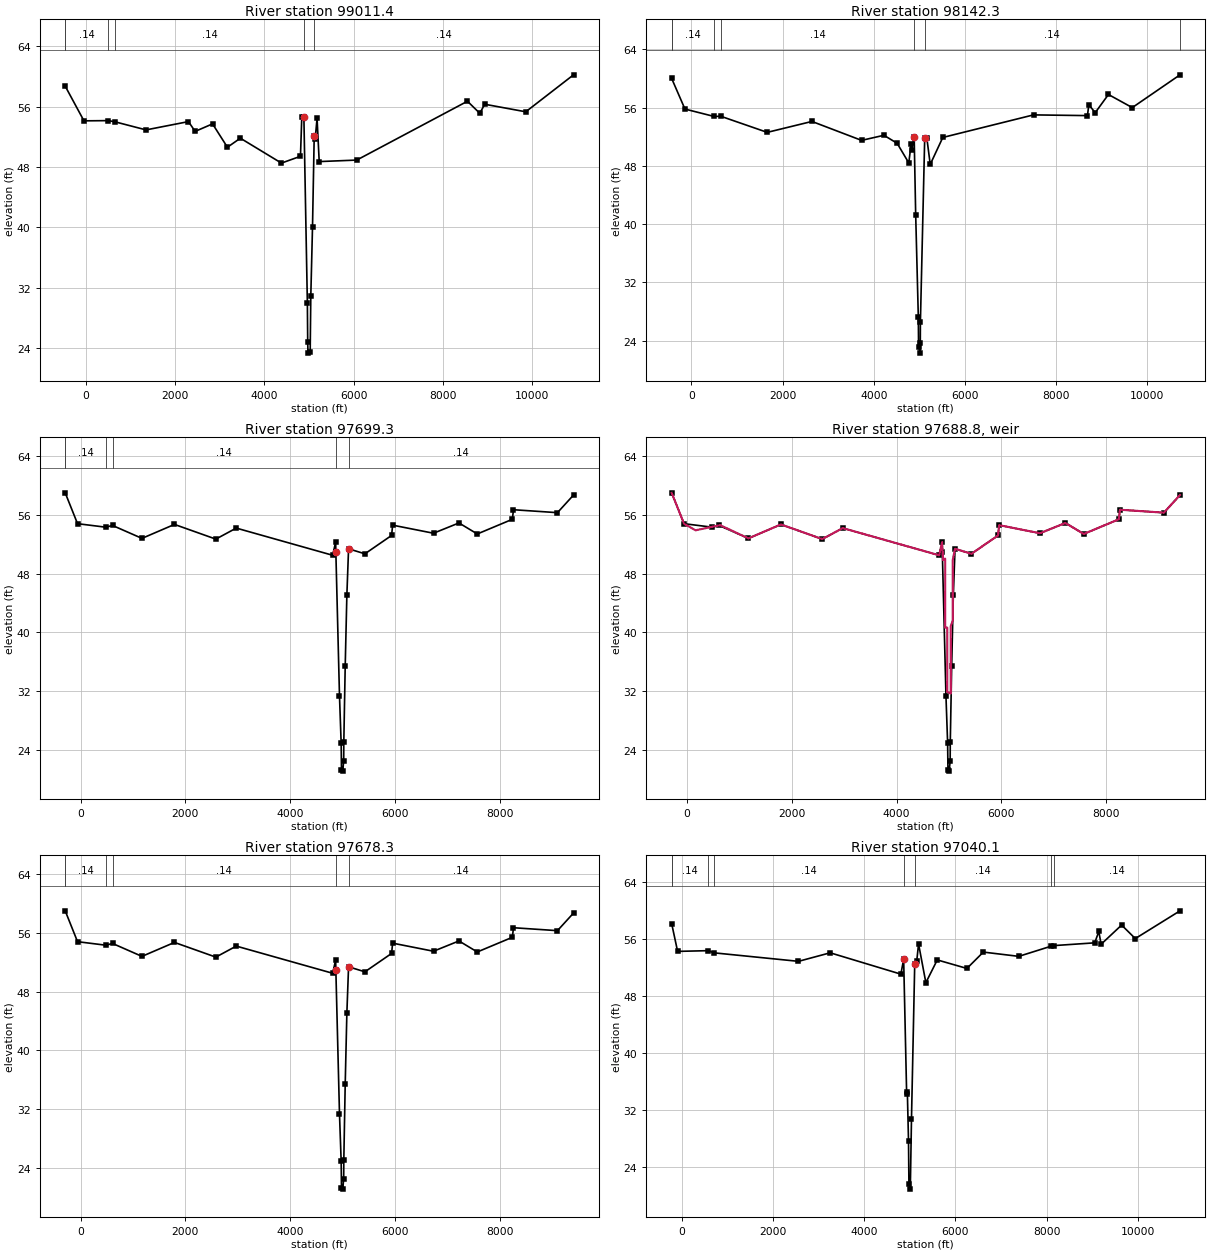
Type RM Length L Ch R = 1 ,99011.4 ,554.8,869.1,878.4
BEGIN DESCRIPTION:
Cross Section 99011.4
END DESCRIPTION:
XS GIS Cut Line= 6
       3163429.3     13900423.73      3162863.81     13899962.71
      3160230.89     13899962.71      3157768.21     13900252.44
      3155124.45     13898473.33      3152862.24     13898006.04
#Sta/Elev= 30
  -462.6    58.7   -42.6    54.1   505.3   54.13   653.3   53.97  1348.4    52.9
  2298.4      54  2448.4    52.7  2838.4    53.7  3171.4    50.6  3461.4    51.8
  4381.4    48.5  4807.9    49.4  4837.3   54.55  4884.7   54.58  4962.7    29.9
  4970.3   24.73  4976.9   23.31  5025.6   23.41  5039.7   30.89    5078   40.08
  5115.9   52.07  5136.8   51.65  5179.8   54.43  5227.9    48.7  6069.1    48.9
  8549.1    56.7  8825.7    55.1  8935.7    56.3  9855.7    55.3 10925.7    60.2
#Mann= 6 , 1 , 0
  -462.6      .2       0  -462.6     .14       0   505.3     .07       0
   653.3     .14       0  4884.7    .035       0  5115.9     .14       0
Bank Sta=4884.7,5115.9
XS Rating Curve= 0 ,0
Exp/Cntr=0.3,0.1

Type RM Length L Ch R = 1 ,98142.3 ,361.6,443,472.2
BEGIN DESCRIPTION:
Cross Section 98142.3
END DESCRIPTION:
XS GIS Cut Line= 6
      3163457.34     13900320.91      3162989.83     13899823.36
      3158589.53     13899483.17      3155937.99     13898409.62
      3154153.05     13897950.45      3152846.68     13897937.51
#Sta/Elev= 30
  -431.8      60  -140.7    55.8   501.9   54.78     641   54.82  1664.2    52.6
  2644.2    54.1  3732.7    51.5  4222.7    52.2  4512.7    51.1  4768.2    48.4
  4818.2      51  4827.4    50.2  4886.1    51.9  4919.5   41.19  4977.1   27.21
  4982.4   23.16  5017.1   22.29  5020.2    23.7  5022.4    26.5    5117   51.84
  5164.2    51.8  5238.2    48.2  5513.7    51.9  7503.7      55  8685.8    54.9
  8715.8    56.4  8855.8    55.3  9145.8    57.8  9668.8      56 10715.3    60.5
#Mann= 7 , 1 , 0
  -431.8      .2       0  -431.8     .14       0   501.9     .07       0
     641     .14       0  4886.1    .035       0    5117     .14       0
 10715.3      .2       0
Bank Sta=4886.1,5117
XS Rating Curve= 0 ,0
Exp/Cntr=0.7,0.5

Type RM Length L Ch R = 1 ,97699.3 ,21,21,21
BEGIN DESCRIPTION:
Upstream Section of Bridge/Culvert/Weir
END DESCRIPTION:
XS GIS Cut Line= 6
      3163431.34     13900112.85      3163330.86     13899900.21
      3163054.85     13899684.96      3158550.66      13899057.5
      3156298.34     13898288.93      3154157.99     13897860.97
#Sta/Elev= 30
  -292.5      59   -57.3    54.8   483.9   54.32   610.3   54.56  1172.7    52.8
  1792.7    54.7  2582.7    52.7  2972.7    54.2  4812.8    50.5  4869.8    52.3
  4873.2      51    4943   31.34  4974.7   24.92    4981   21.31  5004.5   21.12
  5023.1   22.53  5025.4   25.06  5051.9   35.38  5083.6   45.06  5116.1   51.38
  5428.4    50.7  5937.3    53.2  5957.3    54.6  6737.3    53.5  7223.2    54.9
  7573.2    53.4  8243.2    55.4  8263.2    56.7  9103.2    56.3  9410.2    58.7
#Mann= 6 , 1 , 0
  -292.5      .2       0  -292.5     .14       0   483.9     .07       0
   610.3     .14       0  4873.2    .035       0  5116.1     .14       0
#XS Ineff= 2 , 0
       0  4863.2    50.5  5126.1       0   50.24
Permanent Ineff=
       F       F
Bank Sta=4873.2,5116.1
XS Rating Curve= 0 ,0
Exp/Cntr=0.7,0.5

Type RM Length L Ch R = 5 ,97688.8 ,,,
BEGIN DESCRIPTION:
SHEET PILE WEIR
Structure ID:
END DESCRIPTION:
IW Pilot Flow=0
#Inline Weir SE= 30
  -292.5      59   -57.3    54.8   162.7    53.9   632.7    54.6  1172.7    52.8
  1792.7    54.7  2582.7    52.7  2972.7    54.2  4812.8    50.5  4869.8    52.3
  4888.1   49.86    4928   50.04  4928.1   40.65  4967.2   40.66  4967.7    31.9
  5032.9   31.68  5033.6   40.84  5072.3   41.62  5072.6   49.87  5116.1   51.39
  5428.4    50.7  5937.3    53.2  5957.3    54.6  6737.3    53.5  7223.2    54.9
  7573.2    53.4  8243.2    55.4  8263.2    56.7  9103.2    56.3  9410.2    58.7
IW Dist,WD,Coef,Skew,MaxSub,Min_El,Is_Ogee,SpillHt,DesHd
10,1,3,0,0.95,, 0 ,,,1,1,
Inline Weir Flap Gates= 0
IW Outlet Rating Curve= 0 ,False,,

Type RM Length L Ch R = 1 ,97678.3 ,638.2,638.2,638.2
BEGIN DESCRIPTION:
Downstream Section of Bridge/Culvert/Weir
END DESCRIPTION:
XS GIS Cut Line= 6
      3163441.28     13900094.35       3163340.8     13899881.71
      3163064.79     13899666.46       3158560.6       13899039.
      3156308.28     13898270.43      3154167.92     13897842.47
#Sta/Elev= 30
  -292.5      59   -57.3    54.8   483.9   54.32   610.3   54.56  1172.7    52.8
  1792.7    54.7  2582.7    52.7  2972.7    54.2  4812.8    50.5  4869.8    52.3
  4873.2      51    4943   31.34  4974.7   24.92    4981   21.31  5004.5   21.12
  5023.1   22.53  5025.4   25.06  5051.9   35.38  5083.6   45.06  5116.1   51.38
  5428.4    50.7  5937.3    53.2  5957.3    54.6  6737.3    53.5  7223.2    54.9
  7573.2    53.4  8243.2    55.4  8263.2    56.7  9103.2    56.3  9410.2    58.7
#Mann= 6 , 1 , 0
  -292.5      .2       0  -292.5     .14       0   483.9     .07       0
   610.3     .14       0  4873.2    .035       0  5116.1     .14       0
#XS Ineff= 2 , 0
       0 4866.53    50.5 5122.77       0   50.24
Permanent Ineff=
       F       F
Bank Sta=4873.2,5116.1
XS Rating Curve= 0 ,0
Exp/Cntr=0.7,0.5

Type RM Length L Ch R = 1 ,97040.1 ,949,1118,1125.5
BEGIN DESCRIPTION:
Cross Section 97040.1
END DESCRIPTION:
XS GIS Cut Line= 6
        3163815.     13899560.77       3159609.2     13898878.24
      3158522.54     13898262.47      3157117.12     13898193.65
      3154308.26     13897775.83      3152929.86       13897842.
#Sta/Elev= 30
  -219.6    58.2   -89.6    54.3   586.2    54.4   700.8    54.1  2560.4    52.9
  3255.4    54.1  4805.3    51.1  4866.5   53.18  4931.9   34.31  4947.3   34.57
    4973   27.64  4981.8   21.66  5012.3   20.88  5038.2    30.8  5109.1   52.51
  5152.7    52.9  5193.3   55.35  5353.3    49.9  5603.3    53.1  6253.3    51.9
  6613.3    54.2  7390.4    53.6  8090.1   55.01  8154.4   55.11  9055.4    55.5
  9145.4    57.1  9195.4    55.3  9645.1      58  9945.1    56.1 10925.1      60
#Mann= 8 , 1 , 0
  -219.6      .2       0  -219.6     .14       0   586.2     .07       0
   700.8     .14       0  4866.5    .035       0  5109.1     .14       0
  8090.1      .1       0  8154.4     .14       0
Bank Sta=4866.5,5109.1
XS Rating Curve= 0 ,0
Exp/Cntr=0.3,0.1

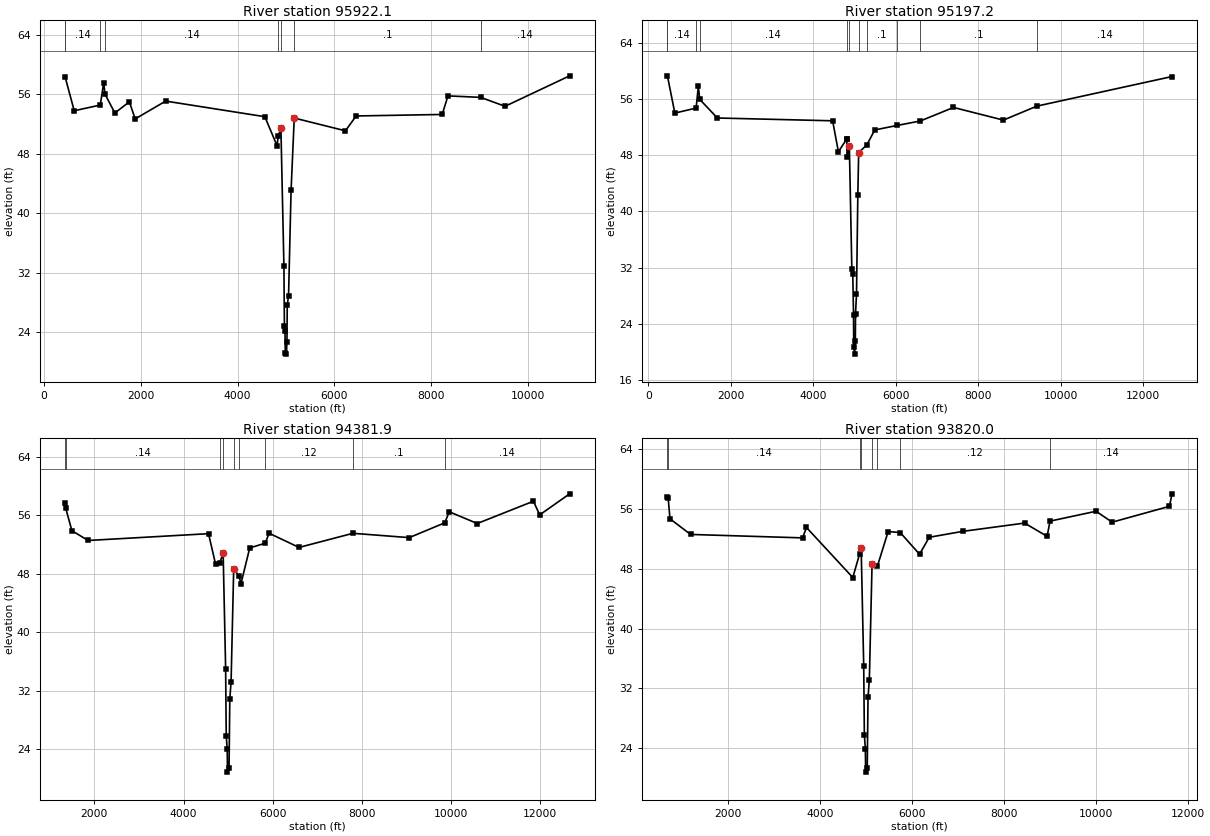
Type RM Length L Ch R = 1 ,95922.1 ,694.1,724.9,734.6
BEGIN DESCRIPTION:
Cross Section 95922.1
END DESCRIPTION:
XS GIS Cut Line= 6
      3163844.69     13899485.35       3160000.4     13897943.71
      3158841.29     13897367.78      3157102.63     13897367.78
      3155017.77     13897571.19      3153858.08     13897542.05
#Sta/Elev= 30
   432.9    58.4   622.9    53.8  1161.8   54.57  1232.9    57.6  1257.9   56.05
  1462.9    53.5  1762.9      55  1882.9    52.7  2512.9    55.1  4562.9      53
  4814.8    49.1  4840.1   50.36  4894.9   51.46  4957.1   32.93  4967.1   24.84
  4979.2   24.14  4985.9   21.16  5008.1   21.05  5019.8   22.67  5025.8   27.66
  5052.9   28.91  5105.2   43.09  5170.5   52.82  6229.1    51.1  6449.1    53.1
  8227.8    53.3  8347.8    55.8  9022.8    55.6  9527.8    54.4 10862.6    58.5
#Mann= 8 , 1 , 0
   432.9      .2       0   432.9     .14       0  1161.8     .07       0
  1257.9     .14       0  4840.1     .14       0  4894.9    .035       0
  5170.5      .1       0  9022.8     .14       0
Bank Sta=4894.9,5170.5
XS Rating Curve= 0 ,0
Exp/Cntr=0.3,0.1

Type RM Length L Ch R = 1 ,95197.2 ,921.4,815.3,259.4
BEGIN DESCRIPTION:
Cross Section 95197.2
END DESCRIPTION:
XS GIS Cut Line= 6
       3163853.8     13899444.36        3159544.     13896857.05
      3158660.18     13896690.43      3157703.92     13897016.43
      3155384.57     13897327.42      3152427.05     13897206.52
#Sta/Elev= 30
   461.2    59.3   641.2      54  1157.6   54.71  1211.2    57.8  1245.1   55.95
  1672.5    53.3  4468.2    52.9  4608.2    48.5  4805.6   50.27  4813.6    50.3
  4816.2   47.72  4873.8   49.32  4934.4   31.81  4956.7   31.16  4975.4   25.21
  4980.2   20.76  5001.3    19.7  5019.2   21.51  5023.4   25.46  5047.3   28.19
  5079.4   42.34    5100   48.37  5299.6   49.48    5490    51.6  6033.9   52.24
  6597.7   52.88  7399.9    54.8  8609.9      53  9422.6   54.99   12700    59.2
#Mann= 11 , 1 , 0
   461.2      .2       0   461.2     .14       0  1157.6     .07       0
  1245.1     .14       0  4805.6     .07       0  4873.8    .035       0
    5100     .14       0  5299.6      .1       0  6033.9     .12       0
  6597.7      .1       0  9422.6     .14       0
Bank Sta=4873.8,5100
XS Rating Curve= 0 ,0
Exp/Cntr=0.3,0.1

Type RM Length L Ch R = 1 ,94381.9 ,1076.2,561.9,224.8
BEGIN DESCRIPTION:
Cross Section 94381.9-Interpolated
END DESCRIPTION:
XS GIS Cut Line= 6
      3163393.33     13898779.88       3161896.8     13897349.37
      3160336.55     13896480.73      3158415.76     13896622.43
      3157165.28     13896862.37      3152909.45     13896903.24
#Sta/Elev= 30
  1340.3   57.75  1356.5   56.98  1494.3   53.92  1858.3   52.58  4558.6   53.51
  4715.6   49.38  4810.5   49.48  4886.7   50.88  4942.4   35.07  4955.9    25.9
  4978.3   24.01  4984.1    20.9  5019.2   21.49  5035.9   30.89  5064.8   33.28
  5123.4   48.67  5239.8   47.76  5286.8   46.68  5482.8   51.56  5831.7   52.21
  5916.8   53.57  6588.8   51.63  7797.8   53.56  9060.1   52.97  9859.3      55
  9956.1   56.51 10586.1    54.9 11846.1   57.95 11986.1   56.08 12658.1   58.96
#Mann= 9 , 1 , 0
  1340.3     .07       0  1356.5     .14       0  4810.5     .06       0
  4886.7    .035       0  5123.4     .06       0  5239.8     .14       0
  5831.7     .12       0  7797.8      .1       0  9859.3     .14       0
Bank Sta=4886.7,5123.4
XS Rating Curve= 0 ,0
Exp/Cntr=0.3,0.1

Type RM Length L Ch R = 1 ,93820.0 ,1137.8,925,684.1
BEGIN DESCRIPTION:
Cross Section 93820.0
END DESCRIPTION:
XS GIS Cut Line= 6
      3163492.08     13898654.41      3161278.36     13896053.59
      3160601.69     13895965.99      3159623.69     13896335.45
      3157417.68     13896647.68      3153819.74     13896656.24
#Sta/Elev= 30
   673.5   57.65   689.4    57.5   729.5   54.68  1177.5   52.59  3613.5   52.13
  3697.5   53.52  4704.8   46.83  4853.8      50  4886.7   50.79  4942.4   34.98
  4955.9   25.81  4978.3   23.92  4984.1   20.81  5019.2    21.4  5035.9    30.8
  5064.8   33.19  5123.4   48.58  5238.7   48.33    5474   52.98  5736.5   52.84
  6156.7   49.94  6366.7   52.21  7094.7      53  8440.7   54.11  8930.7   52.33
  8993.4   54.37  9994.7   55.69 10344.7   54.23 11590.7   56.35 11646.7   58.02
#Mann= 8 , 1 , 0
   673.5     .07       0   689.4     .14       0  4853.8     .06       0
  4886.7    .035       0  5123.4     .06       0  5238.7     .14       0
  5736.5     .12       0  8993.4     .14       0
Bank Sta=4886.7,5123.4
XS Rating Curve= 0 ,0
Exp/Cntr=0.3,0.1