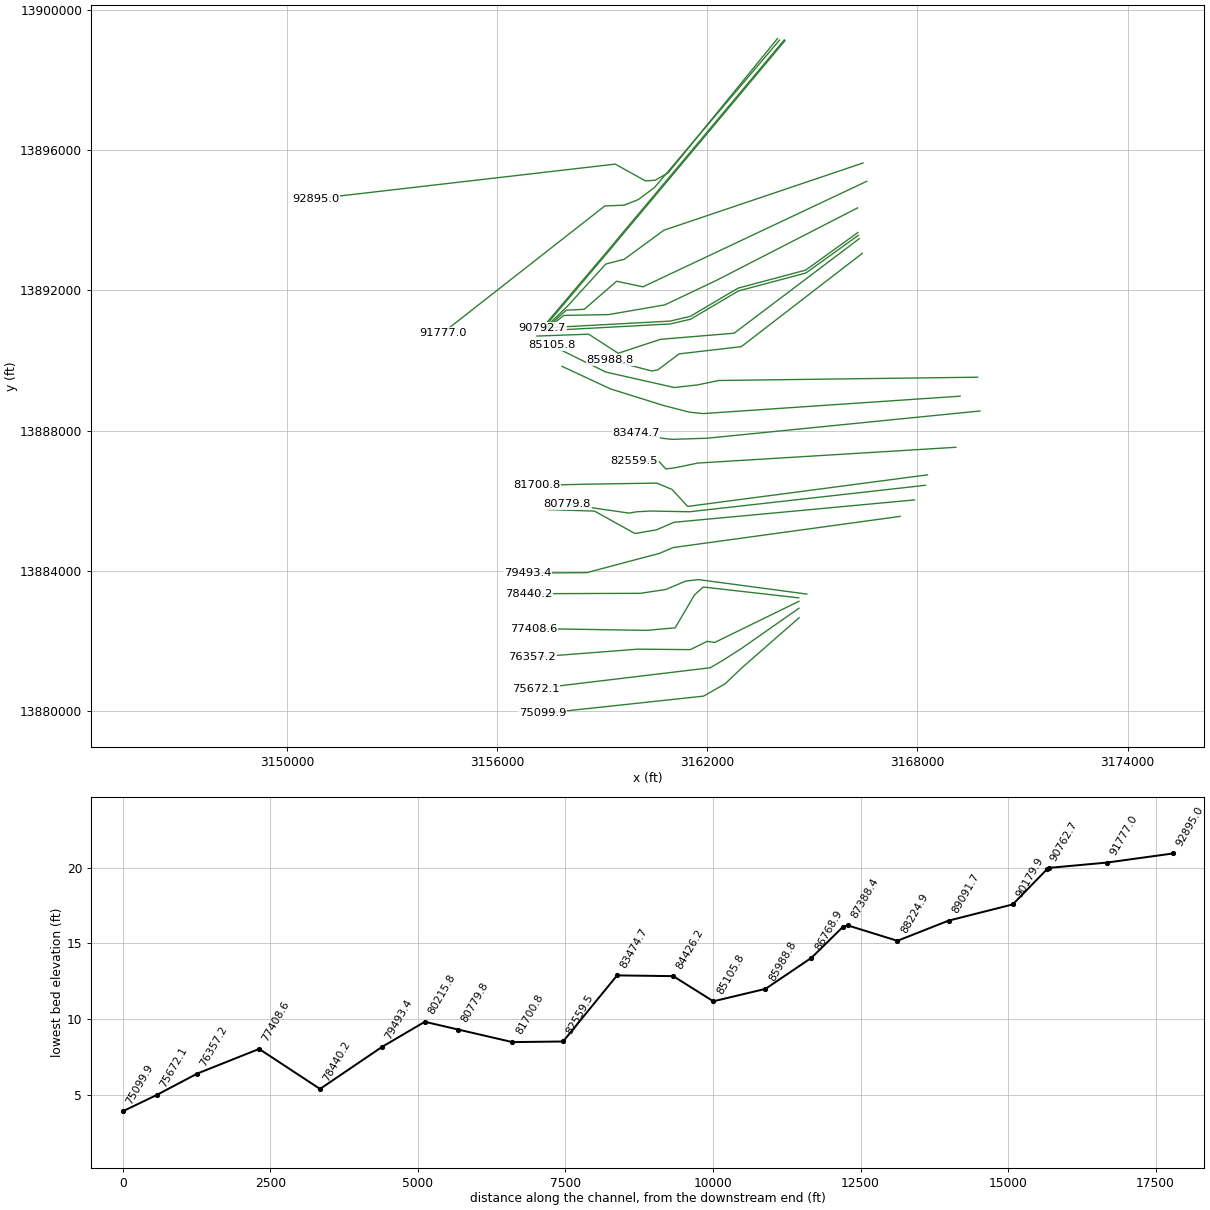
HEC-RAS study P100-00-00.prj: P100-00-00

--- P100-00-00.g01 (geometry) --- (continued)

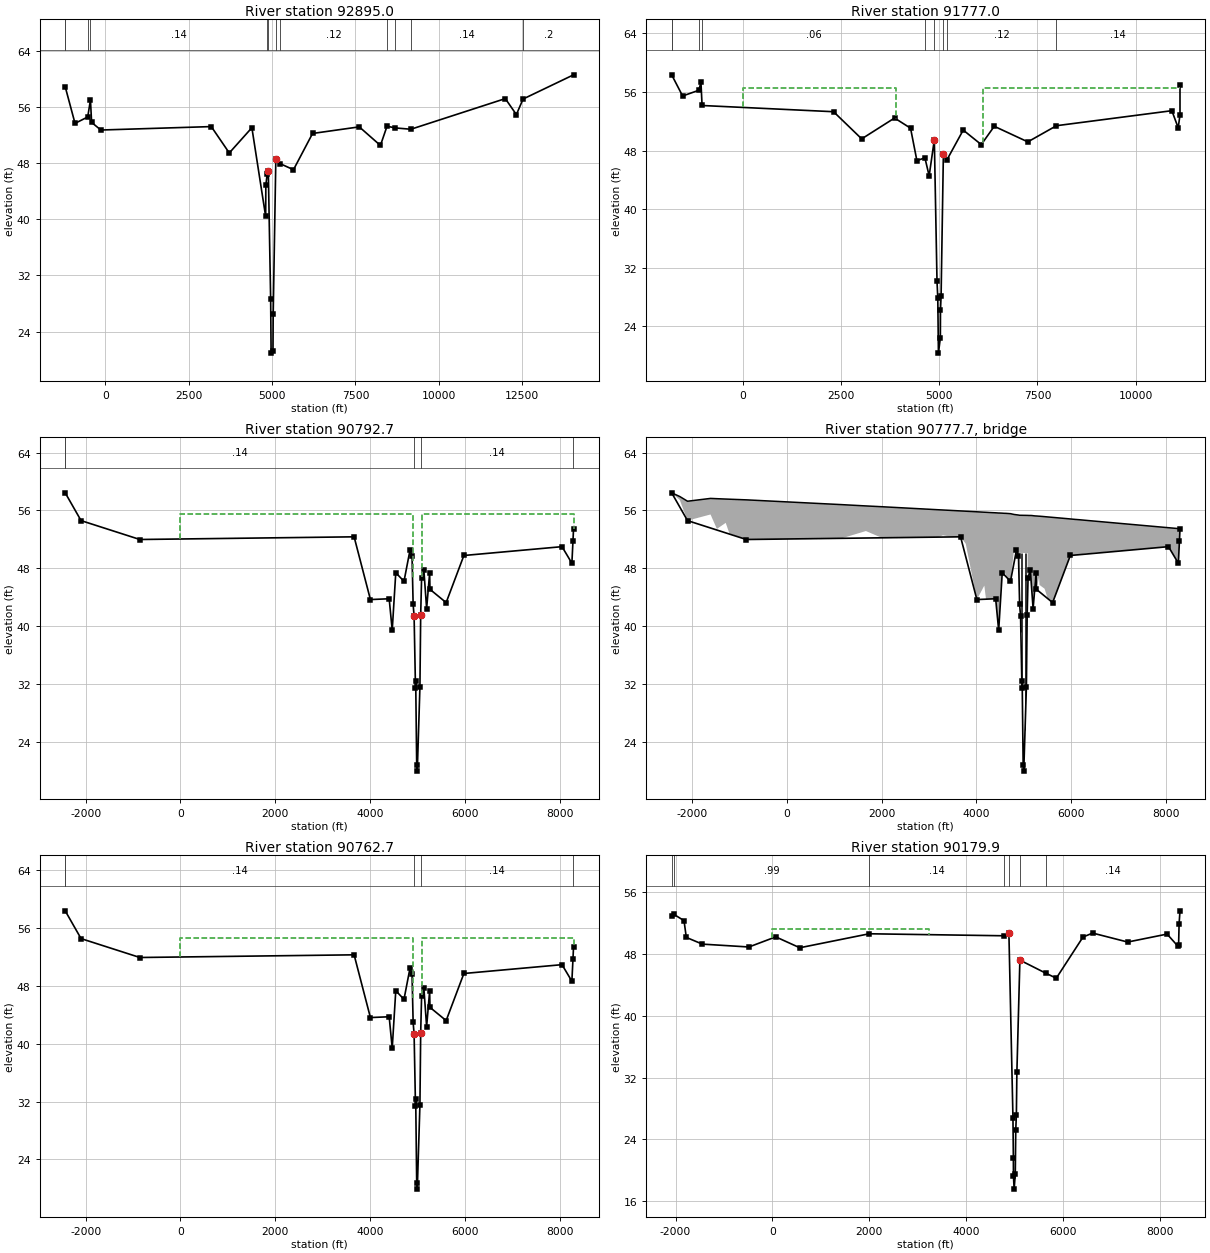
Type RM Length L Ch R = 1 ,92895.0 ,363.5,1118,1749
BEGIN DESCRIPTION:
Cross Section 92895.0
END DESCRIPTION:
XS GIS Cut Line= 6
      3164002.44     13899175.24      3160880.79      13895346.8
      3160511.23     13895136.69      3160232.22     13895118.39
      3159370.13     13895596.52      3150824.96      13894610.9
#Sta/Elev= 30
 -1198.1   58.91  -904.2   53.69  -523.7    54.6  -441.3   57.03  -407.3   53.83
  -130.1   52.74  3179.5   53.23  3718.7   49.47    4396   53.07    4809   40.42
  4814.4   44.85  4852.4    46.4  4888.2   46.91  4958.5   28.65  4972.1   20.93
  5028.4   21.19  5034.7   26.56  5113.6   48.54  5240.8   47.95  5642.6   47.08
  6214.5   52.25  7614.3   53.19  8248.1   50.54  8445.7   53.28  8692.9   53.04
    9160   52.85 11990.4   57.22 12322.4   54.94 12522.9   57.16 14035.1   60.61
#Mann= 12 , 1 , 0
 -1198.1      .2       0 -1198.1     .14       0  -523.7     .07       0
  -441.3     .14       0  4852.4     .06       0  4888.2    .035       0
  5113.6     .06       0  5240.8     .12       0  8445.7     .14       0
  8692.9     .12       0    9160     .14       0 12522.9      .2       0
Bank Sta=4888.2,5113.6
XS Rating Curve= 0 ,0
Exp/Cntr=0.3,0.1

Type RM Length L Ch R = 1 ,91777.0 ,166.1,984.3,1729
BEGIN DESCRIPTION:
Cross Section 91777.0
END DESCRIPTION:
XS GIS Cut Line= 6
      3164061.34     13899131.07      3160494.91     13894933.58
      3160029.38     13894585.92      3159623.93     13894426.65
        3159073.     13894404.81      3154449.19     13890789.31
#Sta/Elev= 30
 -1818.4   58.35 -1539.7   55.46 -1127.3   56.24 -1072.8   57.32 -1043.9   54.16
  2305.6   53.31  3022.1    49.6  3859.4   52.45  4266.7   51.06  4428.1   46.63
  4632.2   47.01  4740.7   44.55  4872.3   49.49  4940.5   30.16  4960.5   27.84
  4976.8   20.33  5025.9   22.42    5029   26.27  5044.3   28.07    5103   47.56
  5185.5   46.66  5608.2    50.8  6068.1   48.82    6399   51.32  7253.8   49.19
  7983.9    51.4   10923   53.45 11084.5   51.11 11130.3   52.88 11130.4      57
#Mann= 9 , 1 , 0
 -1818.4      .2       0 -1818.4     .14       0 -1127.3     .07       0
 -1043.9     .06       0  4632.2     .06       0  4872.3    .035       0
    5103     .06       0  5185.5     .12       0  7983.9     .14       0
#XS Ineff= 2 , 0
       0    3900    56.6    6100       0    56.6
Permanent Ineff=
       F       F
Bank Sta=4872.3,5103
XS Rating Curve= 0 ,0
Exp/Cntr=0.5,0.3

Type RM Length L Ch R = 1 ,90792.7 ,30,30,30
BEGIN DESCRIPTION:
Upstream Section of Bridge/Culvert/Weir
END DESCRIPTION:
XS GIS Cut Line= 6
      3164197.21     13899137.11      3160200.99     13894372.93
      3159609.88     13893672.04      3159196.11     13893173.82
      3157941.25     13891697.79      3157288.61     13890929.83
#Sta/Elev= 30
 -2432.1   58.44 -2097.5    54.6    -856   51.99  3665.1   52.36    4009   43.69
  4405.1    43.8  4469.3   39.45  4544.3    47.4  4717.9   46.21    4844    50.5
  4887.4   49.76  4910.9   43.01  4931.1   41.41  4960.5   31.44  4964.9   32.48
    4986   20.81  4998.3   19.98  5054.1    31.6  5070.3   41.61  5089.4   46.71
  5137.5   47.74  5195.5   42.44  5259.1   47.36  5266.3    45.1  5607.5   43.27
  5981.7   49.78  8052.7      51    8261   48.71  8283.7   51.72  8295.9   53.48
#Mann= 5 , 1 , 0
 -2432.1      .2       0 -2432.1     .14       0  4931.1    .035       0
  5070.3     .14       0  8283.7     .12       0
#XS Ineff= 2 , 0
       0    4899    55.5    5091       0    55.5
Permanent Ineff=
       F       F
Bank Sta=4931.1,5070.3
XS Rating Curve= 0 ,0
Exp/Cntr=0.5,0.3

Type RM Length L Ch R = 3 ,90777.7 ,,,
BEGIN DESCRIPTION:
UNION PACIFIC RAILROAD
Structure ID: P00-24
END DESCRIPTION:
Bridge Culvert--1,0,-1,-1, 0
Deck Dist Width WeirC Skew NumUp NumDn MinLoCord MaxHiCord MaxSubmerge Is_Ogee
10,10,2.6,0, 60, 60, , , 0.95, 0, 1,1,,
 -2432.1 -2261.2 -2097.5 -1611.8 -1477.9 -1291.8 -1214.6    -856  1155.8  1666.8
  2003.2    3200  3292.3  3494.4  3665.1  3774.6    4009  4166.4  4201.7  4276.6
  4308.7  4405.1  4469.3  4489.1  4512.1  4544.3  4586.1  4597.8  4629.9  4717.9
  4793.2  4887.4 4909.11  4909.2 5080.49  5080.6  5089.4  5105.3  5137.5  5147.3
  5174.3  5195.5  5237.9  5259.1  5266.3  5322.8  5330.8  5438.1  5503.7  5607.5
  5883.5  5917.8  5981.7  6077.5  6138.9  6178.2  6290.4  8052.7    8261  8295.9
   58.44   57.93   57.28   57.67   57.63   57.58   57.56   57.47   56.81   56.63
   56.52    56.1   56.07      56   55.94    55.9   55.82   55.76   55.75   55.72
   55.71   55.68   55.65   55.65   55.64   55.63   55.61   55.61    55.6   55.56
   55.45   55.37   55.34   55.34   55.32   55.32   55.32   55.31   55.31   55.31
    55.3   55.28   55.25   55.24   55.24   55.21   55.21   55.15   55.11   55.05
   54.89   54.87   54.83   54.77   54.74   54.72   54.65   53.62    53.5   53.48
   58.44   57.46    54.6   55.45   53.45   54.29   52.85   51.99   52.01   53.16
   51.32   50.76   52.57   51.44   52.36   51.39   43.69   45.62   43.45   41.84
   43.76    43.8   39.45   40.87   45.32    47.4   46.56   47.52   45.67   46.21
   50.51   49.76   43.56   50.14   50.12   45.07   46.71   45.96   47.74   46.26
    45.7   42.44   47.13   47.36    45.1   46.81   45.71   45.19   43.29   43.27
   46.16   48.83   49.78    47.9   49.68   48.73   50.05      51   48.71   53.48
 -2432.1 -2261.2 -2097.5 -1611.8 -1477.9 -1291.8 -1214.6    -856  1155.8  1666.8
  2003.2    3200  3292.3  3494.4  3665.1  3774.6    4009  4166.4  4201.7  4276.6
  4308.7  4405.1  4469.3  4489.1  4512.1  4544.3  4586.1  4597.8  4629.9  4717.9
  4793.2  4887.4 4909.11  4909.2 5080.49  5080.6  5089.4  5105.3  5137.5  5147.3
  5174.3  5195.5  5237.9  5259.1  5266.3  5322.8  5330.8  5438.1  5503.7  5607.5
  5883.5  5917.8  5981.7  6077.5  6138.9  6178.2  6290.4  8052.7    8261  8295.9
   58.44   57.93   57.28   57.67   57.63   57.58   57.56   57.47   56.81   56.63
   56.52    56.1   56.07      56   55.94    55.9   55.82   55.76   55.75   55.72
   55.71   55.68   55.65   55.65   55.64   55.63   55.61   55.61    55.6   55.56
   55.45   55.37   55.34   55.34   55.32   55.32   55.32   55.31   55.31   55.31
    55.3   55.28   55.25   55.24   55.24   55.21   55.21   55.15   55.11   55.05
   54.89   54.87   54.83   54.77   54.74   54.72   54.65   53.62    53.5   53.48
    58.4   57.42   54.56   55.41   53.41   54.25   52.81   51.95   51.97   53.12
   51.28   50.72   52.53    51.4   52.32   51.35   43.65   45.58   43.41    41.8
   43.72   43.76   39.41   40.83   45.28   47.36   46.52   47.48   45.63   46.17
   50.47   49.72   43.52    50.1   50.08   45.03   46.67   45.92    47.7   46.22
   45.66    42.4   47.09   47.32   45.06   46.77   45.67   45.15   43.25   43.23
   46.12   48.79   49.74   47.86   49.64   48.69   50.01   50.96   48.67   53.44
Pier Skew, UpSta & Num, DnSta & Num=  ,4937.4, 2 ,4937.4, 2 , 0 , 0 , 0 ,,
       2       2
   36.82   51.12
       2       2
   36.78   51.08
Pier Skew, UpSta & Num, DnSta & Num=  ,4964.9, 2 ,4964.9, 2 , 0 , 0 , 0 ,,
       2       2
   30.95    51.1
       2       2
   30.91   51.06
Pier Skew, UpSta & Num, DnSta & Num=  ,5025.5, 2 ,5025.5, 2 , 0 , 0 , 0 ,,
       2       2
   24.24   51.12
       2       2
    24.2   51.08
Pier Skew, UpSta & Num, DnSta & Num=  ,5052, 2 ,5052, 2 , 0 , 0 , 0 ,,
       2       2
   31.45   51.13
       2       2
   31.41   51.09
Abutment Skew #Up #Dn= , 2 , 2
    4909  4938.9
   50.14   37.56
    4909  4938.9
    50.1   37.52
Abutment Skew #Up #Dn= , 2 , 2
  5054.1 5080.69
    31.6   50.12
  5054.1 5080.69
   31.56   50.08
BR Coef= 1 , 1 , 0 ,1.25, 0 ,,,0.8,0,2,0,
WSPro=,,,, 1 ,,,, 0 ,,,, 0 ,,,,-1 ,-1 ,-1 , 0 , 0 , 0 , 0 , 0
BR U #Sta/Elev= 30
 -2432.1   58.44 -2097.5    54.6    -856   51.99  3665.1   52.36    4009   43.69
  4405.1    43.8  4469.3   39.45  4544.3    47.4  4717.9   46.21    4844    50.5
  4887.4   49.76  4910.9   43.01  4931.1   41.41  4960.5   31.44  4964.9   32.48
    4986   20.81  4998.3   19.98  5054.1    31.6  5070.3   41.61  5089.4   46.71
  5137.5   47.74  5195.5   42.44  5259.1   47.36  5266.3    45.1  5607.5   43.27
  5981.7   49.78  8052.7      51    8261   48.71  8283.7   51.72  8295.9   53.48
BR U #Mann= 5
 -2432.1      .2 -2432.1     .14  4931.1    .035  5070.3     .14  8283.7     .12
BR U Banks=4931.1,5070.3
BR D #Sta/Elev= 30
 -2432.1    58.4 -2097.5   54.56    -856   51.95  3665.1   52.32    4009   43.65
  4405.1   43.76  4469.3   39.41  4544.3   47.36  4717.9   46.17    4844   50.46
  4887.4   49.72  4910.9   42.97  4931.1   41.37  4960.5    31.4  4964.9   32.44
    4986   20.77  4998.3   19.94  5054.1   31.56  5070.3   41.57  5089.4   46.67
  5137.5    47.7  5195.5    42.4  5259.1   47.32  5266.3   45.06  5607.5   43.23
  5981.7   49.74  8052.7   50.96    8261   48.67  8283.7   51.68  8295.9   53.44
BR D #Mann= 5
 -2432.1      .2 -2432.1     .14  4931.1    .035  5070.3     .14  8283.7     .12
BR D Banks=4931.1,5070.3
BC Design=,, 0 ,, 0 ,,,,,,
BC HTab HWMax=58.44
BC Use User HTab Curves=0
BC User HTab FreeFlow(D)= 0

Type RM Length L Ch R = 1 ,90762.7 ,582.8,582.8,582.8
BEGIN DESCRIPTION:
Downstream Section of Bridge/Culvert/Weir
END DESCRIPTION:
XS GIS Cut Line= 6
      3164217.71     13899115.21      3160221.49     13894351.03
      3159630.38     13893650.14      3159216.61     13893151.92
      3157961.75     13891675.89      3157309.12     13890907.93
#Sta/Elev= 30
 -2432.1   58.36 -2097.5   54.52    -856   51.91  3665.1   52.28    4009   43.61
  4405.1   43.72  4469.3   39.37  4544.3   47.32  4717.9   46.13    4844   50.42
  4887.4   49.68  4910.9   42.93  4931.1   41.33  4960.5   31.36  4964.9    32.4
    4986   20.73  4998.3    19.9  5054.1   31.52  5070.3   41.53  5089.4   46.63
  5137.5   47.66  5195.5   42.36  5259.1   47.28  5266.3   45.02  5607.5   43.19
  5981.7    49.7  8052.7   50.92    8261   48.63  8283.7   51.64  8295.9    53.4
#Mann= 5 , 1 , 0
 -2432.1      .2       0 -2432.1     .14       0  4931.1    .035       0
  5070.3     .14       0  8283.7     .12       0
#XS Ineff= 2 , 0
       0    4899    54.6    5091       0    54.6
Permanent Ineff=
       F       F
Bank Sta=4931.1,5070.3
XS Rating Curve= 0 ,0
Exp/Cntr=0.5,0.3

Type RM Length L Ch R = 1 ,90179.9 ,1174.3,1088.2,599.3
BEGIN DESCRIPTION:
Cross Section 90179.9
END DESCRIPTION:
XS GIS Cut Line= 6
      3166444.91     13895628.12      3160759.46     13893712.43
      3159627.82     13892884.45      3159100.36     13892748.49
      3158015.92     13891557.46      3157336.54     13890902.31
#Sta/Elev= 30
 -2080.8   52.98   -2037   53.14 -1825.8   52.32 -1778.5   50.15   -1447   49.28
  -484.8   48.91    69.2   50.22   565.7   48.81    2000   50.62  4794.4   50.36
  4885.7   50.77  4969.7   26.79  4978.2   21.57  4979.7   19.33    4994   17.57
  5017.7   19.51  5027.6   25.24  5040.3   27.19  5050.7    32.7  5112.9   47.21
  5647.6   45.52    5865   44.87    6417    50.2  6616.5   50.71  7339.7   49.55
  8153.8   50.58  8380.9   48.99  8391.5   49.13  8402.1   51.94  8420.6   53.59
#Mann= 7 , 1 , 0
 -2080.8      .2       0   -2037     .99       0    2000     .14       0
  4794.4     .14       0  4885.7    .035       0  5112.9     .14       0
  5647.6     .14       0
#XS Ineff= 2 , 0
       0  3229.2    51.3               0
Permanent Ineff=
       F       F
Bank Sta=4885.7,5112.9
XS Rating Curve= 0 ,0
Exp/Cntr=0.3,0.1

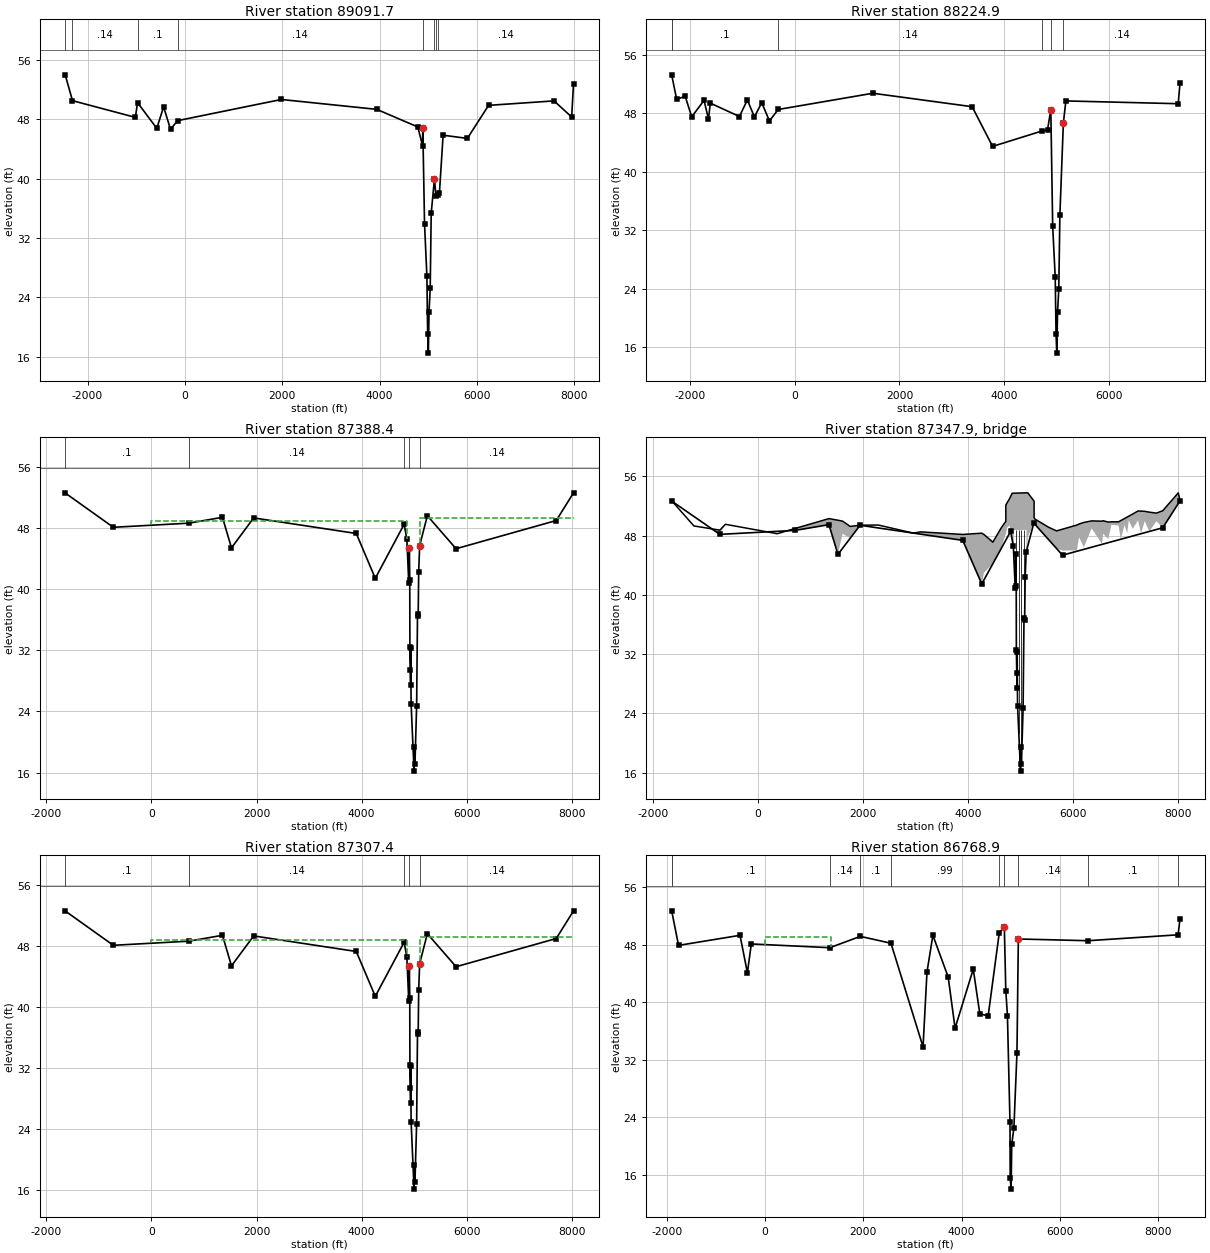
Type RM Length L Ch R = 1 ,89091.7 ,768.9,866.8,867.4
BEGIN DESCRIPTION:
Cross Section 89091.7-Interpolated
END DESCRIPTION:
XS GIS Cut Line= 6
      3166551.98     13895106.93      3160162.72     13892099.34
       3159410.1     13892258.47      3158485.28     13891458.46
       3157970.7     13891433.36      3157372.25     13890896.82
#Sta/Elev= 30
 -2459.9   53.97 -2310.3   50.49 -1018.1   48.24  -973.9   50.23  -578.2   46.76
  -437.9   49.67  -296.4   46.63    -151    47.8  1980.7   50.65  3942.1   49.32
  4784.6   46.95  4881.7   44.44  4887.3   46.81    4923   33.86  4971.3   26.87
  4987.1   19.08  5001.3    16.5  5015.5   22.06  5039.5   25.24  5059.9   35.34
  5126.8   39.97  5156.8   37.69    5202   37.82    5229   38.08  5304.4   45.84
  5802.9   45.41    6239   49.86  7583.4   50.46  7945.7   48.29  7984.2   52.78
#Mann= 8 , 1 , 0
 -2459.9      .2       0 -2310.3     .14       0  -973.9      .1       0
    -151     .14       0  4887.3    .035       0  5126.8     .14       0
  5156.8      .2       0    5202     .14       0
Bank Sta=4887.3,5126.8
XS Rating Curve= 0 ,0
Exp/Cntr=0.3,0.1

Type RM Length L Ch R = 1 ,88224.9 ,857.8,836.5,527
BEGIN DESCRIPTION:
Cross Section 88224.9
END DESCRIPTION:
XS GIS Cut Line= 6
      3166292.07     13894349.83      3162257.94     13892281.91
      3160787.27     13891585.26      3159174.51      13891307.2
      3157902.34      13891284.8       3157410.7     13890896.82
#Sta/Elev= 30
 -2344.4   53.23 -2249.4   49.87 -2086.7   50.31 -1962.8   47.48 -1726.8   49.74
 -1642.5   47.17 -1607.5   49.36 -1052.6   47.53  -900.9   49.79    -766   47.47
  -626.9   49.42  -479.5   46.93  -312.2   48.49  1492.7   50.71  3386.4   48.87
  3777.2   43.44  4728.2   45.57  4824.2   45.66  4887.3   48.48    4923   32.53
  4971.3   25.54  4987.1   17.75  5001.3   15.17  5015.5   20.73  5039.5   23.91
  5059.9   34.01  5126.8   46.64  5174.3   49.66  7317.6   49.28  7351.4   52.11
#Mann= 6 , 1 , 0
 -2344.4      .2       0 -2344.4      .1       0  -312.2     .14       0
  4728.2     .07       0  4887.3    .035       0  5126.8     .14       0
Bank Sta=4887.3,5126.8
XS Rating Curve= 0 ,0
Exp/Cntr=0.5,0.3

Type RM Length L Ch R = 1 ,87388.4 ,81,81,81
BEGIN DESCRIPTION:
Upstream Section of Bridge/Culvert/Weir
END DESCRIPTION:
XS GIS Cut Line= 6
      3166301.14      13893647.9       3164807.2     13892575.45
      3162877.06     13892061.82      3161511.99     13891256.58
      3160938.27     13891122.57      3157290.19       13890926.
#Sta/Elev= 30
 -1641.5   52.65  -725.7   48.15   711.2   48.69  1351.8   49.46  1523.3   45.45
  1945.5   49.38    3899   47.34  4260.9   41.46  4810.3   48.55    4862   46.58
  4897.7    40.9 4908.82   45.48 4917.18    41.2  4919.6   32.47  4927.8   29.39
    4934   27.41 4934.89   32.32  4942.8   24.97 4999.26   16.18  5002.8   19.38
 5016.24   17.17  5047.9   24.77 5064.62   36.79  5077.4   36.58 5087.17   42.34
 5105.86   45.76  5251.9   49.67  5798.4   45.34  7705.7   49.04  8034.5   52.67
#Mann= 5 , 1 , 0
 -1641.5      .1       0   711.2     .14       0  4810.3     .07       0
 4908.82     .04       0 5105.86     .14       0
#XS Ineff= 2 , 0
       0    4862      49    5120       0    49.4
Permanent Ineff=
       F       F
Bank Sta=4908.82,5105.86
XS Rating Curve= 0 ,0
Exp/Cntr=0.5,0.3

Type RM Length L Ch R = 3 ,87347.9 ,,,
BEGIN DESCRIPTION:
NORTH LAKE HOUSTON PARKWAY - 35 degree skew
Structure ID: P00-23
END DESCRIPTION:
Bridge Culvert--1,0,-1,-1, 0
Deck Dist Width WeirC Skew NumUp NumDn MinLoCord MaxHiCord MaxSubmerge Is_Ogee
10,61,2.6,0, 60, 60, , , 0.95, 0, 1,1,,
 -1641.5 -1618.2 -1218.5  -725.7  -619.1   367.5  1351.8  1523.3  1610.9  1757.8
  1945.5  2292.3    2934  2989.2    3098    3899  4260.9  4303.1    4472  4629.8
 4718.69  4718.8  4747.3  4789.1  4840.5 4868.79 4868.88 5112.44 5112.55    5123
    5138  5251.9  5257.5 5257.61  5273.2  5525.8  5546.3  5684.7  6072.2  6113.5
  6203.6  6354.2  6548.9  6571.1  6668.9  6730.1  6864.1  6909.1  6977.5  7029.2
  7059.2  7134.3  7236.2  7292.1  7362.1    7450  7585.3  7705.7  8002.3  8034.5
   52.66   52.51    49.3   48.73   49.52   48.25   50.29   50.07   49.95   49.23
    49.4   49.42   48.37   48.37    48.5   48.15   48.32   48.14   47.11   49.02
   49.92   52.12   52.47   52.97   53.72   53.72   53.72   53.77   53.77   53.77
   53.77   52.69   52.62   50.42   50.23   49.15   49.08   48.63   49.42   49.56
   49.77   49.98   49.94      50   49.82   49.86   49.85   50.03   50.29    50.5
   50.61   50.91   51.32    51.3   51.27   51.16   51.03   51.35   53.77   52.68
   52.66    51.4   49.29   48.16   49.51   48.17   49.47   45.46   48.25   47.24
   49.39   49.41   48.01   46.69   48.26   47.35   41.47   42.98   43.44   44.82
   48.24   48.24    49.1   49.37   47.41   45.68   48.72   48.77   45.36   44.71
   47.83   49.68   49.56   49.56   49.23   46.87   45.44   45.95   46.01   47.76
   46.43   48.98   46.87   48.25   47.53   49.45   49.35   47.45   49.42   48.32
   50.04   48.91   50.05   47.92   49.95   48.48   49.94   49.05   52.36   52.68
 -1641.5 -1618.2 -1218.5  -725.7  -619.1   367.5  1351.8  1523.3  1610.9  1757.8
  1945.5  2292.3    2934  2989.2    3098    3899  4260.9  4303.1    4472  4629.8
 4718.69  4718.8  4747.3  4789.1  4840.5 4868.79 4868.88 5112.44 5112.55    5123
    5138  5251.9  5257.5 5257.61  5273.2  5525.8  5546.3  5684.7  6072.2  6113.5
  6203.6  6354.2  6548.9  6571.1  6668.9  6730.1  6864.1  6909.1  6977.5  7029.2
  7059.2  7134.3  7236.2  7292.1  7362.1    7450  7585.3  7705.7  8002.3  8034.5
   52.66   52.51    49.3   48.73   49.52   48.25   50.29   50.07   49.95   49.23
    49.4   49.42   48.37   48.37    48.5   48.15   48.32   48.14   47.11   49.02
   49.92   52.12   52.47   52.97   53.72   53.72   53.72   53.77   53.77   53.77
   53.77   52.69   52.62   50.42   50.23   49.15   49.08   48.63   49.42   49.56
   49.77   49.98   49.94      50   49.82   49.86   49.85   50.03   50.29    50.5
   50.61   50.91   51.32    51.3   51.27   51.16   51.03   51.35   53.77   52.68
   52.62   51.36   49.25   48.12   49.47   48.13   49.43   45.42   48.21    47.2
   49.35   49.37   47.97   46.65   48.22   47.31   41.43   42.94    43.4   44.78
    48.2    48.2   49.06   49.33   47.37   45.64   48.68   48.73   45.32   44.67
   47.79   49.64   49.52   49.52   49.19   46.83    45.4   45.91   45.97   47.72
   46.39   48.94   46.83   48.21   47.49   49.41   49.31   47.41   49.38   48.28
      50   48.87   50.01   47.88   49.91   48.44    49.9   49.01   52.32   52.64
Pier Skew, UpSta & Num, DnSta & Num=  ,4917.2, 2 ,4917.2, 2 , 0 , 0 , 0 ,,
     1.8     1.8
   36.96   49.73
     1.8     1.8
   36.92   49.69
Pier Skew, UpSta & Num, DnSta & Num=  ,4966.3, 2 ,4966.3, 2 , 0 , 0 , 0 ,,
     1.8     1.8
   21.29   49.74
     1.8     1.8
   21.25    49.7
Pier Skew, UpSta & Num, DnSta & Num=  ,5016.2, 2 ,5016.2, 2 , 0 , 0 , 0 ,,
     1.8     1.8
   16.33   49.75
     1.8     1.8
   16.29   49.71
Pier Skew, UpSta & Num, DnSta & Num=  ,5064.6, 2 ,5064.6, 2 , 0 , 0 , 0 ,,
     1.8     1.8
   35.13   49.76
     1.8     1.8
   35.09   49.72
BR Coef= 1 , 1 , 0 ,1.25, 0 ,,,0.8,-1,2,0,
WSPro=,,,, 1 ,,,, 0 ,,,, 0 ,,,,-1 ,-1 ,-1 , 0 , 0 , 0 , 0 , 0
BR U #Sta/Elev= 30
 -1641.5   52.66  -725.7   48.16   711.2    48.7  1351.8   49.47  1523.3   45.46
  1945.5   49.39    3899   47.35  4260.9   41.47  4810.3   48.56    4862   46.59
  4897.7   40.91 4908.82   45.49 4917.18   41.21  4919.6   32.48  4927.8    29.4
    4934   27.42 4934.89   32.33  4942.8   24.98 4999.26   16.19  5002.8   19.39
 5016.24   17.18  5047.9   24.78 5064.62    36.8  5077.4   36.59 5087.17   42.35
 5105.86   45.77  5251.9   49.68  5798.4   45.35  7705.7   49.05  8034.5   52.68
BR U #Mann= 5
 -1641.5      .1   711.2     .14  4810.3     .07 4908.82     .04 5105.86     .14
BR U Banks=4908.82,5105.86
BR D #Sta/Elev= 30
 -1641.5   52.62  -725.7   48.12   711.2   48.66  1351.8   49.43  1523.3   45.42
  1945.5   49.35    3899   47.31  4260.9   41.43  4810.3   48.52    4862   46.55
  4897.7   40.87 4908.82   45.45 4917.18   41.17  4919.6   32.44  4927.8   29.36
    4934   27.38 4934.89   32.29  4942.8   24.94 4999.26   16.15  5002.8   19.35
 5016.24   17.14  5047.9   24.74 5064.62   36.76  5077.4   36.55 5087.17   42.31
 5105.86   45.73  5251.9   49.64  5798.4   45.31  7705.7   49.01  8034.5   52.64
BR D #Mann= 5
 -1641.5      .1   711.2     .14  4810.3     .07 4908.82     .04 5105.86     .14
BR D Banks=4908.82,5105.86
BC Design=,, 0 ,, 0 ,,,,,,
BC HTab HWMax=52.67
BC Use User HTab Curves=0
BC User HTab FreeFlow(D)= 0

Type RM Length L Ch R = 1 ,87307.4 ,538.5,538.5,538.5
BEGIN DESCRIPTION:
Downstream Section of Bridge/Culvert/Weir
END DESCRIPTION:
XS GIS Cut Line= 6
      3166311.44     13893567.56       3164817.5     13892495.11
      3162887.36     13891981.48      3161522.29     13891176.24
      3160948.57     13891042.23      3157300.49     13890845.66
#Sta/Elev= 30
 -1641.5   52.58  -725.7   48.08   711.2   48.62  1351.8   49.39  1523.3   45.38
  1945.5   49.31    3899   47.27  4260.9   41.39  4810.3   48.48    4862   46.51
  4897.7   40.83 4908.82   45.41 4917.18   41.13  4919.6    32.4  4927.8   29.32
    4934   27.34 4934.89   32.25  4942.8    24.9 4999.26   16.11  5002.8   19.31
 5016.24    17.1  5047.9    24.7 5064.62   36.72  5077.4   36.51 5087.17   42.27
 5105.86   45.69  5251.9    49.6  5798.4   45.27  7705.7   48.97  8034.5    52.6
#Mann= 5 , 1 , 0
 -1641.5      .1       0   711.2     .14       0  4810.3     .07       0
 4908.82     .04       0 5105.86     .14       0
#XS Ineff= 2 , 0
       0    4862    48.8    5120       0    49.2
Permanent Ineff=
       F       F
Bank Sta=4908.82,5105.86
XS Rating Curve= 0 ,0
Exp/Cntr=0.5,0.3

Type RM Length L Ch R = 1 ,86768.9 ,458.3,780.1,793.1
BEGIN DESCRIPTION:
Cross Section 86768.9
END DESCRIPTION:
XS GIS Cut Line= 6
      3166335.82     13893469.92      3162764.31     13890777.13
      3160664.95     13890603.32      3159454.19     13890205.83
      3158612.91     13890749.58      3157133.84     13890696.53
#Sta/Elev= 30
 -1898.5    52.7 -1758.5    47.9  -508.5    49.3  -358.5    44.1  -278.5    48.1
  1317.8   47.58  1939.1   49.15  2561.5    48.2  3214.4    33.8  3294.4    44.2
  3414.4    49.3  3725.7    43.5  3865.7    36.4  4235.7    44.6  4368.8    38.4
  4538.8    38.1  4765.5   49.69  4867.8   50.41  4897.5   41.62  4930.7   38.15
  4982.7   23.32  4986.6    15.6  5005.5   14.05  5018.2   20.26  5062.1   22.53
  5124.7      33  5152.7   48.79  6568.6   48.55  8402.4   49.37  8440.7    51.6
#Mann= 10 , 1 , 0
 -1898.5      .2       0 -1898.5      .1       0  1317.8     .14       0
  1939.1      .1       0  2561.5     .99       0  4765.5      .1       0
  4867.8     .04       0  5152.7     .14       0  6568.6      .1       0
  8402.4     .14       0
#XS Ineff= 2 , 0
       0    1341      49               0
Permanent Ineff=
       F       F
Bank Sta=4867.8,5152.7
XS Rating Curve= 0 ,0
Exp/Cntr=0.3,0.1

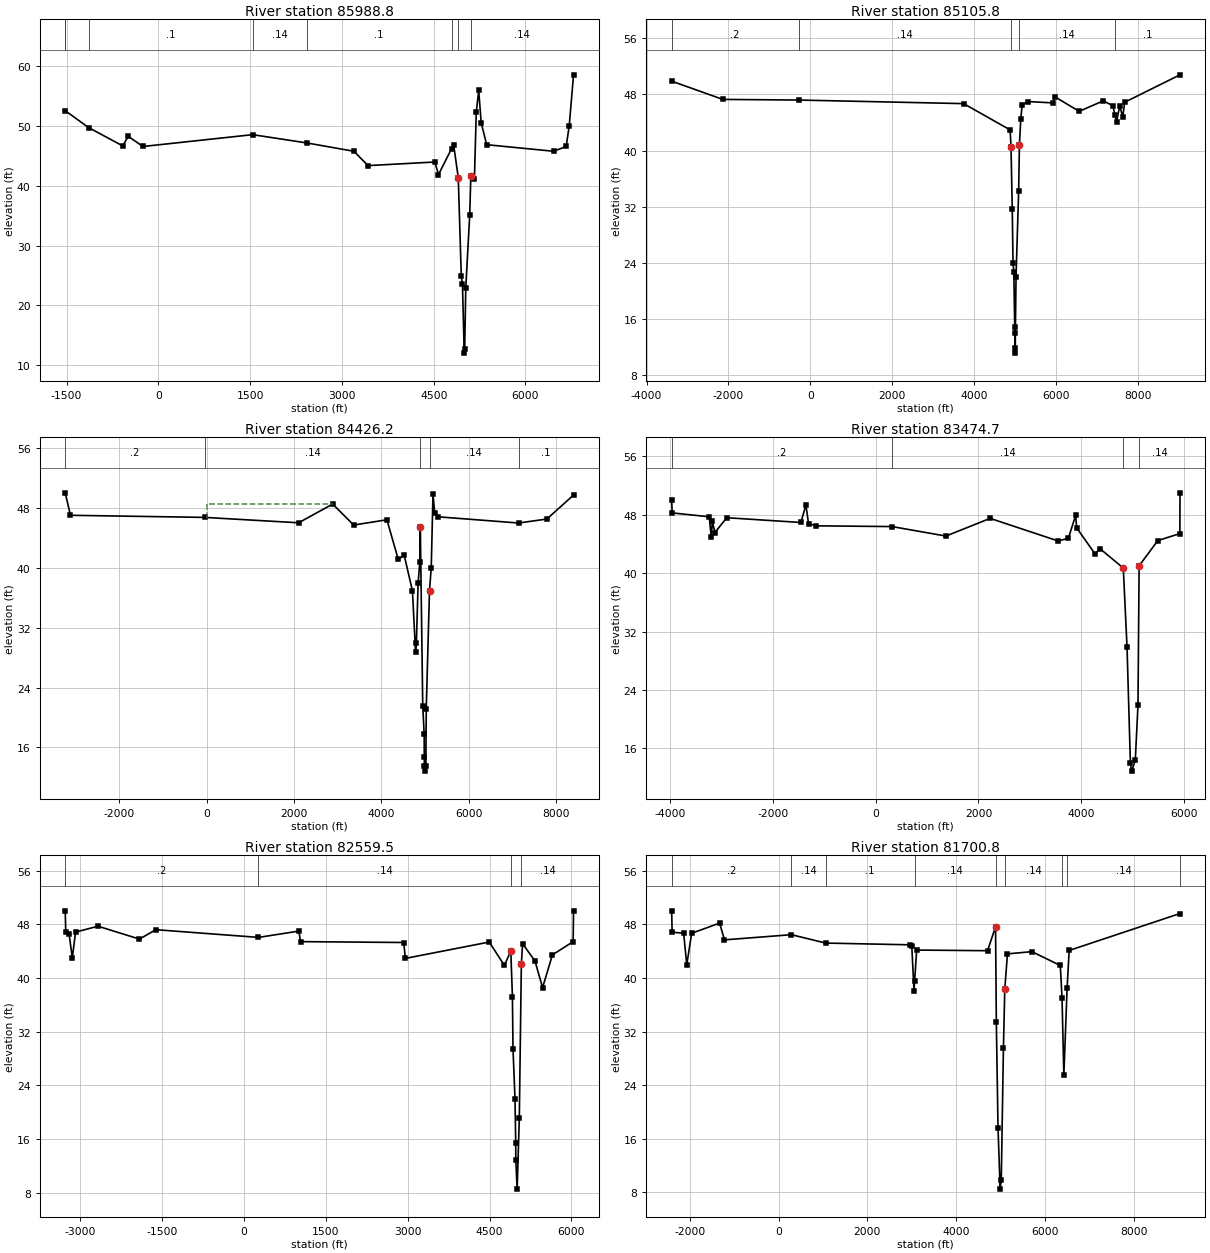
Type RM Length L Ch R = 1 ,85988.8 ,1145,883,343.4
BEGIN DESCRIPTION:
Cross Section 85988.8-Interpolated
END DESCRIPTION:
XS GIS Cut Line= 6
      3166424.52     13893053.05       3162970.8      13890394.3
      3161196.32     13890188.56      3160587.69     13889734.23
      3160416.24     13889699.94      3159231.29     13890008.98
#Sta/Elev= 30
 -1522.2    52.6 -1139.1   49.76  -582.2    46.7  -492.2    48.3  -252.2    46.6
  1540.1   48.58  2429.1   47.19  3196.4    45.8  3426.4    43.4  4518.3      44
  4578.3    41.9  4790.9   46.21  4825.5    46.9  4901.4    41.4  4950.7   24.88
  4969.8   23.58  4998.8      12  5006.1   12.69  5023.8   22.84  5088.4   35.13
  5106.6   41.61  5165.5    41.2  5195.5    52.3  5235.5      56  5275.5    50.6
  5365.5    46.9  6459.9    45.8  6665.1    46.6  6715.1    50.1  6785.1    58.6
#Mann= 8 , 1 , 0
 -1522.2      .2       0 -1522.2      .1       0 -1139.1      .1       0
  1540.1     .14       0  2429.1      .1       0  4790.9     .14       0
  4901.4     .04       0  5106.6     .14       0
Bank Sta=4901.4,5106.6
XS Rating Curve= 0 ,0
Exp/Cntr=0.3,0.1

Type RM Length L Ch R = 1 ,85105.8 ,903,679.6,469.4
BEGIN DESCRIPTION:
Cross Section 85105.8
END DESCRIPTION:
XS GIS Cut Line= 6
      3169720.36     13889523.65      3162325.64      13889429.8
       3161724.5     13889304.56      3161056.57     13889229.42
      3159102.84     13889669.45      3157549.38     13890430.95
#Sta/Elev= 30
 -3385.7    49.9 -2135.7    47.3  -288.3   47.21  3744.3    46.7  4879.8   42.96
  4901.4   40.58  4931.8   31.71  4950.7   24.06  4969.8   22.76  4992.5   14.83
  4998.8   11.18  5006.1   11.87  5007.9   13.99  5023.8   22.02  5088.4   34.31
  5106.6   40.79  5139.7   44.49  5173.5    46.5  5305.8      47  5935.8    46.8
  5965.8    47.7  6565.8    45.6  7155.8    47.1  7388.5    46.4  7442.5   45.02
  7478.5    44.1  7558.5    46.4  7628.5    44.8  7678.5    46.9  9028.5    50.8
#Mann= 5 , 1 , 0
 -3385.7      .2       0  -288.3     .14       0  4901.4    .035       0
  5106.6     .14       0  7442.5      .1       0
Bank Sta=4901.4,5106.6
XS Rating Curve= 0 ,0
Exp/Cntr=0.3,0.1

Type RM Length L Ch R = 1 ,84426.2 ,666.3,951.5,1127.7
BEGIN DESCRIPTION:
Cross Section 84426.2
END DESCRIPTION:
XS GIS Cut Line= 6
      3169218.29      13888982.9      3161874.79     13888486.34
      3161482.38     13888528.09       3160739.3     13888720.12
      3159236.22     13889189.29      3157848.65     13889833.79
#Sta/Elev= 30
 -3234.9      50 -3114.9      47   -47.2   46.72  2105.1      46  2885.1    48.5
  3365.1    45.7  4125.4    46.4  4385.4    41.1    4520    41.7    4710    36.9
    4780    28.8  4799.8    29.9  4839.8      38  4879.8    40.8  4889.6   45.39
  4945.3   21.56  4978.4   17.76  4980.2   14.71  4983.2   13.55  5000.9   12.84
  5017.6   13.52  5025.7   21.17  5100.1   36.95  5139.8      40  5179.8    49.8
  5219.8    47.3  5290.8    46.8  7136.7   45.97  7785.4    46.5  8395.4    49.7
#Mann= 5 , 1 , 0
 -3234.9      .2       0   -47.2     .14       0  4889.6    .035       0
  5100.1     .14       0  7136.7      .1       0
#XS Ineff= 2 , 0
       0  2885.1    48.5               0
Permanent Ineff=
       F       F
Bank Sta=4889.6,5100.1
XS Rating Curve= 0 ,0
Exp/Cntr=0.3,0.1

Type RM Length L Ch R = 1 ,83474.7 ,904.4,915.2,922.3
BEGIN DESCRIPTION:
Cross Section 83474.7
END DESCRIPTION:
XS GIS Cut Line= 6
      3169783.35     13888560.85      3162000.02     13887785.01
      3160989.77     13887751.61       3160705.9     13887785.01
       3159961.3     13887931.59      3159958.74     13887931.25
#Sta/Elev= 30
 -3963.4      50 -3953.4   48.25 -3233.4   47.72 -3193.4   44.92 -3173.4    47.1
 -3123.4   45.56 -2893.4   47.59 -1453.4   46.94 -1353.4   49.31 -1303.4   46.76
 -1153.4   46.48   317.7   46.38  1366.6   45.08  2226.6    47.5  3546.6   44.41
  3746.6   44.77  3888.5   47.92  3908.5    46.2  4268.5    42.6  4358.5   43.37
  4814.3    40.7  4887.4   29.83  4952.5   13.96  4976.4   12.89  5047.6   14.38
    5100   21.95  5122.1      41  5485.2   44.46  5914.1   45.42  5916.6      51
#Mann= 4 , 1 , 0
 -3963.4      .2       0   317.7     .14       0  4814.3     .04       0
  5122.1     .14       0
Bank Sta=4814.3,5122.1
XS Rating Curve= 0 ,0
Exp/Cntr=0.3,0.1

Type RM Length L Ch R = 1 ,82559.5 ,1274.2,858.7,648.7
BEGIN DESCRIPTION:
Cross Section 82559.5
END DESCRIPTION:
XS GIS Cut Line= 6
      3169098.13     13887526.27       3161725.2     13887076.18
      3161081.62     13886941.75      3160812.35      13886908.7
       3160620.9     13887123.68      3159914.18     13887122.85
#Sta/Elev= 30
 -3271.6      50 -3261.6   46.89 -3201.6   46.61 -3141.6   42.99 -3081.6   46.83
 -2671.6   47.71 -1911.6   45.79 -1611.6   47.19   267.8   46.04  1008.4   46.98
  1038.4   45.41  2928.4   45.28  2958.4   42.91    4495   45.35  4772.5   41.86
  4889.3   44.03    4919    37.2  4929.6   29.48  4966.2   22.01  4979.5   15.37
  4980.9   12.85  5005.6    8.53  5045.3   19.13  5082.9   42.13  5105.7   45.08
  5331.7   42.54  5471.7   38.56  5651.7   43.44  6031.7   45.41  6038.4      50
#Mann= 4 , 1 , 0
 -3271.6      .2       0   267.8     .14       0  4889.3     .04       0
  5082.9     .14       0
Bank Sta=4889.3,5082.9
XS Rating Curve= 0 ,0
Exp/Cntr=0.3,0.1

Type RM Length L Ch R = 1 ,81700.8 ,348.7,921,934
BEGIN DESCRIPTION:
Cross Section 81700.8
Coincident Section with P126-00-00, Cross Section 3710.3-Interpolated
END DESCRIPTION:
XS GIS Cut Line= 6
      3168286.46     13886740.02      3161437.76     13885840.87
      3160992.34     13886325.08      3160557.28     13886505.48
      3158524.54     13886473.55        3157141.     13886441.62
#Sta/Elev= 30
 -2410.5      50 -2400.5   46.82 -2140.5   46.65 -2070.5   41.95 -1960.5   46.65
 -1330.5   48.17 -1220.5   45.67   286.7   46.44  1060.6   45.19  2969.5   44.93
  2999.5   44.78  3049.5   38.08  3063.8   39.53  3109.5   44.15    4707   44.05
  4886.6   47.63  4904.7   33.35  4942.3   17.68  4990.4    8.49  5015.8    9.89
  5064.4   29.56  5094.7   38.28    5155   43.58  5705.9   43.91  6345.9   41.85
  6384.5   37.01  6425.9   25.48  6499.5   38.56  6545.9   44.09  9042.8    49.6
#Mann= 9 , 1 , 0
 -2410.5      .2       0   286.7     .14       0  1060.6      .1       0
  3063.8     .14       0  4886.6     .04       0  5094.7     .14       0
  6384.5     .06       0  6499.5     .14       0  9042.8      .2       0
Bank Sta=4886.6,5094.7
XS Rating Curve= 0 ,0
Exp/Cntr=0.3,0.1

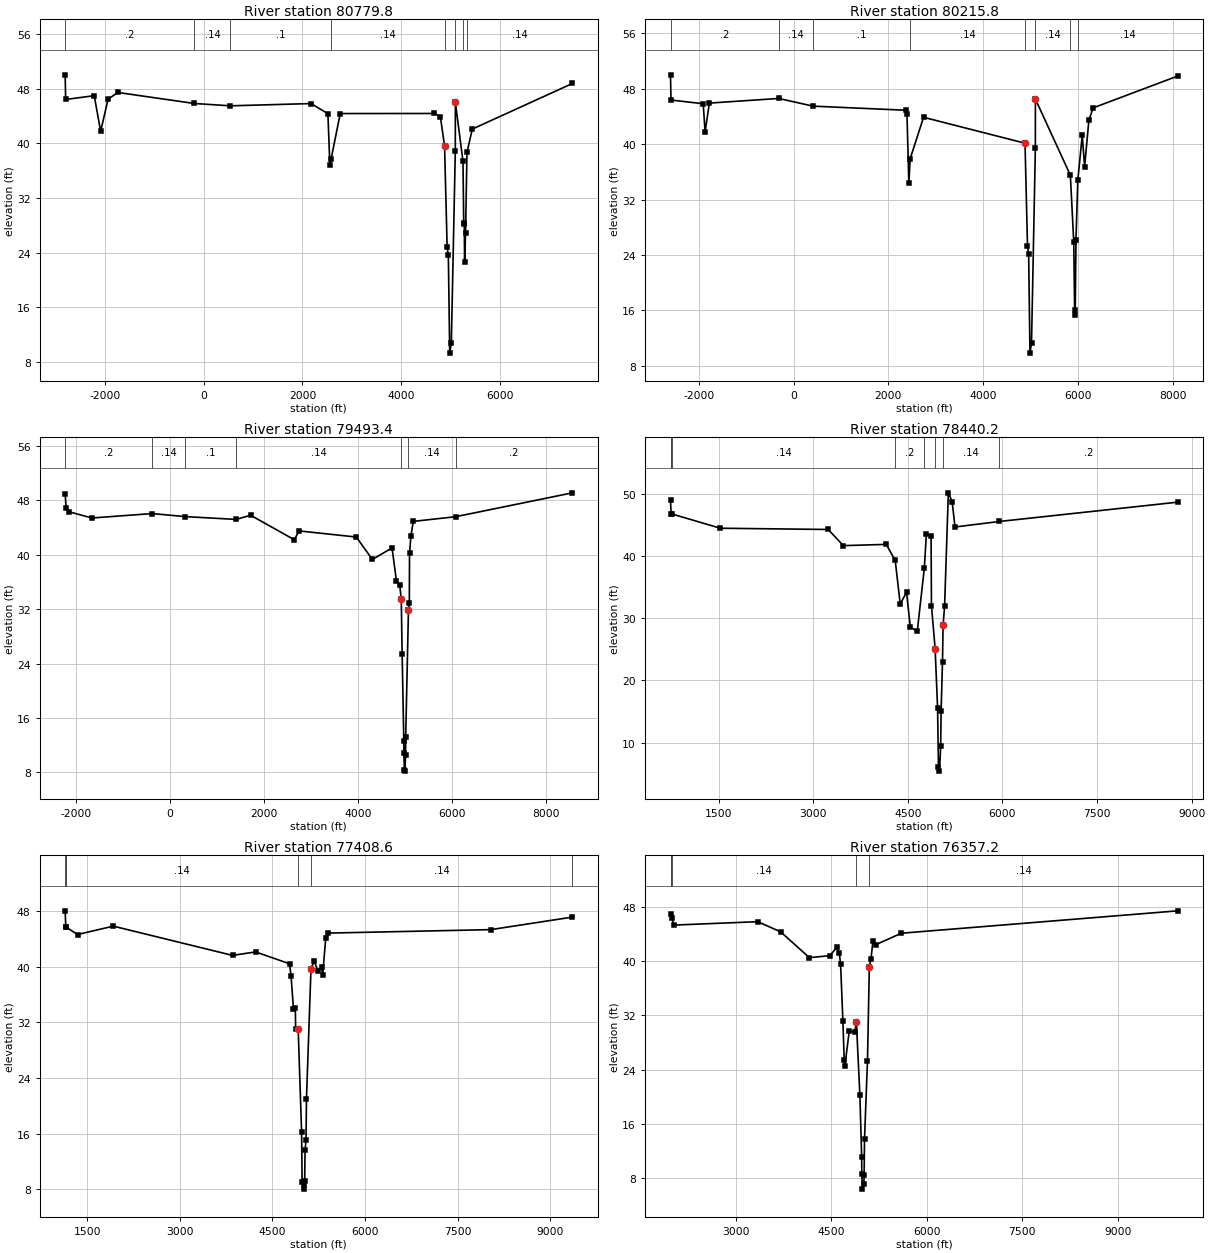
Type RM Length L Ch R = 1 ,80779.8 ,374.2,564,631.7
BEGIN DESCRIPTION:
Cross Section 80779.8-Interpolated
Coincident Section with P126-00-00, Cross Section 2243.2
END DESCRIPTION:
XS GIS Cut Line= 6
      3168229.19     13886443.21      3161489.68     13885688.59
      3160372.15     13885709.43      3159986.48       13885688.
      3159767.46     13885649.91      3158002.69     13885905.05
#Sta/Elev= 30
 -2814.2      50 -2804.2    46.4 -2224.2   46.95 -2094.2   41.73 -1944.2   46.44
 -1744.2   47.42    -193   45.81   537.9   45.47  2175.8    45.8  2515.8   44.32
  2555.8   36.79  2580.5   37.68  2765.8   44.34  4677.5   44.35  4797.5   43.87
  4882.4   39.62  4934.6   24.82  4958.9   23.64    4987    9.32  5019.6   10.81
  5100.6   38.88  5101.6   45.99    5256   37.36  5271.2    28.4  5282.1   28.22
  5288.8   22.63  5307.9   26.88    5337   38.65  5445.2   42.07    7477   48.74
#Mann= 8 , 1 , 0
 -2814.2      .2       0    -193     .14       0   537.9      .1       0
  2580.5     .14       0  4882.4     .04       0  5101.6     .14       0
    5256     .06       0    5337     .14       0
Bank Sta=4882.4,5101.6
XS Rating Curve= 0 ,0
Exp/Cntr=0.3,0.1

Type RM Length L Ch R = 1 ,80215.8 ,1725.3,722.4,719
BEGIN DESCRIPTION:
Cross Section 80215.8
Coincident Section with P126-00-00, Cross Section 1437.7
END DESCRIPTION:
XS GIS Cut Line= 6
      3167917.69      13886026.5      3161048.22      13885388.8
      3160544.01      13885172.5      3159931.73     13885069.03
      3158779.96     13885707.28      3157460.27     13885749.85
#Sta/Elev= 30
 -2598.8      50 -2588.8   46.36 -1908.8   45.83 -1868.8   41.76 -1778.8   45.92
  -312.8   46.59   407.4   45.48  2361.2   44.89  2391.2   44.28  2431.2   34.34
  2458.4   37.88  2741.2   43.87  4882.4   40.13  4934.6   25.33  4958.9   24.15
    4987    9.83  5019.6   11.32  5100.6   39.39  5101.6    46.5  5839.2   35.51
  5911.1   25.83  5930.1   15.33  5942.4   16.09  5957.6    26.2  5996.2   34.76
  6089.9   41.27  6139.9   36.76  6229.9   43.44  6319.9   45.23  8106.6   49.83
#Mann= 8 , 1 , 0
 -2598.8      .2       0  -312.8     .14       0   407.4      .1       0
  2458.4     .14       0  4882.4     .04       0  5101.6     .14       0
  5839.2     .06       0  5996.2     .14       0
Bank Sta=4882.4,5101.6
XS Rating Curve= 0 ,0
Exp/Cntr=0.3,0.1

Type RM Length L Ch R = 1 ,79493.4 ,1061.1,1053.2,1045.9
BEGIN DESCRIPTION:
Cross Section 79493.4
END DESCRIPTION:
XS GIS Cut Line= 6
      3167504.36     13885556.97      3161024.23     13884668.58
       3160626.7     13884499.93        3160187.     13884385.49
      3158557.67     13883952.96       3156868.5     13883942.65
#Sta/Elev= 30
 -2230.2      49 -2210.2    46.9 -2140.2    46.3 -1660.2    45.4  -376.1   46.05
   329.3    45.6  1409.9   45.19  1719.8    45.8  2649.8    42.2  2749.8    43.5
  3969.8    42.6  4310.5    39.3  4730.5      41  4822.4    36.2  4894.4   35.51
  4926.6   33.44    4945   25.39  4980.9   12.55  4982.7   10.78    4992    8.36
  5005.5    8.18  5017.4   10.54  5020.5   13.16  5079.7   31.86  5098.1   32.84
  5102.4    40.2  5132.4    42.8  5182.4    44.9  6085.9   45.59  8571.7    49.1
#Mann= 7 , 1 , 0
 -2230.2      .2       0  -376.1     .14       0   329.3      .1       0
  1409.9     .14       0  4926.6    .035       0  5079.7     .14       0
  6085.9      .2       0
Bank Sta=4926.6,5079.7
XS Rating Curve= 0 ,0
Exp/Cntr=0.3,0.1

Type RM Length L Ch R = 1 ,78440.2 ,532.7,1031.6,1149.5
BEGIN DESCRIPTION:
Cross Section 78440.2
END DESCRIPTION:
XS GIS Cut Line= 6
      3164841.57      13883342.5       3161739.3     13883756.21
      3161380.29     13883711.58      3160810.51     13883472.28
       3160081.2     13883364.02      3156888.17     13883352.45
#Sta/Elev= 30
     738      49     748    46.8   769.1   46.77    1528    44.5    3238    44.3
    3478    41.7  4157.7    41.9    4300   39.32  4379.5    32.3  4479.5    34.2
  4539.5    28.6  4649.5    27.9    4762   38.12  4793.5    43.5  4868.5    43.3
  4874.6   32.05    4933    25.1  4971.6   15.58  4985.7     6.1  5001.7     5.4
  5021.2    9.46  5027.5   15.07  5049.9   23.03  5058.9   28.91  5082.8   31.94
  5142.3    50.2  5202.3    48.8    5248    44.7  5952.9   45.59  8779.8    48.7
#Mann= 8 , 1 , 0
     738      .2       0     748      .1       0   769.1     .14       0
    4300      .2       0    4762     .14       0    4933    .035       0
  5058.9     .14       0  5952.9      .2       0
Bank Sta=4933,5058.9
XS Rating Curve= 0 ,0
Exp/Cntr=0.3,0.1

Type RM Length L Ch R = 1 ,77408.6 ,1476.2,1051.4,896.8
BEGIN DESCRIPTION:
Cross Section 77408.6
END DESCRIPTION:
XS GIS Cut Line= 6
      3164609.74     13883235.04      3161881.23     13883543.41
      3161631.75     13883316.61      3161081.61      13882380.8
      3160263.36     13882308.69      3157040.45     13882358.95
#Sta/Elev= 30
  1142.9      48  1152.9    45.7  1155.8   45.68  1342.9    44.6  1922.9    45.8
  3852.9    41.6  4225.9    42.1  4775.9    40.4    4800    38.7    4840    33.9
    4870      34  4874.9   31.08  4916.1   31.01  4971.2   16.26  4979.3    9.13
  5005.7    8.04    5018    8.57  5020.7    9.21  5027.6   13.62  5043.4   15.12
    5050   20.96  5123.3   39.65  5174.6    40.8  5234.6    39.4  5294.6    39.9
  5312.5    38.8  5362.5    44.1  5392.5    44.8  8033.9    45.3  9357.2    47.1
#Mann= 6 , 1 , 0
  1142.9      .2       0  1152.9      .1       0  1155.8     .14       0
  4916.1    .035       0  5123.3     .14       0  9357.2      .2       0
Bank Sta=4916.1,5123.3
XS Rating Curve= 0 ,0
Exp/Cntr=0.3,0.1

Type RM Length L Ch R = 1 ,76357.2 ,586.7,685.1,696.6
BEGIN DESCRIPTION:
Cross Section 76357.2
END DESCRIPTION:
XS GIS Cut Line= 6
      3164616.35     13883136.78      3162210.81     13881964.15
      3161997.09     13881995.78      3161512.12     13881759.36
      3160017.12     13881772.89      3157002.67     13881540.53
#Sta/Elev= 30
  1979.1    46.9  2002.7   46.36  2029.1    45.3  3349.1    45.8  3709.1    44.3
  4159.1    40.5  4479.1    40.8  4589.1      42  4629.1    41.2  4649.1    39.5
  4685.2    31.2  4705.2    25.5  4715.2    24.5  4785.2    29.7  4871.3    29.5
  4896.9   31.03  4951.4   20.33  4979.9    11.2  4981.6    8.59  4991.7    6.41
  5014.4    7.21  5018.3    8.49  5024.8   13.83  5071.2   25.35  5100.4    39.2
    5127   40.37  5157.4      43  5197.4    42.4  5603.1    44.1  9942.3    47.4
#Mann= 5 , 1 , 0
  1979.1      .2       0  1979.1      .1       0  2002.7     .14       0
  4896.9    .035       0  5100.4     .14       0
Bank Sta=4896.9,5100.4
XS Rating Curve= 0 ,0
Exp/Cntr=0.3,0.1

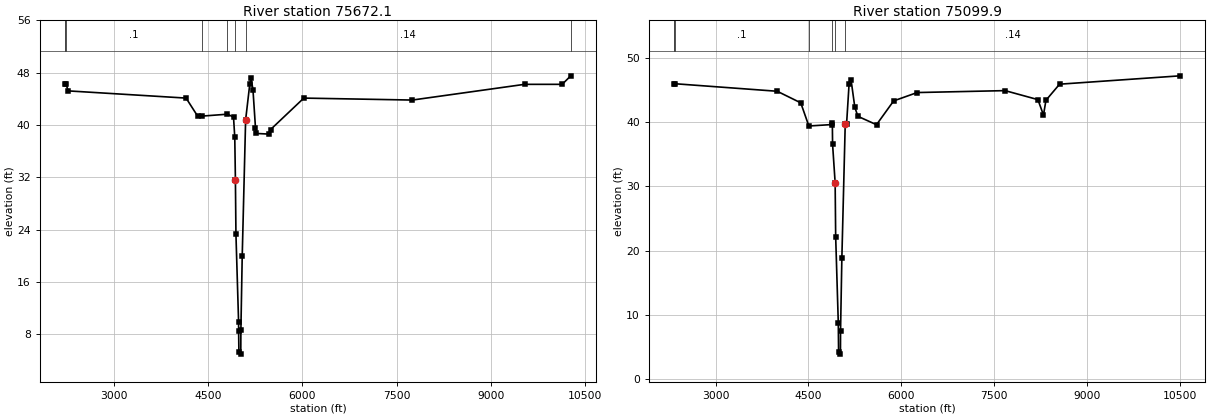
Type RM Length L Ch R = 1 ,75672.1 ,513,572.2,757.1
BEGIN DESCRIPTION:
Cross Section 75672.1-Interpolated
END DESCRIPTION:
XS GIS Cut Line= 5
      3164615.86     13882938.53      3162953.79     13881778.14
      3162439.51     13881451.51      3162085.07     13881243.01
       3157103.4     13880646.58
#Sta/Elev= 30
  2214.2    46.3  2229.8   46.22  2264.2    45.2  4144.2    44.1  4331.3    41.3
  4399.2   41.35  4802.2   41.64  4900.5    41.2  4920.5    38.1  4930.7   31.65
  4939.2   23.28  4981.5    9.87  4982.1    8.57  4986.3    5.32  5016.3       5
    5018    8.65  5039.1   19.91  5093.6   40.77  5160.5    46.3  5180.5    47.1
  5210.5    45.4  5250.5    39.6  5261.7    38.7  5471.7    38.6  5491.7    39.3
  6021.7    44.1  7751.7    43.8  9541.7    46.2 10141.7    46.2   10279    47.5
#Mann= 8 , 1 , 0
  2214.2      .2       0  2214.2      .1       0  2229.8      .1       0
  4399.2     .08       0  4802.2     .14       0  4930.7    .035       0
  5093.6     .14       0   10279      .2       0
Bank Sta=4930.7,5093.6
XS Rating Curve= 0 ,0
Exp/Cntr=0.3,0.1

Type RM Length L Ch R = 1 ,75099.9 ,1076,914.7,217.7
BEGIN DESCRIPTION:
Cross Section 75099.9
END DESCRIPTION:
XS GIS Cut Line= 5
      3164621.16     13882668.22      3162993.83     13881247.38
      3162505.95      13880783.6      3161891.58     13880434.25
      3157291.01     13879940.22
#Sta/Elev= 30
  2335.2      46    2345   45.97  3995.2    44.8  4375.2      43  4506.2    39.4
  4874.2   39.62  4885.5    39.9  4889.1   36.58  4930.7   30.58  4939.2   22.21
  4981.5     8.8  4986.3    4.25  5016.3    3.93    5018    7.58  5039.1   18.84
  5093.6    39.7  5115.8   39.77  5155.5    45.9  5188.7    46.5  5248.7    42.3
  5298.7    40.9  5598.7    39.6  5875.4    43.3  6255.4    44.6  7675.4    44.9
  8205.4    43.5  8295.4    41.1  8335.4    43.4  8555.4    45.9 10502.4    47.2
#Mann= 7 , 1 , 0
  2335.2      .2       0  2335.2      .1       0    2345      .1       0
  4506.2     .06       0  4874.2     .14       0  4930.7    .035       0
  5093.6     .14       0
#XS Ineff= 2 , 0
       0                  7675.4       0    44.9
Permanent Ineff=
       F       F
Bank Sta=4930.7,5093.6
XS Rating Curve= 0 ,0
Exp/Cntr=0.3,0.1