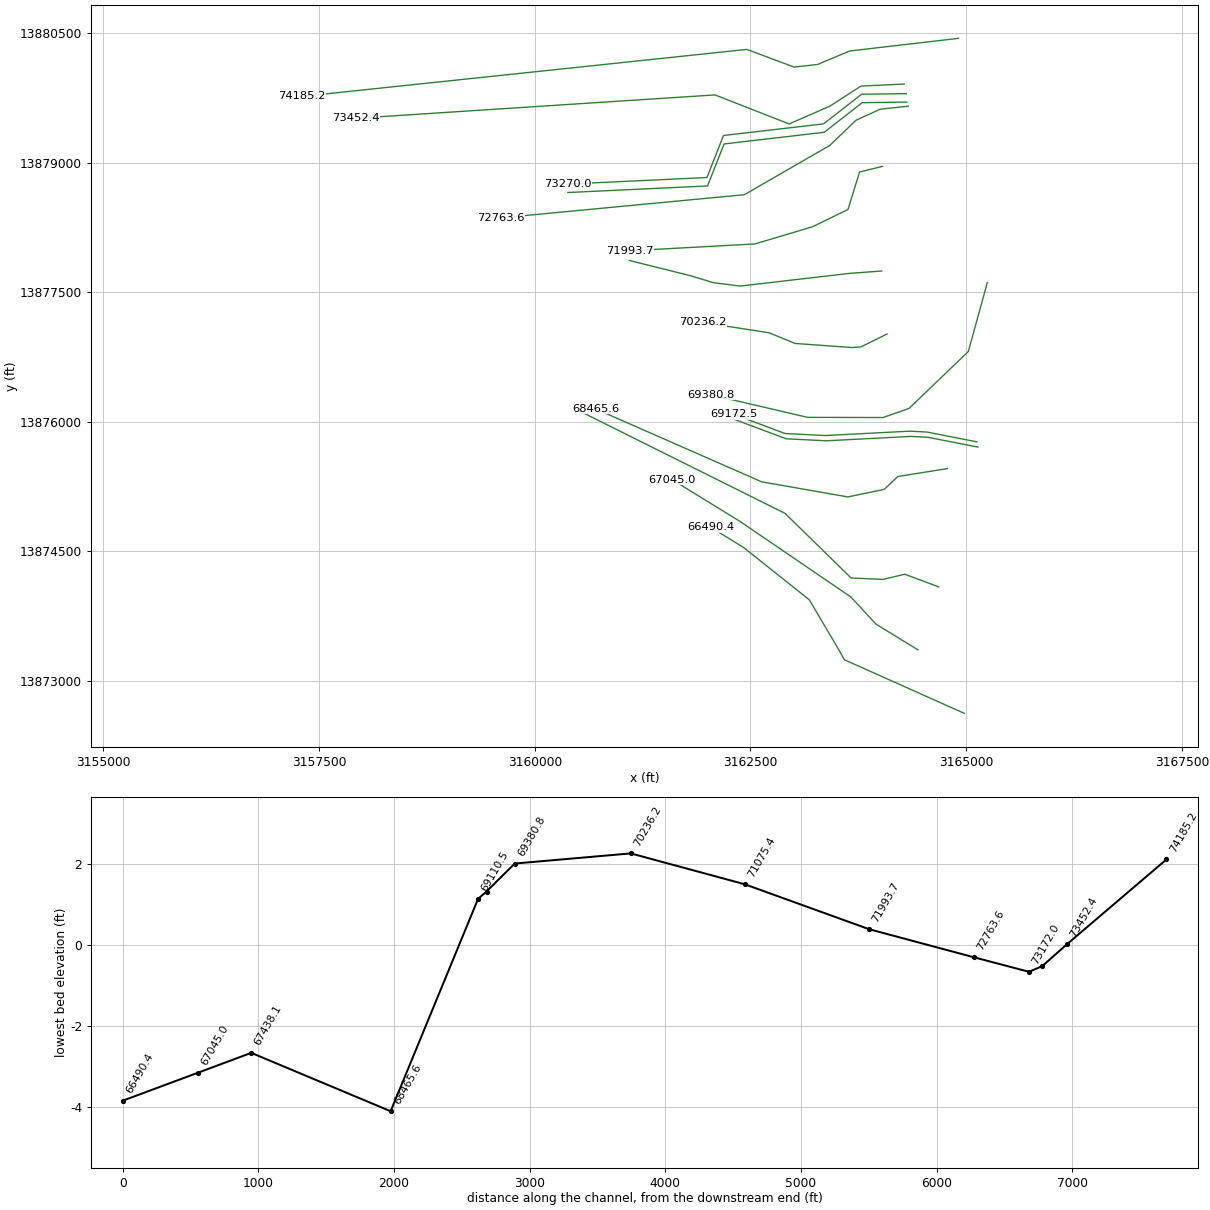
HEC-RAS study P100-00-00.prj: P100-00-00

--- P100-00-00.g01 (geometry) --- (continued)

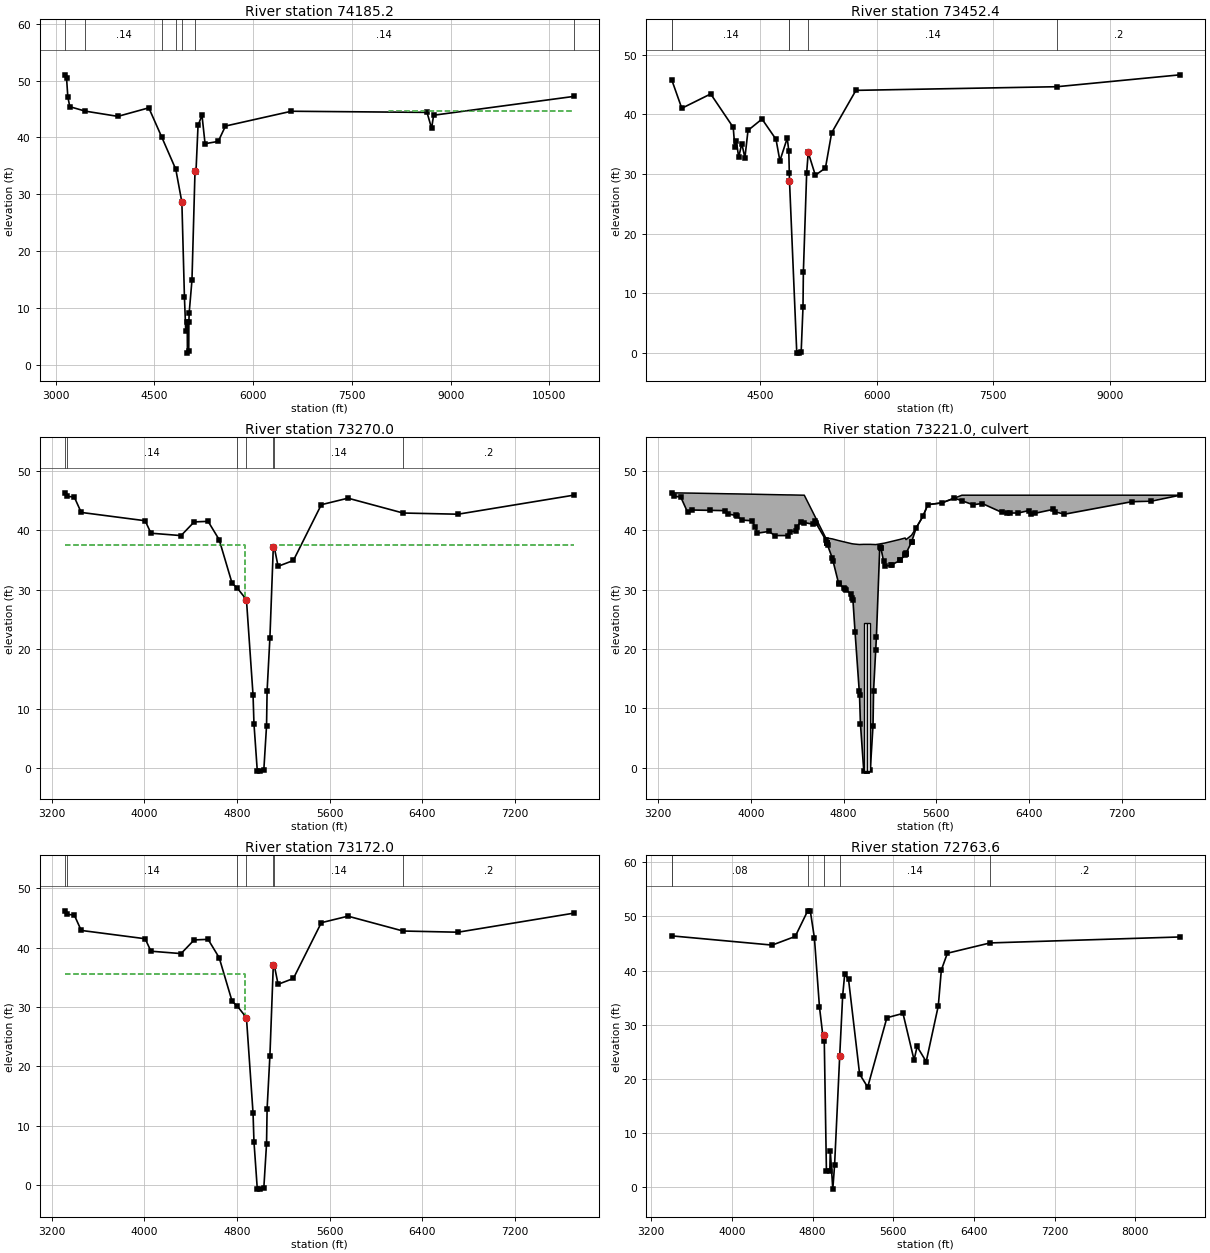
Type RM Length L Ch R = 1 ,74185.2 ,748.4,732.8,589.5
BEGIN DESCRIPTION:
Cross Section 74185.2
END DESCRIPTION:
XS GIS Cut Line= 6
       3164911.5     13880442.04      3163650.36     13880295.71
      3163276.92     13880139.11      3163005.88     13880108.99
      3162457.76     13880313.78      3157301.08     13879768.99
#Sta/Elev= 30
  3146.6      51  3166.6    50.5  3186.6    47.1  3216.6    45.4  3451.6   44.62
  3946.6    43.7  4416.2    45.2  4614.6   40.01    4826    34.4  4918.5   28.61
  4957.4   11.91  4977.6    5.93    5000    7.61  5002.6     2.1  5022.6    2.43
  5024.9    7.62  5029.6     9.2  5071.7   14.93  5117.9   34.06  5132.4    33.9
  5163.9    42.1  5223.9    43.9  5270.5    38.9  5470.5    39.3  5580.5      42
  6581.2    44.6  8641.2    44.4  8711.2    41.6  8741.2    43.9 10866.6    47.2
#Mann= 7 , 1 , 0
  3146.6     .08       0  3451.6     .14       0  4614.6     .08       0
    4826     .14       0  4918.5    .035       0  5117.9     .14       0
 10866.6      .2       0
#XS Ineff= 2 , 0
       0                  8071.2       0    44.7
Permanent Ineff=
       F       F
Bank Sta=4918.5,5117.9
XS Rating Curve= 0 ,0
Exp/Cntr=0.3,0.1

Type RM Length L Ch R = 1 ,73452.4 ,176.4,182.4,482.9
BEGIN DESCRIPTION:
Cross Section 73452.4-Interpolated
END DESCRIPTION:
XS GIS Cut Line= 6
       3164281.8     13879912.23      3163780.63     13879888.92
      3163419.32     13879655.82      3162947.84     13879450.22
      3162088.66     13879786.42      3157929.81     13879515.96
#Sta/Elev= 30
  3365.7    45.8  3495.7      41  3867.4    43.4  4157.4    37.8  4177.4    34.5
  4197.4    35.5  4227.4    32.8  4267.4    35.1  4307.4    32.7  4347.4    37.3
  4527.4    39.2  4707.4    35.8  4757.4    32.2  4851.7      36  4871.7    33.9
  4878.5   30.15  4880.8   28.88  4974.4     .06  5000.1     .01  5030.9     .21
  5054.4    7.66  5059.2   13.55  5101.7    30.2  5121.7    33.6  5213.1    29.8
  5343.1      31  5423.1    36.9    5735      44  8319.4   44.61  9902.6    46.6
#Mann= 6 , 1 , 0
  3365.7      .2       0  3365.7     .14       0  4878.5      .1       0
  4880.8     .04       0  5121.7     .14       0  8319.4      .2       0
Bank Sta=4880.8,5121.7
XS Rating Curve= 0 ,0
Exp/Cntr=0.5,0.3

Type RM Length L Ch R = 1 ,73270.0 ,98,98,98
BEGIN DESCRIPTION:
Upstream Section of Bridge/Culvert/Weir
END DESCRIPTION:
XS GIS Cut Line= 6
       3164304.5     13879801.26       3163787.3     13879794.45
       3163347.6     13879451.08      3162187.17      13879316.1
      3161995.53     13878829.24      3160377.28      13878753.3
#Sta/Elev= 30
  3315.9   46.33    3334   45.73    3394   45.63    3454   43.03  4006.2   41.63
  4056.2   39.53  4316.2   39.13  4429.4   41.43  4549.4   41.53  4645.4   38.44
    4757   31.09  4800.9   30.31  4880.8   28.34  4937.8   12.28  4945.7    7.47
  4974.4    -.48  5000.1    -.53  5030.9    -.33  5054.4    7.12  5059.2   13.01
  5083.5   21.96  5112.8   37.23  5122.6   37.01  5154.1   33.96  5286.2   34.94
  5527.2   44.33  5757.6   45.43  6233.2   42.93  6707.6   42.73  7705.1   45.93
#Mann= 7 , 1 , 0
  3315.9      .2       0    3334     .14       0  4800.9      .1       0
  4880.8    .035       0  5112.8      .1       0  5122.6     .14       0
  6233.2      .2       0
#XS Ineff= 2 , 0
       0    4867    37.5    5124       0    37.5
Permanent Ineff=
       F       F
Bank Sta=4880.8,5112.8
XS Rating Curve= 0 ,0
Exp/Cntr=0.5,0.3

Type RM Length L Ch R = 2 ,73221.0 ,,,
BEGIN DESCRIPTION:
UNKNOWN ROAD 1
Structure ID: P00-21
END DESCRIPTION:
Bridge Culvert--1,0,-1,-1, 0
Deck Dist Width WeirC Skew NumUp NumDn MinLoCord MaxHiCord MaxSubmerge Is_Ogee
10,78,3,0, 60, 60, , , 0.95, 0, 1,1,,
  3315.9    3334    3394    3454    3494    3774    3804    3874  3926.2  4006.2
  4036.2  4056.2  4156.2  4206.2  4316.2  4336.2  4386.2  4429.4    4461  4539.4
  4549.4  4561.4  4654.3 4655.59  4655.7  4703.3    4757  4866.9  4880.8  4899.3
  4937.8  4945.7  4974.4  5030.9  5054.4  5059.2  5077.8  5083.5  5112.8  5122.7
  5154.1  5286.2    5332  5339.4  5387.2  5427.2  5487.2  5527.2  5647.6  5757.6
  5821.9  5917.6  5997.6  6167.6  6307.6  6397.6  6417.6  6607.6  6707.6  7705.1
    46.3   46.29   46.28   46.26   46.25   46.15   46.14   46.12    46.1   46.07
   46.06   46.05   46.01   45.99   45.95   45.95   45.93   45.91    45.9   42.86
   42.47      42    38.4   38.39   38.69   38.54   38.26   37.75    37.7   37.66
   37.59    37.6   37.62   37.62    37.6    37.6   37.58    37.6   37.69   37.73
   37.83   38.45   38.69   38.42   39.16   40.41   42.41   44.31   44.61   45.41
    45.9    45.9    45.9    45.9    45.9    45.9    45.9    45.9    45.9    45.9
    46.3    45.7    45.6      43    43.4    43.3    42.7    42.5    41.7    41.6
    40.6    39.5    39.8    39.1    39.1    39.7    39.9    41.4   41.29      41
    41.5    41.2   37.91   37.84   37.84   35.27   31.06   29.23   28.31   22.84
   12.25    7.44    -.51    -.36    7.09   12.98   19.83   21.93    37.2   36.98
   33.93   34.91   35.81    36.1      38    40.4    42.4    44.3    44.6    45.4
   44.96    44.3    44.5      43    42.9    43.3    42.7    43.5    42.7    45.9
  3315.9    3334    3394    3454    3494    3774    3804    3874  3926.2  4006.2
  4036.2  4056.2  4156.2  4206.2  4316.2  4336.2  4386.2  4429.4    4461  4539.4
  4549.4  4561.4  4654.3 4655.59  4655.7  4703.3    4757  4866.9  4880.8  4899.3
  4937.8  4945.7  4974.4  5030.9  5054.4  5059.2  5077.8  5083.5  5112.8  5122.7
  5154.1  5286.2    5332  5339.4  5387.2  5427.2  5487.2  5527.2  5647.6  5757.6
  5821.9  5917.6  5997.6  6167.6  6307.6  6397.6  6417.6  6607.6  6707.6  7705.1
    46.3   46.29   46.28   46.26   46.25   46.15   46.14   46.12    46.1   46.07
   46.06   46.05   46.01   45.99   45.95   45.95   45.93   45.91    45.9   42.86
   42.47      42    38.4   38.39   38.69   38.54   38.26   37.75    37.7   37.66
   37.59    37.6   37.62   37.62    37.6    37.6   37.58    37.6   37.69   37.73
   37.83   38.45   38.69   38.42   39.16   40.41   42.41   44.31   44.61   45.41
    45.9    45.9    45.9    45.9    45.9    45.9    45.9    45.9    45.9    45.9
   46.18   45.58   45.48   42.88   43.28   43.18   42.58   42.38   41.58   41.48
   40.48   39.38   39.68   38.98   38.98   39.58   39.78   41.28   41.17   40.88
   41.38   41.08   37.79   37.72   37.72   35.15   30.94   29.11   28.19   22.72
   12.13    7.32    -.63    -.48    6.97   12.86   19.71   21.81   37.08   36.86
   33.81   34.79   35.69   35.98   37.88   40.28   42.28   44.18   44.48   45.28
   44.84   44.18   44.38   42.88   42.78   43.18   42.58   43.38   42.58   45.78
BR Coef= 1 , 0 , 0 ,1.25, 0 ,,,0.8,-1,2,0,
WSPro=,,,, 1 ,,,, 0 ,,,, 0 ,,,,-1 ,-1 ,-1 , 0 , 0 , 0 , 0 , 0
Culvert=2,25,25,78,0.015,0.4,1,8,1,-0.56,4990.7,-0.68,4990.7,Culvert #1  , 0 ,10
  4990.7  4990.7
BC Culvert Barrel=1,,0
Culvert Bottom n=0.015
Culvert=2,25,25,78,0.015,0.4,1,8,1,-0.58,5017,-0.69,5017,Culvert #2  , 0 ,10
    5017    5017
BC Culvert Barrel=1,,0
Culvert Bottom n=0.015
BR U #Sta/Elev= 90
  3315.9    46.3    3334    45.7    3394    45.6    3454      43    3494    43.4
  3645.9   43.35    3774    43.3    3804    42.7    3874    42.5  3876.2    42.4
  3926.2    41.7  4006.2    41.6  4036.2    40.6  4056.2    39.5  4156.2    39.8
  4206.2    39.1  4316.2    39.1  4336.2    39.7  4386.2    39.9  4399.4    40.6
  4429.4    41.4    4461   41.29  4539.4      41  4549.4    41.5  4561.4    41.2
  4645.4   38.41  4654.3   37.91 4655.59   37.84  4655.7   37.84 4655.81   37.83
  4662.3   37.47  4703.3   35.27  4709.1   34.82    4757   31.06    4765   30.92
  4800.9   30.28  4809.1   30.13  4820.7   29.95  4866.9   29.23    4877   28.56
  4880.8   28.31  4899.3   22.84  4935.2   12.97  4937.8   12.25  4945.7    7.44
  4974.4    -.51  5000.1    -.56  5002.9    -.54  5030.9    -.36  5054.4    7.09
  5059.2   12.98  5077.8   19.83  5083.5   21.93  5112.8    37.2  5122.6   36.98
  5122.7   36.98  5145.5   34.77  5154.1   33.93  5207.8   34.08  5215.3   34.16
    5286   34.91  5286.2   34.91    5332   35.81 5334.89   35.93    5335   35.93
 5335.11   35.93  5339.4    36.1    5387      38  5387.2      38  5427.2    40.4
  5487.2    42.4  5527.2    44.3  5647.6    44.6  5757.6    45.4  5821.9   44.96
  5917.6    44.3  5997.6    44.5  6167.6      43  6207.6    42.9  6233.2    42.9
  6307.6    42.9  6397.6    43.3  6417.6    42.7  6455.1   42.86  6607.6    43.5
  6627.6    43.1  6707.6    42.7  7287.6    44.8  7457.6    44.9  7705.1    45.9
BR U #Mann= 7
  3315.9      .2    3334     .14  4800.9      .1  4880.8    .035  5112.8      .1
  5122.6     .14  6233.2      .2
BR U Banks=4880.8,5112.8
BR D #Sta/Elev= 90
  3315.9   46.18    3334   45.58    3394   45.48    3454   42.88    3494   43.28
  3645.9   43.23    3774   43.18    3804   42.58    3874   42.38  3876.2   42.28
  3926.2   41.58  4006.2   41.48  4036.2   40.48  4056.2   39.38  4156.2   39.68
  4206.2   38.98  4316.2   38.98  4336.2   39.58  4386.2   39.78  4399.4   40.48
  4429.4   41.28    4461   41.17  4539.4   40.88  4549.4   41.38  4561.4   41.08
  4645.4   38.29  4654.3   37.79 4655.59   37.72  4655.7   37.72 4655.81   37.71
  4662.3   37.35  4703.3   35.15  4709.1    34.7    4757   30.94    4765    30.8
  4800.9   30.16  4809.1   30.01  4820.7   29.83  4866.9   29.11    4877   28.44
  4880.8   28.19  4899.3   22.72  4935.2   12.85  4937.8   12.13  4945.7    7.32
  4974.4    -.63  5000.1    -.68  5002.9    -.66  5030.9    -.48  5054.4    6.97
  5059.2   12.86  5077.8   19.71  5083.5   21.81  5112.8   37.08  5122.6   36.86
  5122.7   36.86  5145.5   34.65  5154.1   33.81  5207.8   33.96  5215.3   34.04
    5286   34.79  5286.2   34.79    5332   35.69 5334.89   35.81    5335   35.81
 5335.11   35.81  5339.4   35.98    5387   37.88  5387.2   37.88  5427.2   40.28
  5487.2   42.28  5527.2   44.18  5647.6   44.48  5757.6   45.28  5821.9   44.84
  5917.6   44.18  5997.6   44.38  6167.6   42.88  6207.6   42.78  6233.2   42.78
  6307.6   42.78  6397.6   43.18  6417.6   42.58  6455.1   42.74  6607.6   43.38
  6627.6   42.98  6707.6   42.58  7287.6   44.68  7457.6   44.78  7705.1   45.78
BR D #Mann= 7
  3315.9      .2    3334     .14  4800.9      .1  4880.8    .035  5112.8      .1
  5122.6     .14  6233.2      .2
BR D Banks=4880.8,5112.8
BC Design=,, 0 ,, 0 ,,,,,,
BC HTab HWMax=46.33
BC Use User HTab Curves=0
BC User HTab FreeFlow(D)= 0

Type RM Length L Ch R = 1 ,73172.0 ,408.4,408.4,408.4
BEGIN DESCRIPTION:
Downstream Section of Bridge/Culvert/Weir
END DESCRIPTION:
XS GIS Cut Line= 6
      3164311.38      13879703.5      3163794.18     13879696.69
      3163354.48     13879353.32      3162194.05     13879218.34
      3162002.41     13878731.48      3160384.16     13878655.54
#Sta/Elev= 30
  3315.9   46.19    3334   45.59    3394   45.49    3454   42.89  4006.2   41.49
  4056.2   39.39  4316.2   38.99  4429.4   41.29  4549.4   41.39  4645.4    38.3
    4757   30.95  4800.9   30.17  4880.8    28.2  4937.8   12.14  4945.7    7.33
  4974.4    -.62  5000.1    -.67  5030.9    -.47  5054.4    6.98  5059.2   12.87
  5083.5   21.82  5112.8   37.09  5122.6   36.87  5154.1   33.82  5286.2    34.8
  5527.2   44.19  5757.6   45.29  6233.2   42.79  6707.6   42.59  7705.1   45.79
#Mann= 7 , 1 , 0
  3315.9      .2       0    3334     .14       0  4800.9      .1       0
  4880.8    .035       0  5112.8      .1       0  5122.6     .14       0
  6233.2      .2       0
#XS Ineff= 2 , 0
       0    4867    35.5    5124       0    35.5
Permanent Ineff=
       F       F
Bank Sta=4880.8,5112.8
XS Rating Curve= 0 ,0
Exp/Cntr=0.5,0.3

Type RM Length L Ch R = 1 ,72763.6 ,659.5,769.9,835.7
BEGIN DESCRIPTION:
Cross Section 72763.6-Interpolated
END DESCRIPTION:
XS GIS Cut Line= 6
      3164328.42     13879655.82      3164002.07     13879620.86
      3163722.35     13879492.65      3163419.32     13879201.28
      3162428.65     13878630.18      3159608.13     13878362.12
#Sta/Elev= 30
  3404.2    46.4  4400.1    44.7  4628.6    46.3  4752.2   51.02  4778.6    50.9
  4818.6      46  4868.6    33.3  4908.6      27  4915.3   28.11  4937.5    3.11
  4971.1    3.11  4975.9    6.79  5000.7    -.31  5018.4    4.11  5069.2   24.28
  5098.6    35.4  5118.6    39.3  5156.5    38.4  5266.5    20.9  5346.5    18.5
  5536.5    31.3  5696.1    32.1  5806.1    23.5  5836.1      26  5926.1    23.2
  6046.1    33.5  6076.1    40.1  6136.1    43.2  6559.2    45.1    8441    46.2
#Mann= 6 , 1 , 0
  3404.2      .2       0  3404.2     .08       0  4752.2     .14       0
  4915.3     .04       0  5069.2     .14       0  6559.2      .2       0
Bank Sta=4915.3,5069.2
XS Rating Curve= 0 ,0
Exp/Cntr=0.3,0.1

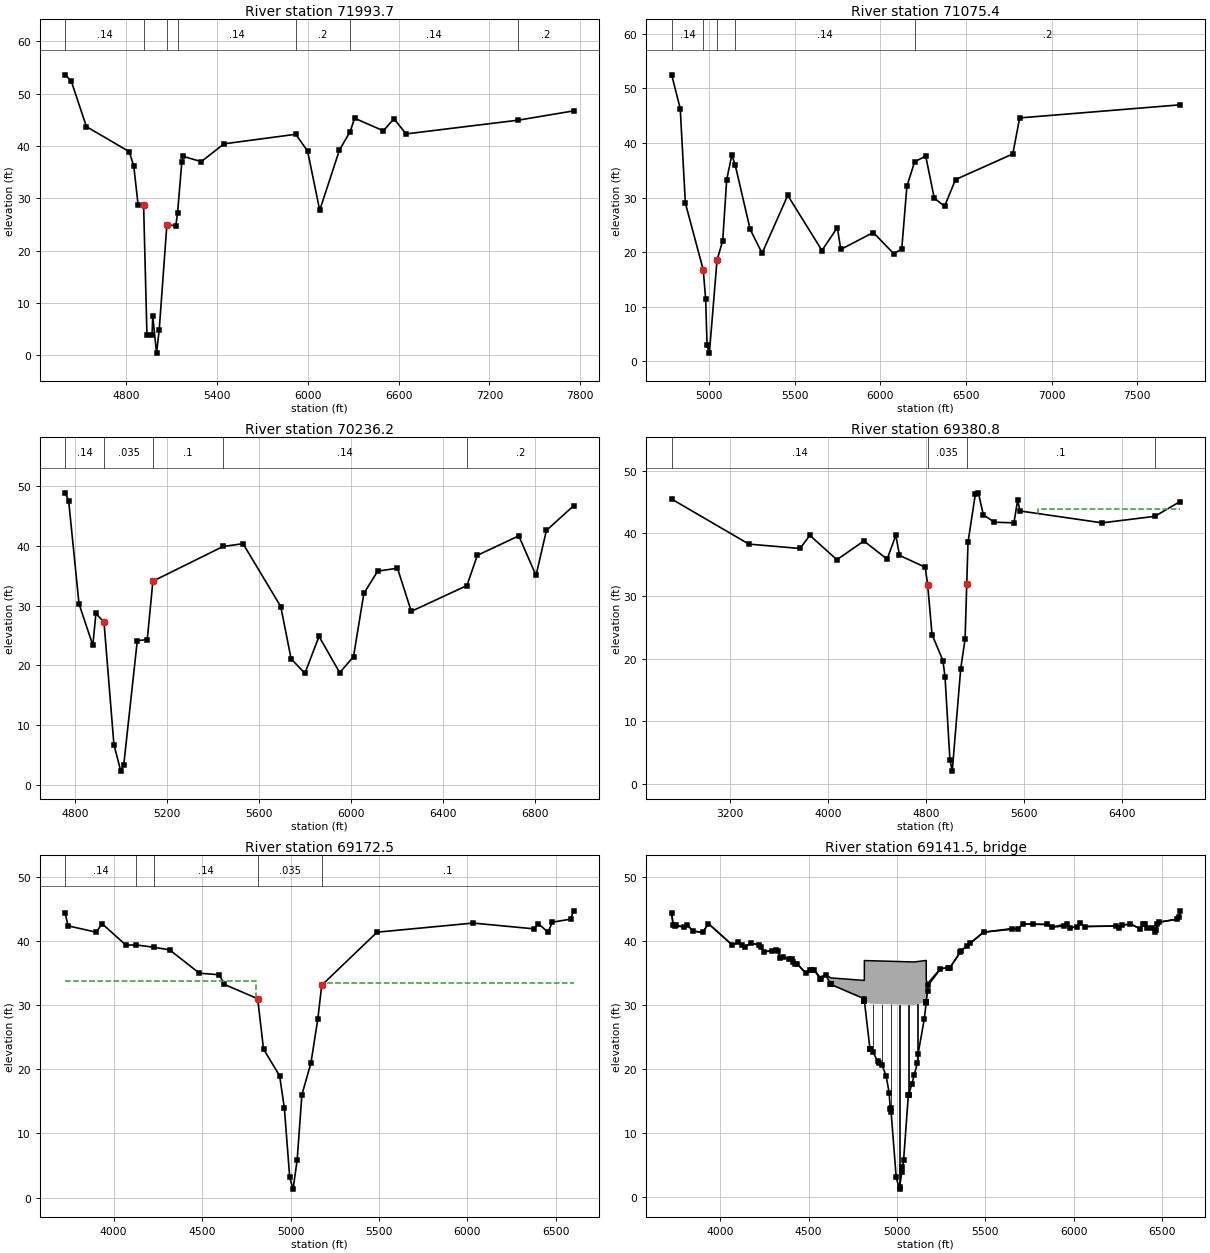
Type RM Length L Ch R = 1 ,71993.7 ,1110.7,918.3,650.6
BEGIN DESCRIPTION:
Cross Section 71993.7
END DESCRIPTION:
XS GIS Cut Line= 6
      3164029.94     13878958.18      3163764.32     13878894.11
       3163629.4     13878458.51      3163216.93     13878258.05
      3162550.04     13878059.53      3161095.84     13877980.23
#Sta/Elev= 30
  4397.5    53.6  4437.5    52.4  4537.5    43.7  4820.7    38.9  4850.7    36.1
  4879.3   28.64  4915.3    28.8  4937.5     3.8  4971.1     3.8  4975.9    7.48
  5000.7     .38  5018.4     4.8  5069.2   24.97    5128    24.7  5139.9   27.27
    5168      37    5178      38  5296.1      37  5446.1    40.4  5920.5   42.23
  5998.8      39  6078.8    27.7  6208.8    39.2  6279.5   42.72  6309.1    45.3
  6499.1    42.9  6569.1    45.2  6649.1    42.3  7390.1   44.93  7755.4    46.7
#Mann= 7 , 1 , 0
  4397.5     .14       0  4915.3    .035       0  5069.2     .08       0
  5139.9     .14       0  5920.5      .2       0  6279.5     .14       0
  7390.1      .2       0
Bank Sta=4915.3,5069.2
XS Rating Curve= 0 ,0
Exp/Cntr=0.3,0.1

Type RM Length L Ch R = 1 ,71075.4 ,747.6,839.2,851.3
BEGIN DESCRIPTION:
Cross Section 71075.4
END DESCRIPTION:
XS GIS Cut Line= 6
       3164020.4     13877746.01      3163653.01     13877719.17
      3162380.86     13877571.51       3162068.5     13877611.26
      3161807.26     13877690.77      3161095.27     13877868.18
#Sta/Elev= 30
  4779.7    52.5  4829.7    46.3  4859.7      29  4964.3   16.75  4978.3   11.37
  4986.6    2.89    5000    1.49  5044.7   18.51  5078.1   22.12  5101.4    33.3
  5131.4    37.8  5151.4   35.93  5238.2    24.2  5308.2    19.8  5458.2    30.4
  5658.2    20.3  5748.2    24.5  5768.2    20.5  5958.2    23.6  6078.2    19.7
  6124.7    20.6  6154.7    32.1    6200   36.57  6264.7    37.6  6314.7    29.9
  6374.7    28.4  6438.9    33.3  6773.8      38  6813.8    44.6  7751.1      47
#Mann= 5 , 1 , 0
  4779.7     .14       0  4964.3    .035       0  5044.7     .08       0
  5151.4     .14       0    6200      .2       0
Bank Sta=4964.3,5044.7
XS Rating Curve= 0 ,0
Exp/Cntr=0.3,0.1

Type RM Length L Ch R = 1 ,70236.2 ,927.1,855.4,827.9
BEGIN DESCRIPTION:
Cross Section 70236.2
END DESCRIPTION:
XS GIS Cut Line= 6
      3164082.07     13877016.37      3163779.99     13876866.71
      3163674.59     13876859.44       3163016.7     13876906.69
      3162715.02     13877030.27      3161945.33     13877149.84
#Sta/Elev= 30
  4758.7   48.88  4773.7   47.54  4818.7   30.28  4878.7   23.34  4892.2   28.67
  4927.3   27.18  4970.4     6.7  5000.2    2.25    5013    3.26    5072   24.12
  5115.3   24.28  5139.8   34.08  5444.8   39.89  5531.5   40.36  5695.5   29.83
  5740.5   21.07  5800.5   18.63  5861.8   24.83  5951.8   18.74  6011.8   21.45
  6056.8   32.04  6116.8   35.76  6202.8   36.25  6262.8   29.02  6504.4   33.34
    6550   38.41    6730   41.67    6805   35.04    6850   42.57    6968    46.7
#Mann= 5 , 1 , 0
  4758.7     .14       0  4927.3    .035       0  5139.8      .1       0
  5444.8     .14       0  6504.4      .2       0
Bank Sta=4927.3,5139.8
XS Rating Curve= 0 ,0
Exp/Cntr=0.3,0.1

Type RM Length L Ch R = 1 ,69380.8 ,207.2,208.3,218.7
BEGIN DESCRIPTION:
Cross Section 69380.8-Interpolated
END DESCRIPTION:
XS GIS Cut Line= 6
      3165243.95     13877611.44      3165024.37     13876813.57
      3164337.44     13876153.88      3164036.39     13876048.36
      3163161.95     13876050.16      3162038.08     13876312.32
#Sta/Elev= 30
  2725.2    45.5  3355.2    38.3  3772.7    37.6  3852.7    39.7  4073.2    35.8
  4293.2    38.8  4483.2    35.9  4554.1    39.7  4584.1    36.5  4794.1    34.6
  4814.3    31.7  4849.5   23.84  4938.4   19.68  4955.8   17.02  4995.5    3.83
  5014.5       2  5083.5   18.36  5119.1   23.08  5132.8    31.9  5143.1    38.6
  5203.1    46.3  5227.8    46.5  5267.8      43  5357.8    41.8  5517.8    41.7
  5547.8    45.3  5567.8    43.6  6237.4    41.7  6667.1   42.74  6872.8    45.1
#Mann= 4 , 1 , 0
  2725.2     .14       0  4814.3    .035       0  5132.8      .1       0
  6667.1     .14       0
#XS Ineff= 2 , 0
       0                  5717.4       0    43.9
Permanent Ineff=
       F       F
Bank Sta=4814.3,5132.8
XS Rating Curve= 0 ,0
Exp/Cntr=0.5,0.3

Type RM Length L Ch R = 1 ,69172.5 ,62,62,62
BEGIN DESCRIPTION:
Upstream Section of Bridge/Culvert/Weir
END DESCRIPTION:
XS GIS Cut Line= 6
      3165123.61     13875766.49       3164543.1     13875880.36
      3164344.56      13875890.3      3163366.83     13875839.41
      3162900.03     13875863.07      3162304.11     13876086.54
#Sta/Elev= 30
  3726.2   44.35  3742.2   42.38  3902.2   41.38  3933.9   42.73  4069.9   39.36
  4125.2   39.41  4229.6   39.03  4316.7   38.63  4484.7   34.99  4596.7   34.75
  4625.5   33.25  4814.3   31.01  4847.4   23.15  4938.4   18.99  4965.2   13.95
  4995.5    3.14  5014.5    1.31  5037.6    5.87  5064.3   16.03  5115.3   20.96
  5154.7    27.9  5176.3   33.11  5489.4   41.39  6032.1   42.81  6376.1   41.91
  6400.1   42.73  6456.1   41.39  6480.1   42.95  6584.1   43.42  6600.1   44.72
#Mann= 5 , 1 , 0
  3726.2     .14       0  4125.2      .1       0  4229.6     .14       0
  4814.3    .035       0  5176.3      .1       0
#XS Ineff= 2 , 0
       0    4806    33.8    5176       0    33.4
Permanent Ineff=
       F       F
Bank Sta=4814.3,5176.3
XS Rating Curve= 0 ,0
Exp/Cntr=0.5,0.3

Type RM Length L Ch R = 3 ,69141.5 ,,,
BEGIN DESCRIPTION:
TIDWELL ROAD
Structure ID: P00-19
END DESCRIPTION:
Bridge Culvert--1,0,-1,-1, 0
Deck Dist Width WeirC Skew NumUp NumDn MinLoCord MaxHiCord MaxSubmerge Is_Ogee
10,42,2.6,0, 60, 60, , , 0.95, 0, 1,1,,
  3726.2  3734.2  3742.2  3798.2  3814.2  3846.2  3902.2  3933.9  4069.9  4101.9
  4141.9  4173.9  4221.9  4245.9  4316.7  4324.7  4340.7  4404.7  4420.7  4436.7
  4484.7  4532.7  4564.7  4596.7  4625.5  4814.3 4815.57 4815.68  4847.4    5098
 5165.27 5165.38  5172.7  5176.3    5246  5298.4  5363.1  5489.4  5682.1  5714.1
  5850.1  5874.1  5960.1  5976.1  6016.1  6032.1  6064.1  6240.1  6256.1  6272.1
  6320.1  6376.1  6400.1  6416.1  6440.1  6456.1  6480.1  6584.1  6592.1  6600.1
   44.33   42.57   42.36   42.17   42.54   41.53   41.36   42.71   39.34   39.77
   39.12   39.69   39.34   38.31   38.61   38.44   37.28   37.27   36.38    36.4
   34.97   35.45   34.38   34.74   34.24   33.84   33.84   36.94   36.92   36.72
   36.96   33.86   33.41   33.47   35.68   35.79   38.49   41.38    41.9   42.65
   42.58   42.16   42.66   42.06   42.22   42.79   42.26   42.34   42.01   42.47
   42.65   41.89   42.71   42.01   42.04   41.37   42.93    43.4   43.67    44.7
   44.32   42.56   42.35   42.16   42.53   41.52   41.35    42.7   39.33   39.76
   39.11   39.68   39.33    38.3    38.6   38.43   37.27   37.26   36.37   36.39
   34.96   35.43   34.12   34.72   33.22   30.98   30.68   30.65   30.21   30.01
   30.42   30.45   32.21   33.08   35.66   35.77   38.47   41.36   41.88   42.63
   42.57   42.15   42.65   42.05   42.21   42.78   42.25   42.33      42   42.46
   42.64   41.88    42.7      42   42.03   41.36   42.92   43.39   43.66   44.69
  3726.2  3734.2  3742.2  3798.2  3814.2  3846.2  3902.2  3933.9  4069.9  4101.9
  4141.9  4173.9  4221.9  4245.9  4316.7  4324.7  4340.7  4404.7  4420.7  4436.7
  4484.7  4532.7  4564.7  4596.7  4625.5  4814.3 4815.57 4815.68  4847.4    5098
 5165.27 5165.38  5172.7  5176.3    5246  5298.4  5363.1  5489.4  5682.1  5714.1
  5850.1  5874.1  5960.1  5976.1  6016.1  6032.1  6064.1  6240.1  6256.1  6272.1
  6320.1  6376.1  6400.1  6416.1  6440.1  6456.1  6480.1  6584.1  6592.1  6600.1
   44.33   42.57   42.36   42.17   42.54   41.53   41.36   42.71   39.34   39.77
   39.12   39.69   39.34   38.31   38.61   38.44   37.28   37.27   36.38    36.4
   34.97   35.45   34.38   34.74   34.24   33.84   33.84   36.94   36.92   36.72
   36.96   33.86   33.41   33.47   35.68   35.79   38.49   41.38    41.9   42.65
   42.58   42.16   42.66   42.06   42.22   42.79   42.26   42.34   42.01   42.47
   42.65   41.89   42.71   42.01   42.04   41.37   42.93    43.4   43.67    44.7
   44.25   42.49   42.28   42.09   42.46   41.45   41.28   42.63   39.26   39.69
   39.04   39.61   39.26   38.23   38.53   38.36    37.2   37.19    36.3   36.32
   34.89   35.36   34.05   34.65   33.15   30.91   30.61   30.58   30.14   29.94
   30.35   30.38   32.14   33.01   35.59    35.7    38.4   41.29   41.81   42.56
    42.5   42.08   42.58   41.98   42.14   42.71   42.18   42.26   41.93   42.39
   42.57   41.81   42.63   41.93   41.96   41.29   42.85   43.32   43.59   44.62
Pier Skew, UpSta & Num, DnSta & Num=  ,4865.2, 2 ,4865.2, 2 , 0 , 0 , 0 ,,
     2.8     2.8
   21.55    31.2
     2.8     2.8
   21.48   31.13
Pier Skew, UpSta & Num, DnSta & Num=  ,4915.9, 2 ,4915.9, 2 , 0 , 0 , 0 ,,
     2.8     2.8
   19.52   31.17
     2.8     2.8
   19.45    31.1
Pier Skew, UpSta & Num, DnSta & Num=  ,4965.3, 2 ,4965.3, 2 , 0 , 0 , 0 ,,
     2.8     2.8
   12.38   31.16
     2.8     2.8
   12.31   31.09
Pier Skew, UpSta & Num, DnSta & Num=  ,5015, 2 ,5015, 2 , 0 , 0 , 0 ,,
     2.8     2.8
     .37   31.13
     2.8     2.8
      .3   31.06
Pier Skew, UpSta & Num, DnSta & Num=  ,5064.3, 2 ,5064.3, 2 , 0 , 0 , 0 ,,
     2.8     2.8
   14.47   31.07
     2.8     2.8
    14.4      31
Pier Skew, UpSta & Num, DnSta & Num=  ,5115.3, 2 ,5115.3, 2 , 0 , 0 , 0 ,,
     2.8     2.8
   19.79   31.08
     2.8     2.8
   19.72   31.01
Abutment Skew #Up #Dn= , 2 , 2
  4815.8  4847.5
   30.58   23.12
  4815.8  4847.5
   30.51   23.05
Abutment Skew #Up #Dn= , 2 , 2
  5066.3 5165.69
   16.01   30.47
  5066.3 5165.69
   15.94    30.4
BR Coef= 1 , 1 , 0 ,1.25, 0 ,,,0.8,0,2,0,
WSPro=,,,, 1 ,,,, 0 ,,,, 0 ,,,,-1 ,-1 ,-1 , 0 , 0 , 0 , 0 , 0
BR U #Sta/Elev= 114
  3726.2   44.32  3734.2   42.56  3742.2   42.35  3750.2   42.49  3798.2   42.16
  3814.2   42.53  3846.2   41.52  3902.2   41.35  3933.9    42.7  4069.9   39.33
  4101.9   39.76  4125.2   39.38  4141.9   39.11  4173.9   39.68  4221.9   39.33
  4229.6      39  4245.9    38.3  4292.7   38.45  4316.7    38.6  4324.7   38.43
  4340.7   37.27  4356.7   37.52  4388.7   37.13  4404.7   37.26  4412.7   36.64
  4420.7   36.37  4436.7   36.39  4484.7   34.96  4508.7    35.4  4517.2   35.41
  4532.7   35.43  4564.7   34.12  4572.7   34.04  4596.7   34.72  4623.3   33.33
  4625.5   33.22  4625.6   33.22  4814.3   30.98 4815.57   30.68 4815.68   30.65
 4815.79   30.63 4815.91    30.6    4816   30.58  4847.4   23.12  4847.5   23.12
  4849.5   23.12  4865.2   22.63  4891.4    21.2  4898.9   21.02  4915.9   20.62
  4938.4   18.96  4955.8    16.3  4962.3   13.72  4965.2   13.92  4966.9   13.31
  4995.5    3.11  5014.5    1.28    5015    1.63  5026.8    3.88  5031.2    4.68
  5037.6    5.84  5064.3      16  5066.2      16  5066.3   16.01  5083.5   17.64
    5098   19.14  5115.3   20.93  5119.1   22.36  5154.7   27.87 5165.16   30.39
 5165.27   30.42 5165.38   30.45 5165.49   30.47  5165.6    30.5  5165.7   30.52
  5172.7   32.21  5176.3   33.08    5246   35.66  5285.8   35.85  5295.3   35.79
  5298.4   35.77  5357.6   38.24  5363.1   38.47  5396.3   39.23  5413.9   39.63
  5489.4   41.36  5650.1   41.93  5682.1   41.88  5714.1   42.63  5766.3   42.61
  5850.1   42.57  5874.1   42.15  5944.1   42.32  5960.1   42.65  5976.1   42.05
  6016.1   42.21  6032.1   42.78  6064.1   42.25  6240.1   42.33  6256.1      42
  6272.1   42.46  6320.1   42.64  6376.1   41.88  6392.1   42.67  6400.1    42.7
  6416.1      42  6440.1   42.03  6456.1   41.36  6464.1   41.65  6472.1   42.57
  6480.1   42.92  6584.1   43.39  6592.1   43.66  6600.1   44.69
BR U #Mann= 5
  3726.2     .14  4125.2      .1  4229.6     .14  4814.3    .035  5176.3      .1
BR U Banks=4814.3,5176.3
BR D #Sta/Elev= 114
  3726.2   44.25  3734.2   42.49  3742.2   42.28  3750.2   42.42  3798.2   42.09
  3814.2   42.46  3846.2   41.45  3902.2   41.28  3933.9   42.63  4069.9   39.26
  4101.9   39.69  4125.2   39.31  4141.9   39.04  4173.9   39.61  4221.9   39.26
  4229.6   38.93  4245.9   38.23  4292.7   38.38  4316.7   38.53  4324.7   38.36
  4340.7    37.2  4356.7   37.45  4388.7   37.06  4404.7   37.19  4412.7   36.57
  4420.7    36.3  4436.7   36.32  4484.7   34.89  4508.7   35.33  4517.2   35.34
  4532.7   35.36  4564.7   34.05  4572.7   33.97  4596.7   34.65  4623.3   33.26
  4625.5   33.15  4625.6   33.15  4814.3   30.91 4815.57   30.61 4815.68   30.58
 4815.79   30.56 4815.91   30.53    4816   30.51  4847.4   23.05  4847.5   23.05
  4849.5   23.05  4865.2   22.56  4891.4   21.13  4898.9   20.95  4915.9   20.55
  4938.4   18.89  4955.8   16.23  4962.3   13.65  4965.2   13.85  4966.9   13.24
  4995.5    3.04  5014.5    1.21    5015    1.56  5026.8    3.81  5031.2    4.61
  5037.6    5.77  5064.3   15.93  5066.2   15.93  5066.3   15.94  5083.5   17.57
    5098   19.07  5115.3   20.86  5119.1   22.29  5154.7    27.8 5165.16   30.32
 5165.27   30.35 5165.38   30.38 5165.49    30.4  5165.6   30.43  5165.7   30.45
  5172.7   32.14  5176.3   33.01    5246   35.59  5285.8   35.78  5295.3   35.72
  5298.4    35.7  5357.6   38.17  5363.1    38.4  5396.3   39.16  5413.9   39.56
  5489.4   41.29  5650.1   41.86  5682.1   41.81  5714.1   42.56  5766.3   42.54
  5850.1    42.5  5874.1   42.08  5944.1   42.25  5960.1   42.58  5976.1   41.98
  6016.1   42.14  6032.1   42.71  6064.1   42.18  6240.1   42.26  6256.1   41.93
  6272.1   42.39  6320.1   42.57  6376.1   41.81  6392.1    42.6  6400.1   42.63
  6416.1   41.93  6440.1   41.96  6456.1   41.29  6464.1   41.58  6472.1    42.5
  6480.1   42.85  6584.1   43.32  6592.1   43.59  6600.1   44.62
BR D #Mann= 5
  3726.2     .14  4125.2      .1  4229.6     .14  4814.3    .035  5176.3      .1
BR D Banks=4814.3,5176.3
BC Design=,, 0 ,, 0 ,,,,,,
BC HTab HWMax=44.72
BC Use User HTab Curves=0
BC User HTab FreeFlow(D)= 0

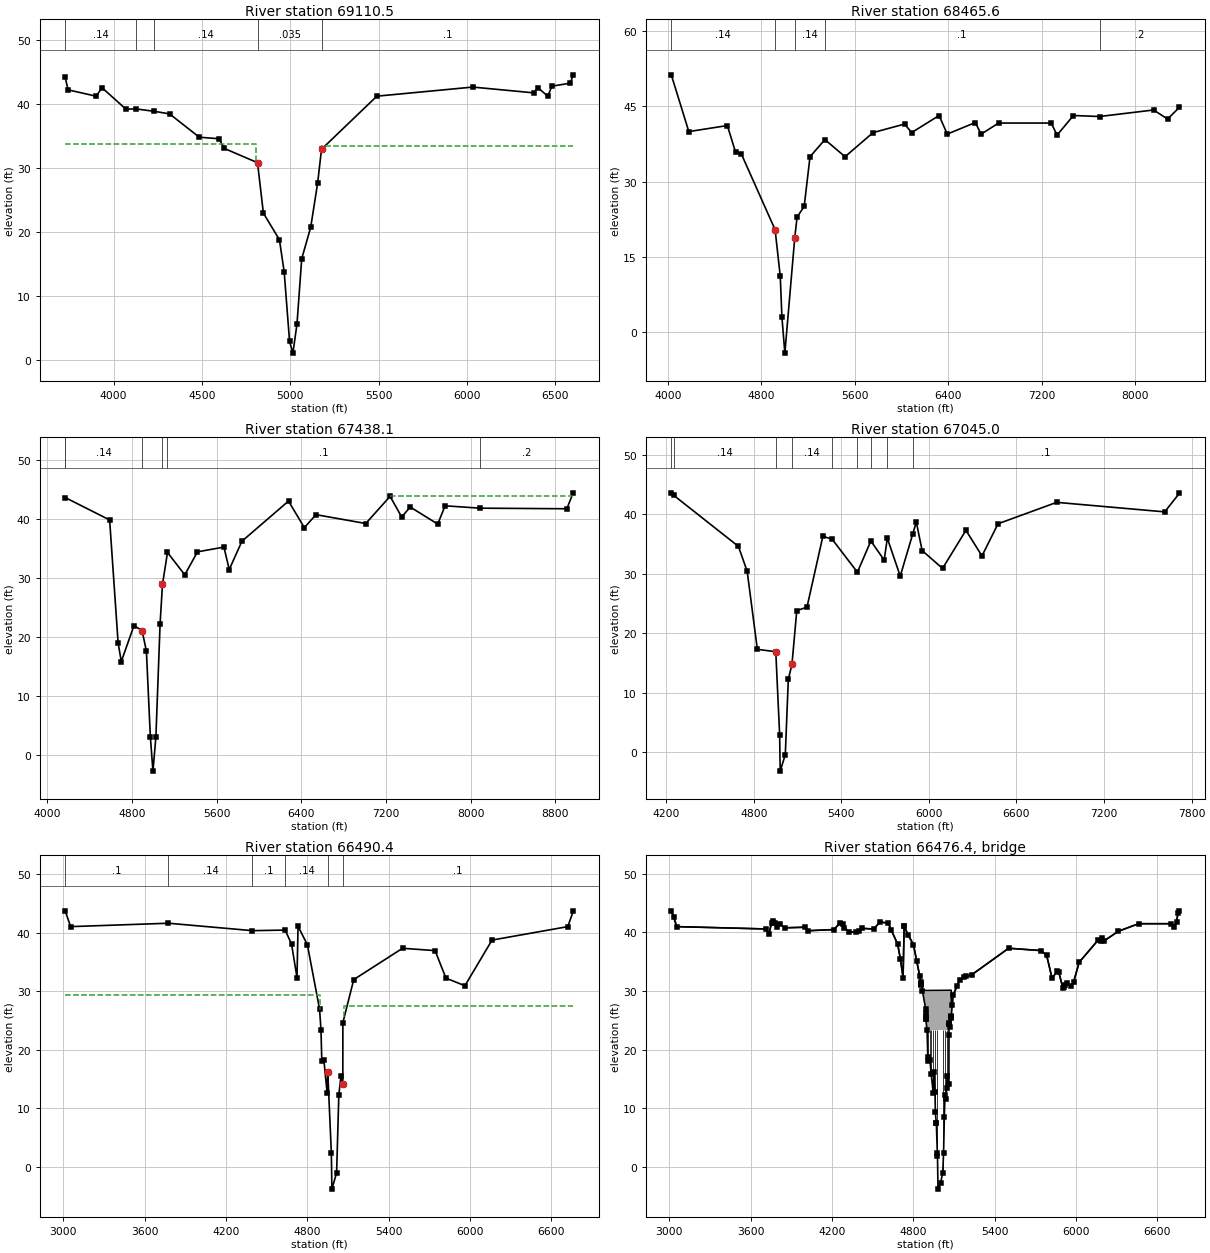
Type RM Length L Ch R = 1 ,69110.5 ,644.9,644.9,644.9
BEGIN DESCRIPTION:
Downstream Section of Bridge/Culvert/Weir
END DESCRIPTION:
XS GIS Cut Line= 6
      3165135.77      13875705.7      3164555.26     13875819.56
      3164356.72      13875829.5      3163378.99     13875778.61
      3162912.19     13875802.27      3162316.27     13876025.74
#Sta/Elev= 30
  3726.2   44.17  3742.2    42.2  3902.2    41.2  3933.9   42.55  4069.9   39.18
  4125.2   39.23  4229.6   38.85  4316.7   38.45  4484.7   34.81  4596.7   34.57
  4625.5   33.07  4814.3   30.83  4847.4   22.97  4938.4   18.81  4965.2   13.77
  4995.5    2.96  5014.5    1.13  5037.6    5.69  5064.3   15.85  5115.3   20.78
  5154.7   27.72  5176.3   32.93  5489.4   41.21  6032.1   42.63  6376.1   41.73
  6400.1   42.55  6456.1   41.21  6480.1   42.77  6584.1   43.24  6600.1   44.54
#Mann= 5 , 1 , 0
  3726.2     .14       0  4125.2      .1       0  4229.6     .14       0
  4814.3    .035       0  5176.3      .1       0
#XS Ineff= 2 , 0
       0    4806    33.8    5176       0    33.4
Permanent Ineff=
       F       F
Bank Sta=4814.3,5176.3
XS Rating Curve= 0 ,0
Exp/Cntr=0.5,0.3

Type RM Length L Ch R = 1 ,68465.6 ,1056.2,1027.5,795.6
BEGIN DESCRIPTION:
Cross Section 68465.6
END DESCRIPTION:
XS GIS Cut Line= 6
      3164780.63     13875456.44      3164207.43     13875364.86
      3164049.62     13875215.82      3163628.79     13875128.14
      3162629.31     13875303.49      3160703.07     13876149.19
#Sta/Elev= 30
  4029.5    51.3  4179.5      40  4509.5    41.2  4579.5    35.9    4630    35.5
    4918   20.47  4962.3   11.19  4976.4    3.09  5001.6   -4.11  5086.4   18.89
  5106.3   22.98    5167    25.1    5217      35  5344.4    38.4  5516.9      35
  5756.9    39.8  6026.9    41.5  6086.9    39.8  6321.7    43.2  6391.7    39.5
  6631.7    41.8  6681.7    39.5  6831.7    41.7  7281.7    41.7  7331.7    39.3
  7471.7    43.2  7694.9      43  8157.8    44.3  8277.8    42.5  8377.8    44.8
#Mann= 5 , 1 , 0
  4029.5     .14       0    4918    .035       0  5086.4     .14       0
  5344.4      .1       0  7694.9      .2       0
#XS Ineff= 2 , 0
       0                  6321.7       0    43.2
Permanent Ineff=
       F       F
Bank Sta=4918,5086.4
XS Rating Curve= 0 ,0
Exp/Cntr=0.3,0.1

Type RM Length L Ch R = 1 ,67438.1 ,603.6,393.1,231.9
BEGIN DESCRIPTION:
Cross Section  67438.1
END DESCRIPTION:
XS GIS Cut Line= 6
      3164681.23     13874085.44      3164288.05     13874232.88
      3164036.85     13874172.81      3163665.51     13874189.19
      3162900.99     13874937.33      3160501.95     13876132.05
#Sta/Elev= 30
  4169.2    43.7  4589.1    39.9  4669.1    19.1  4699.1    15.9  4819.1      22
  4895.6   21.16  4936.5   17.66  4973.8    3.16  4998.4   -2.67  5026.3    3.15
  5065.9   22.33  5088.3   28.97  5135.7   34.39  5299.1    30.6  5419.1    34.5
  5669.1    35.3  5719.1    31.5  5839.1    36.3  6279.1    43.1  6428.8    38.6
  6538.8    40.8  7008.8    39.3  7238.8    43.9  7348.8    40.4  7428.8    42.1
  7688.8    39.2  7758.8    42.3  8087.6    41.9  8908.8    41.8  8968.8    44.5
#Mann= 6 , 1 , 0
  4169.2      .2       0  4169.2     .14       0  4895.6    .035       0
  5088.3     .14       0  5135.7      .1       0  8087.6      .2       0
#XS Ineff= 2 , 0
       0                 7238.58       0    43.9
Permanent Ineff=
       F       F
Bank Sta=4895.6,5088.3
XS Rating Curve= 0 ,0
Exp/Cntr=0.3,0.1

Type RM Length L Ch R = 1 ,67045.0 ,610,554.6,368.3
BEGIN DESCRIPTION:
Cross Section 67045.0-Interpolated
END DESCRIPTION:
XS GIS Cut Line= 5
      3164441.26     13873356.06      3163955.45     13873653.49
      3163664.08     13873968.17      3162382.03      13874842.3
      3161589.97     13875329.72
#Sta/Elev= 30
  4235.2    43.6  4252.3   43.17  4695.2    34.6  4755.2    30.4  4824.8    17.3
 4951.05   16.91 4977.53    2.94  4981.3   -3.16 5016.32    -.37  5036.9   12.26
 5061.91   14.79  5094.8    23.8  5164.8    24.4  5273.7    36.3  5337.1   35.81
  5510.3   30.26  5602.4   35.51  5693.7    32.3  5715.3   35.98  5803.7    29.6
  5889.6   36.71  5913.7    38.7  5953.7    33.9  6093.7    30.9  6253.7    37.3
  6363.7      33  6473.7    38.4  6875.4      42  7615.4    40.4  7715.4    43.5
#Mann= 9 , 1 , 0
  4235.2      .1       0  4252.3     .14       0 4951.05    .035       0
 5061.91     .14       0  5337.1      .1       0  5510.3     .07       0
  5602.4      .1       0  5715.3     .07       0  5889.6      .1       0
#XS Ineff= 2 , 0
       0                  6875.4       0      42
Permanent Ineff=
       F       F
Bank Sta=4951.05,5061.91
XS Rating Curve= 0 ,0
Exp/Cntr=0.5,0.3

Type RM Length L Ch R = 1 ,66490.4 ,28,28,28
BEGIN DESCRIPTION:
Upstream Section of Bridge/Culvert/Weir
END DESCRIPTION:
XS GIS Cut Line= 6
       3164977.8     13872620.26      3163587.61     13873241.83
      3163525.29     13873354.06      3163181.64     13873935.97
      3162422.87     13874540.31      3162039.65      13874776.9
#Sta/Elev= 30
    3014   43.71    3054   41.01  3775.5   41.59  4395.4   40.32    4637   40.42
  4683.9   38.01  4723.9   32.31  4731.7   41.06 4800.33   37.93 4890.61   26.91
 4900.94   23.33 4906.93   18.12 4922.43   18.16  4946.7    12.5 4951.05   16.22
 4977.53    2.25  4981.3   -3.85 5016.32   -1.06 5032.64   12.31  5048.3   15.41
 5061.91    14.1  5062.4    24.6  5142.6   31.96  5502.7   37.31  5742.7   36.91
  5822.7   32.21  5962.7   30.91  6162.7   38.71  6721.4   41.01  6761.4   43.61
#Mann= 6 , 1 , 0
    3014      .1       0  3775.5     .14       0  4395.4      .1       0
    4637     .14       0 4951.05    .035       0 5061.91      .1       0
#XS Ineff= 2 , 0
       0    4891    29.4    5072       0    27.4
Permanent Ineff=
       F       F
Bank Sta=4951.05,5061.91
XS Rating Curve= 0 ,0
Exp/Cntr=0.5,0.3

Type RM Length L Ch R = 3 ,66476.4 ,,,
BEGIN DESCRIPTION:
GOLF COURSE BRIDGE2 - 35 degree skew
Structure ID: P00-18
END DESCRIPTION:
Bridge Culvert--1,0,-1,-1, 0
Deck Dist Width WeirC Skew NumUp NumDn MinLoCord MaxHiCord MaxSubmerge Is_Ogee
10,8,2.6,0, 60, 60, , , 0.95, 0, 1,1,,
    3014    3054    3714    3734    3754    3764    3794    3814    3854    4004
    4024    4214  4257.7  4327.7  4377.7  4417.7  4507.7  4553.9  4613.9  4683.9
  4703.9  4723.9  4731.7 4800.33  4866.8 4890.61 4890.84 4900.94  5062.3  5062.4
 5072.65  5078.6  5079.3 5079.41  5086.7  5092.5  5142.6 5229.85  5502.7  5742.7
  5782.7  5822.7  5862.7  5872.7  5902.7  5932.7  5962.7  5982.7  6022.7  6162.7
  6182.7  6192.7  6202.7  6311.4  6461.4  6701.4  6721.4  6741.4  6751.4  6761.4
    43.7      41    40.6    39.7    41.7      42    40.9    41.4    40.8    40.9
    40.3    40.5    41.6    40.1      40    40.7    40.6    41.8    41.6      38
    35.5    32.3   41.05   37.92   30.14   30.11   30.11    30.1   30.13   30.13
   30.14   30.15   30.13   27.33   27.67   29.26   31.96   32.77   37.31   36.91
   36.11   32.21   33.41   33.21    30.5    31.3    30.9    31.6    34.9    38.7
    38.5      39    38.5    40.2    41.5    41.5      41    41.8    43.3    43.6
    43.7      41    40.6    39.7    41.7      42    40.9    41.4    40.8    40.9
    40.3    40.5    41.6    40.1      40    40.7    40.6    41.8    41.6      38
    35.5    32.3   41.05   37.92   29.99    26.9   25.22   23.32   23.33   24.59
   23.81   25.44   25.63   25.66   27.66   29.25   31.95   32.76    37.3    36.9
    36.1    32.2    33.4    33.2    30.5    31.3    30.9    31.6    34.9    38.7
    38.5      39    38.5    40.2    41.5    41.5      41    41.8    43.3    43.6
    3014    3054    3714    3734    3754    3764    3794    3814    3854    4004
    4024    4214  4257.7  4327.7  4377.7  4417.7  4507.7  4553.9  4613.9  4683.9
  4703.9  4723.9  4731.7 4800.33  4866.8 4890.61 4890.84 4900.94  5062.3  5062.4
 5072.65  5078.6  5079.3 5079.41  5086.7  5092.5  5142.6 5229.85  5502.7  5742.7
  5782.7  5822.7  5862.7  5872.7  5902.7  5932.7  5962.7  5982.7  6022.7  6162.7
  6182.7  6192.7  6202.7  6311.4  6461.4  6701.4  6721.4  6741.4  6751.4  6761.4
    43.7      41    40.6    39.7    41.7      42    40.9    41.4    40.8    40.9
    40.3    40.5    41.6    40.1      40    40.7    40.6    41.8    41.6      38
    35.5    32.3   41.05   37.92   30.14   30.11   30.11    30.1   30.13   30.13
   30.14   30.15   30.13   27.33   27.67   29.26   31.96   32.77   37.31   36.91
   36.11   32.21   33.41   33.21    30.5    31.3    30.9    31.6    34.9    38.7
    38.5      39    38.5    40.2    41.5    41.5      41    41.8    43.3    43.6
   43.66   40.96   40.56   39.66   41.66   41.96   40.86   41.36   40.76   40.86
   40.26   40.46   41.56   40.06   39.96   40.66   40.56   41.76   41.56   37.96
   35.46   32.26   41.01   37.88   29.95   26.86   25.18   23.28   23.29   24.55
   23.77    25.4   25.59   25.62   27.62   29.21   31.91   32.72   37.26   36.86
   36.06   32.16   33.36   33.16   30.46   31.26   30.86   31.56   34.86   38.66
   38.46   38.96   38.46   40.16   41.46   41.46   40.96   41.76   43.26   43.56
Pier Skew, UpSta & Num, DnSta & Num=  ,4906.9, 2 ,4906.9, 2 , 0 , 0 , 0 ,,
       1       1
   17.18   24.29
       1       1
   17.14   24.25
Pier Skew, UpSta & Num, DnSta & Num=  ,4922.4, 2 ,4922.4, 2 , 0 , 0 , 0 ,,
       1       1
   17.02   24.27
       1       1
   16.98   24.23
Pier Skew, UpSta & Num, DnSta & Num=  ,4931.4, 2 ,4931.4, 2 , 0 , 0 , 0 ,,
       1       1
   14.69   24.26
       1       1
   14.65   24.22
Pier Skew, UpSta & Num, DnSta & Num=  ,4946.7, 2 ,4946.7, 2 , 0 , 0 , 0 ,,
       1       1
    11.6   24.25
       1       1
   11.56   24.21
Pier Skew, UpSta & Num, DnSta & Num=  ,4962.2, 2 ,4962.2, 2 , 0 , 0 , 0 ,,
       1       1
    8.12   24.23
       1       1
    8.08   24.19
Pier Skew, UpSta & Num, DnSta & Num=  ,4977.3, 2 ,4977.3, 2 , 0 , 0 , 0 ,,
       1       1
     .83   24.23
       1       1
     .79   24.19
Pier Skew, UpSta & Num, DnSta & Num=  ,5016.3, 2 ,5016.3, 2 , 0 , 0 , 0 ,,
       1       1
   -2.13   24.28
       1       1
   -2.17   24.24
Pier Skew, UpSta & Num, DnSta & Num=  ,5032.6, 2 ,5032.6, 2 , 0 , 0 , 0 ,,
       1       1
   10.85    24.3
       1       1
   10.81   24.26
Pier Skew, UpSta & Num, DnSta & Num=  ,5048.3, 2 ,5048.3, 2 , 0 , 0 , 0 ,,
       1       1
   14.04   24.31
       1       1
      14   24.27
Abutment Skew #Up #Dn= , 2 , 2
  5062.4 5064.54
   24.59   24.44
  5062.4 5064.54
   24.55    24.4
BR Coef= 1 , 1 , 0 ,1.25, 0 ,,,0.8,0,2,0,
WSPro=,,,, 1 ,,,, 0 ,,,, 0 ,,,,-1 ,-1 ,-1 , 0 , 0 , 0 , 0 , 0
BR U #Sta/Elev= 108
    3014    43.7    3034    42.6    3054      41    3714    40.6    3734    39.7
    3754    41.7    3764      42  3775.5   41.58    3794    40.9    3814    41.4
    3854    40.8    4004    40.9    4024    40.3    4214    40.5  4257.7    41.6
  4277.7    41.5  4287.7    40.7  4327.7    40.1  4377.7      40  4395.4   40.31
  4417.7    40.7  4507.7    40.6  4553.9    41.8  4613.9    41.6    4637   40.41
  4683.9      38  4703.9    35.5  4723.9    32.3  4731.7   41.05 4731.78   41.04
 4760.48   39.52 4800.33   37.92  4825.2   35.06  4847.4   32.51  4855.2    31.5
 4857.79   31.16  4857.9   31.15 4858.01   31.13  4858.4   31.08  4866.8   29.99
 4890.61    26.9 4890.69   26.32 4890.78   25.66 4890.84   25.22 4890.94    25.2
 4900.94   23.32 4906.93   18.11 4911.11   18.68 4922.43   18.15 4931.37    15.8
  4946.7   12.49 4951.05   16.21 4959.33   12.82  4962.2    9.26  4968.8    7.47
 4969.17    7.37 4977.29    1.88 4977.53    2.24  4981.3   -3.86 5000.25   -2.85
 5016.32   -1.07 5022.55    2.26 5028.29    8.41 5032.64    12.3  5036.9   11.56
 5045.51   13.38  5048.3    15.4 5061.91   14.09  5062.3   22.45  5062.4   24.59
 5064.34   24.44 5064.45   24.43 5072.65   23.81  5078.6   25.44 5079.19    25.6
  5079.3   25.63 5079.41   25.66  5086.7   27.66  5092.5   29.25  5121.2    30.8
  5142.6   31.95  5176.3   32.36 5189.17   32.51 5229.85   32.76  5502.7    37.3
  5742.7    36.9  5782.7    36.1  5822.7    32.2  5862.7    33.4  5872.7    33.2
  5902.7    30.5    5911   30.72    5921   30.99  5932.7    31.3  5962.7    30.9
  5982.7    31.6  6022.7    34.9  6162.7    38.7  6182.7    38.5  6192.7      39
  6202.7    38.5  6311.4    40.2  6461.4    41.5  6701.4    41.5  6721.4      41
  6741.4    41.8  6751.4    43.3  6761.4    43.6
BR U #Mann= 6
    3014      .1  3775.5     .14  4395.4      .1    4637     .14 4951.05    .035
 5061.91      .1
BR U Banks=4951.05,5061.91
BR D #Sta/Elev= 108
    3014   43.66    3034   42.56    3054   40.96    3714   40.56    3734   39.66
    3754   41.66    3764   41.96  3775.5   41.54    3794   40.86    3814   41.36
    3854   40.76    4004   40.86    4024   40.26    4214   40.46  4257.7   41.56
  4277.7   41.46  4287.7   40.66  4327.7   40.06  4377.7   39.96  4395.4   40.27
  4417.7   40.66  4507.7   40.56  4553.9   41.76  4613.9   41.56    4637   40.37
  4683.9   37.96  4703.9   35.46  4723.9   32.26  4731.7   41.01 4731.78      41
 4760.48   39.48 4800.33   37.88  4825.2   35.02  4847.4   32.47  4855.2   31.46
 4857.79   31.12  4857.9   31.11 4858.01   31.09  4858.4   31.04  4866.8   29.95
 4890.61   26.86 4890.69   26.28 4890.78   25.62 4890.84   25.18 4890.94   25.16
 4900.94   23.28 4906.93   18.07 4911.11   18.64 4922.43   18.11 4931.37   15.76
  4946.7   12.45 4951.05   16.17 4959.33   12.78  4962.2    9.22  4968.8    7.43
 4969.17    7.33 4977.29    1.84 4977.53     2.2  4981.3    -3.9 5000.25   -2.89
 5016.32   -1.11 5022.55    2.22 5028.29    8.37 5032.64   12.26  5036.9   11.52
 5045.51   13.34  5048.3   15.36 5061.91   14.05  5062.3   22.41  5062.4   24.55
 5064.34    24.4 5064.45   24.39 5072.65   23.77  5078.6    25.4 5079.19   25.56
  5079.3   25.59 5079.41   25.62  5086.7   27.62  5092.5   29.21  5121.2   30.76
  5142.6   31.91  5176.3   32.32 5189.17   32.47 5229.85   32.72  5502.7   37.26
  5742.7   36.86  5782.7   36.06  5822.7   32.16  5862.7   33.36  5872.7   33.16
  5902.7   30.46    5911   30.68    5921   30.95  5932.7   31.26  5962.7   30.86
  5982.7   31.56  6022.7   34.86  6162.7   38.66  6182.7   38.46  6192.7   38.96
  6202.7   38.46  6311.4   40.16  6461.4   41.46  6701.4   41.46  6721.4   40.96
  6741.4   41.76  6751.4   43.26  6761.4   43.56
BR D #Mann= 6
    3014      .1  3775.5     .14  4395.4      .1    4637     .14 4951.05    .035
 5061.91      .1
BR D Banks=4951.05,5061.91
BC Design=,, 0 ,, 0 ,,,,,,
BC HTab HWMax=43.71
BC Use User HTab Curves=0
BC User HTab FreeFlow(D)= 0