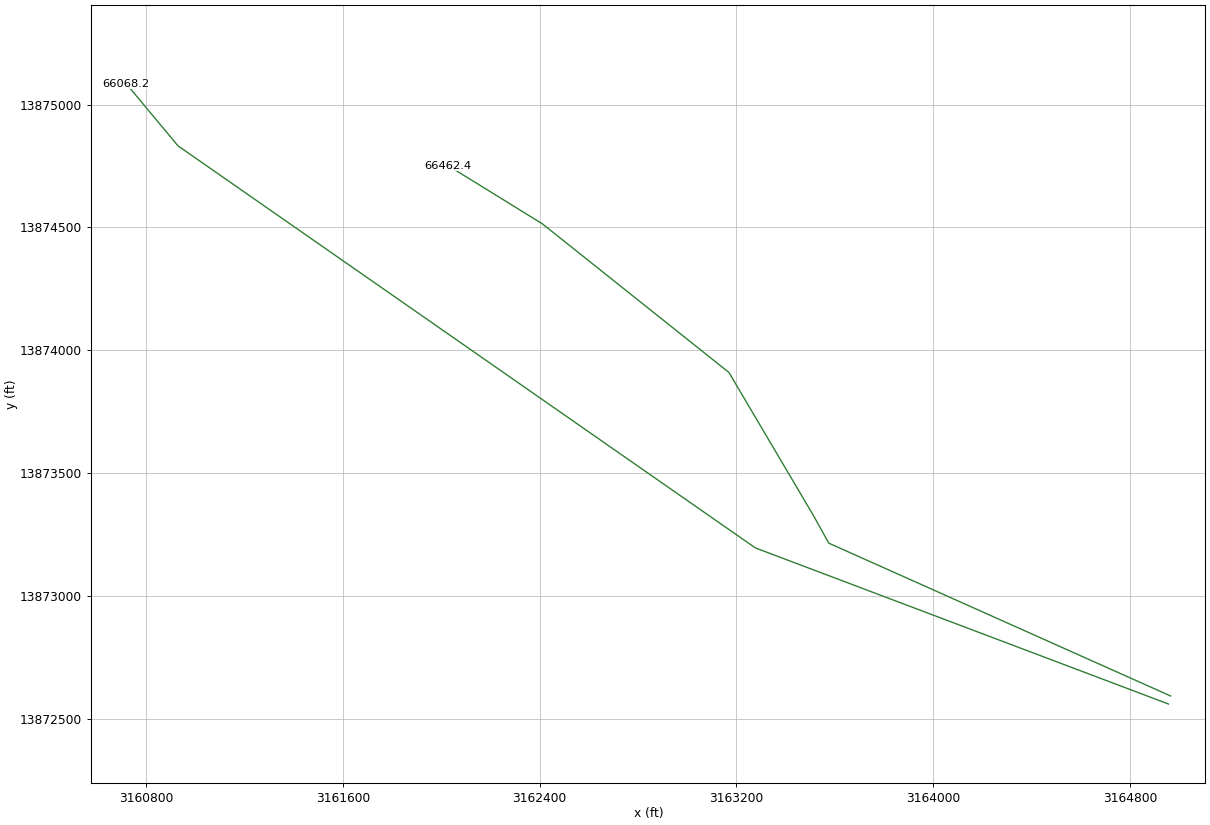
HEC-RAS study P100-00-00.prj: P100-00-00

--- P100-00-00.g01 (geometry) --- (continued)

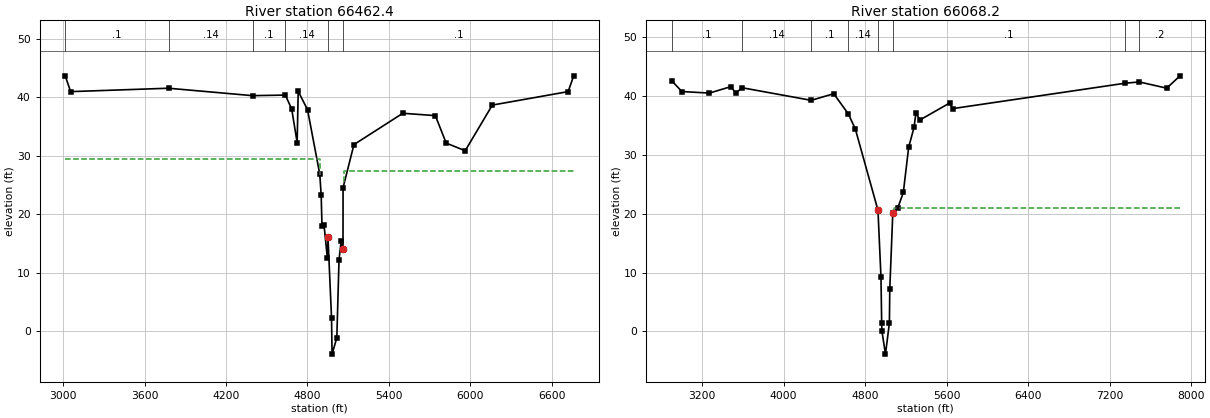
Type RM Length L Ch R = 1 ,66462.4 ,394.2,394.2,394.2
BEGIN DESCRIPTION:
Downstream Section of Bridge/Culvert/Weir
END DESCRIPTION:
XS GIS Cut Line= 6
      3164966.04     13872594.85      3163575.85     13873216.43
      3163513.53     13873328.66      3163169.88     13873910.57
      3162411.11     13874514.91      3162027.88     13874751.49
#Sta/Elev= 30
    3014   43.66    3054   40.96  3775.5   41.54  4395.4   40.27    4637   40.37
  4683.9   37.96  4723.9   32.26  4731.7   41.01 4800.33   37.88 4890.61   26.86
 4900.94   23.28 4906.93   18.07 4922.43   18.11  4946.7   12.45 4951.05   16.17
 4977.53     2.2  4981.3    -3.9 5016.32   -1.11 5032.64   12.26  5048.3   15.36
 5061.91   14.05  5062.4   24.55  5142.6   31.91  5502.7   37.26  5742.7   36.86
  5822.7   32.16  5962.7   30.86  6162.7   38.66  6721.4   40.96  6761.4   43.56
#Mann= 6 , 1 , 0
    3014      .1       0  3775.5     .14       0  4395.4      .1       0
    4637     .14       0 4951.05    .035       0 5061.91      .1       0
#XS Ineff= 2 , 0
       0    4891    29.4    5072       0    27.4
Permanent Ineff=
       F       F
Bank Sta=4951.05,5061.91
XS Rating Curve= 0 ,0
Exp/Cntr=0.5,0.3

Type RM Length L Ch R = 1 ,66068.2 ,33,33,33
BEGIN DESCRIPTION:
Upstream Section of Bridge/Culvert/Weir
END DESCRIPTION:
XS GIS Cut Line= 4
      3164957.22     13872562.19      3163277.45     13873196.98
      3160929.71     13874831.86      3160718.46     13875085.38
#Sta/Elev= 30
  2902.1   42.58  3002.1   40.74  3272.1   40.48  3482.1   41.57  3532.1   40.47
    3592   41.39  4270.9   39.25  4492.1   40.37  4634.6   36.95  4703.7   34.39
  4925.8   20.58  4955.2    9.26  4962.1    1.49  4964.5     .07  4999.3   -3.85
  5037.9    1.42  5041.6    7.15  5071.3   20.15  5120.7   20.98  5174.5    23.6
    5227   31.28  5279.7   34.65  5297.8   37.08  5337.8   35.92  5627.8   38.78
  5657.8   37.84  7352.8   42.16  7489.9   42.37  7758.7   41.31  7888.7   43.41
#Mann= 8 , 1 , 0
  2902.1      .1       0    3592     .14       0  4270.9      .1       0
  4634.6     .14       0  4925.8    .035       0  5071.3      .1       0
  7352.8     .14       0  7489.9      .2       0
#XS Ineff= 2 , 0
       0    4915    21.1    5086       0      21
Permanent Ineff=
       F       F
Bank Sta=4925.8,5071.3
XS Rating Curve= 0 ,0
Exp/Cntr=0.5,0.3