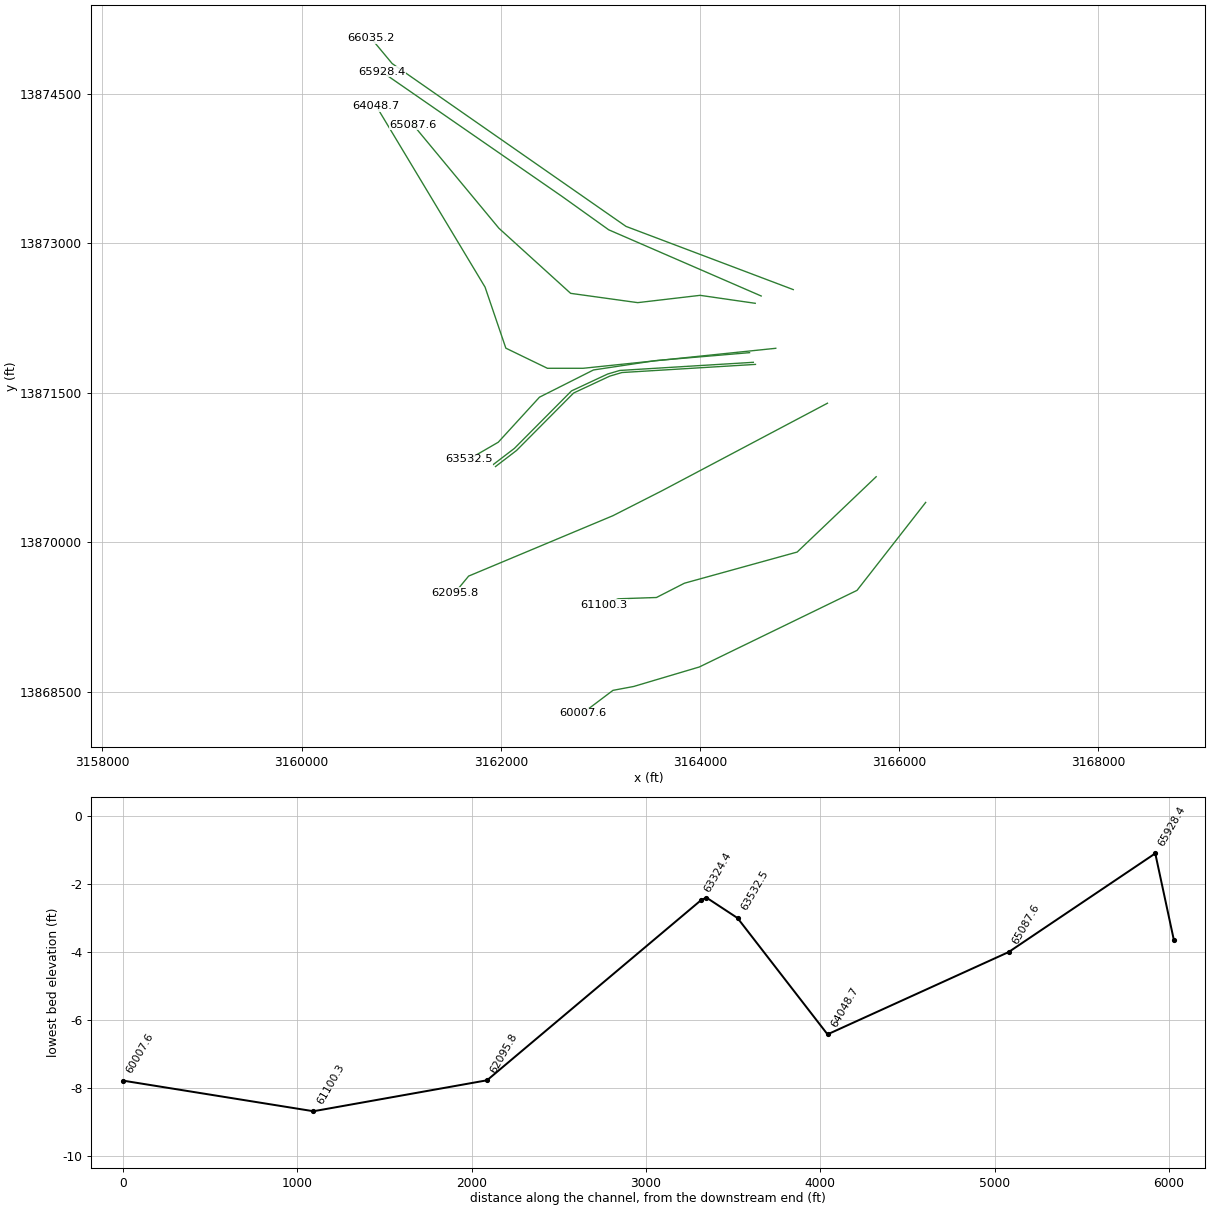
HEC-RAS study P100-00-00.prj: P100-00-00

--- P100-00-00.g01 (geometry) --- (continued)

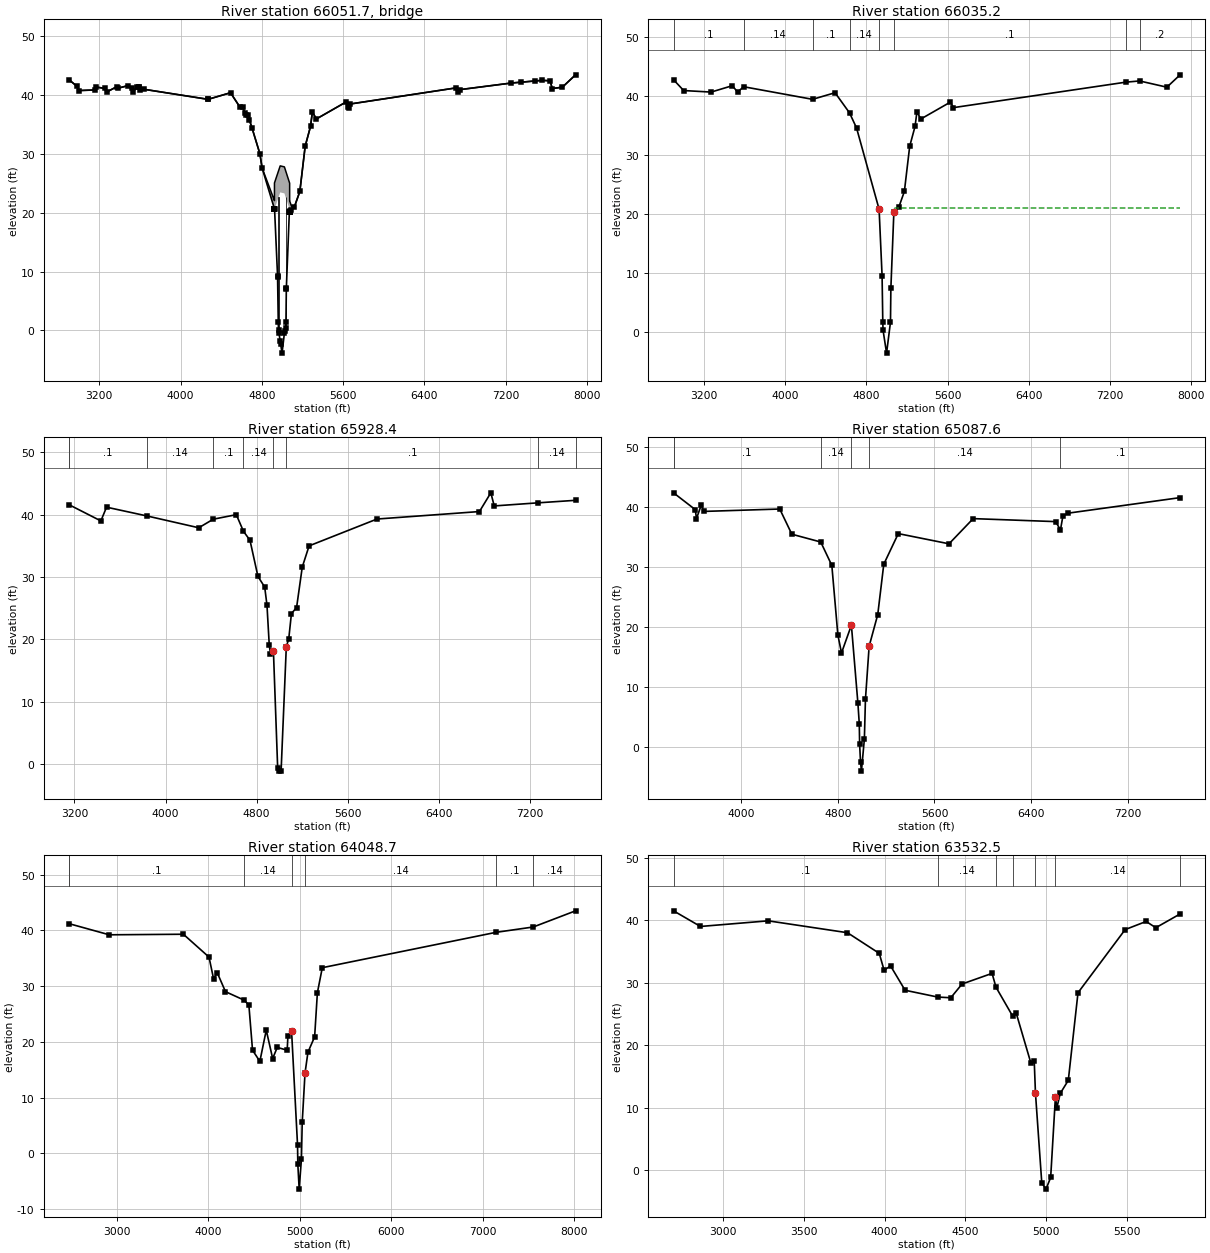
Type RM Length L Ch R = 3 ,66051.7 ,,,
BEGIN DESCRIPTION:
GOLF COURSE BRIDGE1
Structure ID: P00-17
END DESCRIPTION:
Bridge Culvert--1,0,-1,-1, 0
Deck Dist Width WeirC Skew NumUp NumDn MinLoCord MaxHiCord MaxSubmerge Is_Ogee
10,13,2.6,0, 55, 55, , , 0.95, 0, 1,1,,
  2902.1  2982.1  3002.1  3162.1  3172.1  3252.1  3272.1  3372.1  3382.1  3482.1
  3522.1  3532.1  3572.1  3592.1  3602.1  3642.1  4270.9  4492.1  4582.1  4612.1
  4642.1  4662.1  4703.7    4782  4802.6  4924.4 4924.59  4924.7  4925.8  4981.2
  5022.5  5074.2 5074.31 5074.39  5074.5  5092.3  5120.7  5174.5    5227  5279.7
  5297.8  5337.8  5627.8  5647.8  5657.8  5667.8  6707.8  6727.8  6747.8  7257.8
  7558.7  7638.7  7658.7  7758.7  7888.7
   42.58   41.44   40.74   40.84   41.32   41.12   40.48   41.39   41.13   41.57
   41.14   40.47   41.42   41.39   40.81   40.95   39.25   40.37      38   37.88
   36.64   36.61   34.39   29.96   27.62   22.05   22.05   25.05    25.1   27.95
   27.78   25.01   22.01   22.01      22   21.09   20.98    23.6   31.28   34.65
   37.08   35.92   38.78   37.89   37.84   38.45   41.18   40.54   40.89   42.02
   42.47    42.4   41.08   41.31   43.41
   42.58   41.44   40.74   40.84   41.32   41.12   40.48   41.39   41.13   41.57
   41.14   40.47   41.42   41.39   40.81   40.95   39.25   40.37      38   37.88
   36.64   36.61   34.39   29.96   27.62   20.66   20.65   20.64    20.6   23.45
   23.28   20.51   20.51   20.51    20.2    20.5   20.98    23.6   31.28   34.65
   37.08   35.92   38.78   37.89   37.84   38.45   41.18   40.54   40.89   42.02
   42.47    42.4   41.08   41.31   43.41
  2902.1  2982.1  3002.1  3162.1  3172.1  3252.1  3272.1  3372.1  3382.1  3482.1
  3522.1  3532.1  3572.1  3592.1  3602.1  3642.1  4270.9  4492.1  4582.1  4612.1
  4642.1  4662.1  4703.7    4782  4802.6  4924.4 4924.59  4924.7  4925.8  4981.2
  5022.5  5074.2 5074.31 5074.39  5074.5  5092.3  5120.7  5174.5    5227  5279.7
  5297.8  5337.8  5627.8  5647.8  5657.8  5667.8  6707.8  6727.8  6747.8  7257.8
  7558.7  7638.7  7658.7  7758.7  7888.7
   42.58   41.44   40.74   40.84   41.32   41.12   40.48   41.39   41.13   41.57
   41.14   40.47   41.42   41.39   40.81   40.95   39.25   40.37      38   37.88
   36.64   36.61   34.39   29.96   27.62   22.05   22.05   25.05    25.1   27.95
   27.78   25.01   22.01   22.01      22   21.09   20.98    23.6   31.28   34.65
   37.08   35.92   38.78   37.89   37.84   38.45   41.18   40.54   40.89   42.02
   42.47    42.4   41.08   41.31   43.41
   42.54    41.4    40.7    40.8   41.28   41.08   40.44   41.35   41.09   41.53
    41.1   40.43   41.38   41.35   40.77   40.91   39.21   40.33   37.96   37.84
    36.6   36.57   34.35   29.92   27.58   20.62   20.61    20.6   20.56   23.41
   23.24   20.47   20.47   20.47   20.16   20.46   20.94   23.56   31.24   34.61
   37.04   35.88   38.74   37.85    37.8   38.41   41.14    40.5   40.85   41.98
   42.43   42.36   41.04   41.27   43.37
Pier Skew, UpSta & Num, DnSta & Num=  ,4964.5, 2 ,4964.5, 2 , 0 , 0 , 0 ,,
     1.3     1.3
      -1   23.62
     1.3     1.3
   -1.04   23.58
Pier Skew, UpSta & Num, DnSta & Num=  ,5034.6, 2 ,5034.6, 2 , 0 , 0 , 0 ,,
     1.3     1.3
    -.64   23.66
     1.3     1.3
    -.68   23.62
Abutment Skew #Up #Dn= , 2 , 2
  4924.6  4955.3
   20.64    9.15
  4924.6  4955.3
    20.6    9.11
Abutment Skew #Up #Dn= , 2 , 2
  5041.6 5074.59
    7.15   20.51
  5041.6 5074.59
    7.11   20.47
BR Coef= 1 , 1 , 0 ,1.25, 0 ,,,0.8,0,2,0,
WSPro=,,,, 1 ,,,, 0 ,,,, 0 ,,,,-1 ,-1 ,-1 , 0 , 0 , 0 , 0 , 0
BR U #Sta/Elev= 79
  2902.1   42.58  2982.1   41.44  3002.1   40.74  3162.1   40.84  3172.1   41.32
  3252.1   41.12  3272.1   40.48  3372.1   41.39  3382.1   41.13  3482.1   41.57
  3522.1   41.14  3532.1   40.47  3572.1   41.42    3592   41.39  3592.1   41.39
  3602.1   40.81  3642.1   40.95  4270.9   39.25  4272.1   39.25  4492.1   40.37
  4582.1      38  4612.1   37.88  4634.6   36.95  4642.1   36.64  4662.1   36.61
  4678.5   35.69  4703.7   34.39    4782   29.96  4802.6   27.62  4924.4   20.66
 4924.51   20.65 4924.59   20.65  4924.7   20.64  4924.8   20.64 4924.91   20.63
  4925.8   20.58  4955.2    9.26  4955.3    9.15  4962.1    1.49  4964.5     .07
  4968.5    -.38  4981.2   -1.81  4985.1   -2.25  4999.3   -3.85  5022.5    -.46
  5025.3    -.05  5034.6     .39  5037.9    1.42  5041.5       7  5041.6    7.15
  5071.3   20.15 5074.09    20.2  5074.2    20.2 5074.31    20.2 5074.39    20.2
  5074.5    20.2  5074.6   20.21  5092.3    20.5  5120.7   20.98  5174.5    23.6
    5227   31.28  5279.7   34.65  5297.8   37.08  5337.8   35.92  5627.8   38.78
  5647.8   37.89  5657.8   37.84  5667.8   38.45  6707.8   41.18  6727.8   40.54
  6747.8   40.89  7257.8   42.02  7352.8   42.16  7489.9   42.37  7558.7   42.47
  7638.7    42.4  7658.7   41.08  7758.7   41.31  7888.7   43.41
BR U #Mann= 8
  2902.1      .1    3592     .14  4270.9      .1  4634.6     .14  4925.8    .035
  5071.3      .1  7352.8     .14  7489.9      .2
BR U Banks=4925.8,5071.3
BR D #Sta/Elev= 79
  2902.1   42.54  2982.1    41.4  3002.1    40.7  3162.1    40.8  3172.1   41.28
  3252.1   41.08  3272.1   40.44  3372.1   41.35  3382.1   41.09  3482.1   41.53
  3522.1    41.1  3532.1   40.43  3572.1   41.38    3592   41.35  3592.1   41.35
  3602.1   40.77  3642.1   40.91  4270.9   39.21  4272.1   39.21  4492.1   40.33
  4582.1   37.96  4612.1   37.84  4634.6   36.91  4642.1    36.6  4662.1   36.57
  4678.5   35.65  4703.7   34.35    4782   29.92  4802.6   27.58  4924.4   20.62
 4924.51   20.61 4924.59   20.61  4924.7    20.6  4924.8    20.6 4924.91   20.59
  4925.8   20.54  4955.2    9.22  4955.3    9.11  4962.1    1.45  4964.5     .03
  4968.5    -.42  4981.2   -1.85  4985.1   -2.29  4999.3   -3.89  5022.5     -.5
  5025.3    -.09  5034.6     .35  5037.9    1.38  5041.5    6.96  5041.6    7.11
  5071.3   20.11 5074.09   20.16  5074.2   20.16 5074.31   20.16 5074.39   20.16
  5074.5   20.16  5074.6   20.17  5092.3   20.46  5120.7   20.94  5174.5   23.56
    5227   31.24  5279.7   34.61  5297.8   37.04  5337.8   35.88  5627.8   38.74
  5647.8   37.85  5657.8    37.8  5667.8   38.41  6707.8   41.14  6727.8    40.5
  6747.8   40.85  7257.8   41.98  7352.8   42.12  7489.9   42.33  7558.7   42.43
  7638.7   42.36  7658.7   41.04  7758.7   41.27  7888.7   43.37
BR D #Mann= 8
  2902.1      .1    3592     .14  4270.9      .1  4634.6     .14  4925.8    .035
  5071.3      .1  7352.8     .14  7489.9      .2
BR D Banks=4925.8,5071.3
BC Design=,, 0 ,, 0 ,,,,,,
BC HTab HWMax=43.41
BC Use User HTab Curves=0
BC User HTab FreeFlow(D)= 0

Type RM Length L Ch R = 1 ,66035.2 ,106.8,106.8,106.8
BEGIN DESCRIPTION:
Downstream Section of Bridge/Culvert/Weir
END DESCRIPTION:
XS GIS Cut Line= 4
      3164936.96     13872536.14      3163257.19     13873170.94
      3160909.45     13874805.82       3160698.2     13875059.33
#Sta/Elev= 30
  2902.1   42.78  3002.1   40.94  3272.1   40.68  3482.1   41.77  3532.1   40.67
    3592   41.59  4270.9   39.45  4492.1   40.57  4634.6   37.15  4703.7   34.59
  4925.8   20.78  4955.2    9.46  4962.1    1.69  4964.5     .27  4999.3   -3.65
  5037.9    1.62  5041.6    7.35  5071.3   20.35  5120.7   21.18  5174.5    23.8
    5227   31.48  5279.7   34.85  5297.8   37.28  5337.8   36.12  5627.8   38.98
  5657.8   38.04  7352.8   42.36  7489.9   42.57  7758.7   41.51  7888.7   43.61
#Mann= 8 , 1 , 0
  2902.1      .1       0    3592     .14       0  4270.9      .1       0
  4634.6     .14       0  4925.8    .035       0  5071.3      .1       0
  7352.8     .14       0  7489.9      .2       0
#XS Ineff= 2 , 0
       0    4915    21.1    5086       0      21
Permanent Ineff=
       F       F
Bank Sta=4925.8,5071.3
XS Rating Curve= 0 ,0
Exp/Cntr=0.5,0.3

Type RM Length L Ch R = 1 ,65928.4 ,711.7,840.8,937.6
BEGIN DESCRIPTION:
Cross Section 65928.4
END DESCRIPTION:
XS GIS Cut Line= 4
      3164615.09     13872471.88      3163083.77     13873136.64
      3162614.75     13873472.05      3160801.64     13874725.98
#Sta/Elev= 30
  3151.7    41.6  3431.7      39  3481.7    41.2    3840   39.78  4291.7    37.9
  4418.8   39.27  4621.7      40  4684.6   37.33  4741.7    35.9  4811.7    30.1
  4871.1    28.4  4891.1    25.5  4911.1    19.1  4921.6   17.74  4947.7   18.17
    4985    -.58  4996.4    -1.1  5015.3   -1.03  5060.9   18.83  5082.5   20.12
    5106   24.16  5151.1    25.1  5201.1    31.6  5261.1      35  5857.7    39.3
  6757.7    40.5  6857.7    43.5  6887.7    41.4  7275.4    41.9  7602.2    42.3
#Mann= 9 , 1 , 0
  3151.7      .2       0  3151.7      .1       0    3840     .14       0
  4418.8      .1       0  4684.6     .14       0  4947.7    .035       0
  5060.9      .1       0  7275.4     .14       0  7602.2      .2       0
Bank Sta=4947.7,5060.9
XS Rating Curve= 0 ,0
Exp/Cntr=0.3,0.1

Type RM Length L Ch R = 1 ,65087.6 ,1040.3,1038.9,949.1
BEGIN DESCRIPTION:
Cross Section 65087.6-Interpolated
END DESCRIPTION:
XS GIS Cut Line= 6
      3164555.08     13872398.54      3164001.66     13872478.55
      3163374.88     13872405.21      3162701.44     13872498.56
      3161981.31       13873152.      3161119.76     13874191.34
#Sta/Elev= 30
  3440.2    42.4  3620.2    39.6  3630.2    38.1  3670.2    40.4  3690.2    39.3
  4319.4    39.7  4419.4    35.5  4658.6    34.2  4750.4    30.3  4800.4    18.7
  4830.4    15.7  4912.3   20.33  4966.2    7.32  4977.5    3.92  4980.5     .48
  4987.8   -2.49  4995.4      -4  5019.8    1.36  5028.6    7.97  5059.2   16.82
  5130.4    22.1  5180.4    30.5  5300.4    35.6  5720.3    33.9  5920.3    38.1
  6602.7    37.6  6642.5   36.22  6662.7    38.5  6702.7      39  7632.7    41.6
#Mann= 6 , 1 , 0
  3440.2      .2       0  3440.2      .1       0  4658.6     .14       0
  4912.3    .035       0  5059.2     .14       0  6642.5      .1       0
Bank Sta=4912.3,5059.2
XS Rating Curve= 0 ,0
Exp/Cntr=0.3,0.1

Type RM Length L Ch R = 1 ,64048.7 ,197.1,516.2,867.9
BEGIN DESCRIPTION:
Cross Section 64048.7
END DESCRIPTION:
XS GIS Cut Line= 6
      3164761.39     13871946.73      3162826.62     13871745.97
        3162468.     13871745.97       3162050.7      13871948.1
      3161842.05     13872561.02      3160749.88     13874377.98
#Sta/Elev= 30
  2480.2    41.2  2920.2    39.2  3730.1    39.3  4010.1    35.2  4060.1    31.3
  4100.1    32.4  4190.1      29  4393.8   27.48  4445.7    26.6  4485.7    18.5
  4565.7    16.5  4635.7    22.1  4705.7      17  4755.7      19  4864.3    18.5
  4872.5   21.08  4912.3   21.91  4977.5     1.5  4980.5   -1.94  4995.4   -6.42
  5019.8   -1.06  5028.6    5.55  5059.2    14.4  5091.3   18.14  5164.3    20.9
  5194.3    28.8    5248    33.3  7145.6   39.64  7553.2    40.6  8015.4    43.5
#Mann= 7 , 1 , 0
  2480.2      .2       0  2480.2      .1       0  4393.8     .14       0
  4912.3    .035       0  5059.2     .14       0  7145.6      .1       0
  7553.2     .14       0
Bank Sta=4912.3,5059.2
XS Rating Curve= 0 ,0
Exp/Cntr=0.3,0.1

Type RM Length L Ch R = 1 ,63532.5 ,129,178.1,179.2
BEGIN DESCRIPTION:
Cross Section 63532.5-Interpolated
END DESCRIPTION:
XS GIS Cut Line= 6
       3164498.1     13871903.01      3163553.71     13871822.97
      3162930.67     13871729.09      3162388.72     13871455.98
      3161974.78     13871003.63      3161680.33     13870832.94
#Sta/Elev= 30
    2692    41.5  2858.9      39  3278.9    39.9  3769.8      38  3966.7    34.7
  3996.7      32  4036.7    32.7  4126.7    28.8  4329.3   27.71  4409.9    27.6
  4479.9    29.8  4665.8    31.5  4689.8    29.3  4793.4   24.66  4815.8    25.1
  4906.9    17.1  4926.9    17.5  4934.6   12.35  4973.7      -2  4999.8      -3
  5028.8   -1.14  5058.3   11.76  5066.9      10  5088.1    12.3  5138.1    14.4
  5198.1    28.4  5490.3    38.5  5620.3    39.8  5680.3    38.8  5830.7      41
#Mann= 7 , 1 , 0
    2692      .1       0  4329.3     .14       0  4689.8      .1       0
  4793.4     .14       0  4934.6    .035       0  5058.3     .14       0
  5830.7      .2       0
Bank Sta=4934.6,5058.3
XS Rating Curve= 0 ,0
Exp/Cntr=0.5,0.3

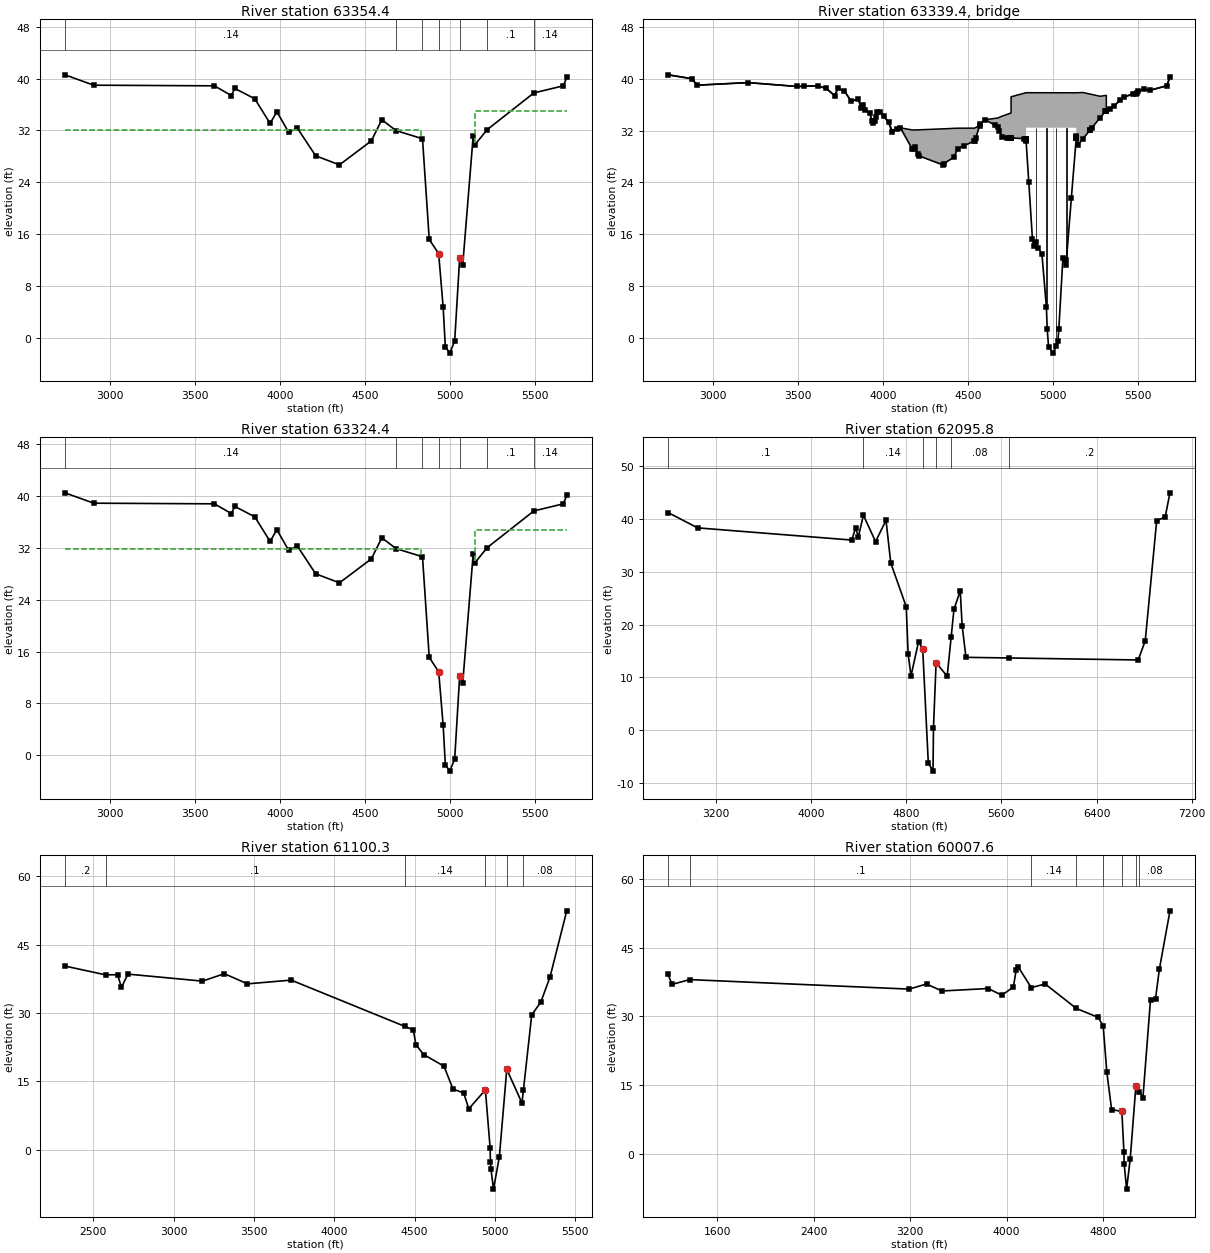
Type RM Length L Ch R = 1 ,63354.4 ,30,30,30
BEGIN DESCRIPTION:
Upstream Section of Bridge/Culvert/Weir
END DESCRIPTION:
XS GIS Cut Line= 6
      3164536.01     13871806.03      3163194.57     13871724.21
      3163072.53     13871688.13      3162709.86     13871518.67
       3162136.6     13870941.54      3161925.14     13870779.91
#Sta/Elev= 30
  2734.6   40.57  2904.6   38.97  3614.6   38.87  3714.6   37.37  3734.6   38.47
  3852.3   36.87  3942.3   33.07  3982.3   34.87  4052.3   31.67  4102.3   32.37
  4210.5   28.07  4350.5   26.67  4538.2   30.37  4600.1   33.63  4683.6   31.96
  4839.4    30.7  4879.1   15.16  4934.6   12.95  4961.1    4.65  4973.7    -1.4
  4999.8    -2.4  5028.8    -.54  5058.3   12.36    5076   11.14  5137.8   31.16
  5149.3   29.81  5219.8    32.1  5495.1   37.78  5668.4   38.87  5688.4   40.17
#Mann= 7 , 1 , 0
  2734.6     .14       0  4683.6      .1       0  4839.4     .14       0
  4934.6    .035       0  5058.3     .14       0  5219.8      .1       0
  5495.1     .14       0
#XS Ineff= 2 , 0
       0    4831      32    5147       0      35
Permanent Ineff=
       F       F
Bank Sta=4934.6,5058.3
XS Rating Curve= 0 ,0
Exp/Cntr=0.5,0.3

Type RM Length L Ch R = 3 ,63339.4 ,,,
BEGIN DESCRIPTION:
GREEN RIVER (LEY) ROAD
Structure ID: P00-16A
END DESCRIPTION:
Bridge Culvert--1,0,-1,-1, 0
Deck Dist Width WeirC Skew NumUp NumDn MinLoCord MaxHiCord MaxSubmerge Is_Ogee
10,10,2.6,0, 60, 60, , , 0.95, 0, 1,1,,
  2734.6  2874.6  2904.6  3204.6  3494.6  3614.6  3664.6  3714.6  3734.6  3772.3
  3812.3  3852.3  3872.3  3882.3  3892.3  3922.3  3932.3  3942.3  3952.3  3962.3
  3982.3  4032.3  4052.3  4082.3  4102.3  4172.3  4180.5  4190.5  4210.5  4350.5
  4418.2  4438.2  4538.2  4568.1  4572.1  4600.1  4674.2  4698.2 4752.99  4753.1
 4841.11  4841.2 5136.79  5136.9  5137.8  5149.3  5175.7  5277.9  5313.8 5313.91
  5359.9  5391.7  5416.2  5470.9  5490.9  5500.9  5538.4  5568.4  5668.4  5688.4
    40.6      40      39    39.4    38.8   38.91   38.51   37.41   38.51   38.11
   36.51   36.91   35.51   35.91   35.21   34.71   33.51   33.11   33.51   34.81
   34.91   33.31   32.04   32.31   32.41   32.09   32.09   32.09   32.11   32.26
   32.34   32.36   32.37   32.78   33.07   33.67   33.93    34.2   34.71   37.21
   37.84   37.84   37.83   37.83   37.83   37.84   37.87   37.29   37.43   35.05
   35.74   36.68   37.11    37.7    37.6    38.1    38.4    38.2    38.9    40.2
    40.6      40      39    39.4    38.8    38.9    38.5    37.4    38.5    38.1
    36.5    36.9    35.5    35.9    35.2    34.7    33.5    33.1    33.5    34.8
    34.9    33.3    31.7    32.3    32.4    29.1    29.1    29.5    28.1    26.7
    27.9    29.2    30.4   32.73   33.06   33.66   32.62   31.01   30.86   30.86
    30.6   32.44   32.43    30.9   31.19   29.84    30.7      34   35.04   35.04
   35.74   36.68   37.11    37.7    37.6    38.1    38.4    38.2    38.9    40.2
  2734.6  2874.6  2904.6  3204.6  3494.6  3614.6  3664.6  3714.6  3734.6  3772.3
  3812.3  3852.3  3872.3  3882.3  3892.3  3922.3  3932.3  3942.3  3952.3  3962.3
  3982.3  4032.3  4052.3  4082.3  4102.3  4172.3  4180.5  4190.5  4210.5  4350.5
  4418.2  4438.2  4538.2  4568.1  4572.1  4600.1  4674.2  4698.2 4752.99  4753.1
 4841.11  4841.2 5136.79  5136.9  5137.8  5149.3  5175.7  5277.9  5313.8 5313.91
  5359.9  5391.7  5416.2  5470.9  5490.9  5500.9  5538.4  5568.4  5668.4  5688.4
    40.6      40      39    39.4    38.8   38.91   38.51   37.41   38.51   38.11
   36.51   36.91   35.51   35.91   35.21   34.71   33.51   33.11   33.51   34.81
   34.91   33.31   32.04   32.31   32.41   32.09   32.09   32.09   32.11   32.26
   32.34   32.36   32.37   32.78   33.07   33.67   33.93    34.2   34.71   37.21
   37.84   37.84   37.83   37.83   37.83   37.84   37.87   37.29   37.43   35.05
   35.74   36.68   37.11    37.7    37.6    38.1    38.4    38.2    38.9    40.2
   40.54   39.94   38.94   39.34   38.74   38.84   38.44   37.34   38.44   38.04
   36.44   36.84   35.44   35.84   35.14   34.64   33.44   33.04   33.44   34.74
   34.84   33.24   31.64   32.24   32.34   29.04   29.04   29.44   28.04   26.64
   27.84   29.14   30.34   32.67      33    33.6   32.56   30.95    30.8    30.8
   30.54   32.38   32.37   30.84   31.13   29.78   30.64   33.94   34.98   34.98
   35.68   36.62   37.05   37.64   37.54   38.04   38.34   38.14   38.84   40.14
Pier Skew, UpSta & Num, DnSta & Num=  ,4900.4, 2 ,4900.4, 2 , 0 , 0 , 0 ,,
     2.4     2.4
   13.69   33.44
     2.4     2.4
   13.63   33.38
Pier Skew, UpSta & Num, DnSta & Num=  ,4961.1, 2 ,4961.1, 2 , 0 , 0 , 0 ,,
     2.4     2.4
    2.83   33.44
     2.4     2.4
    2.77   33.38
Pier Skew, UpSta & Num, DnSta & Num=  ,5018.8, 2 ,5018.8, 2 , 0 , 0 , 0 ,,
     2.4     2.4
   -2.39   33.43
     2.4     2.4
   -2.45   33.37
Pier Skew, UpSta & Num, DnSta & Num=  ,5079, 2 ,5079, 2 , 0 , 0 , 0 ,,
     2.4     2.4
    10.7   33.43
     2.4     2.4
   10.64   33.37
BR Coef= 1 , 1 , 0 ,1.25, 0 ,,,0.8,0,2,0,
WSPro=,,,, 1 ,,,, 0 ,,,, 0 ,,,,-1 ,-1 ,-1 , 0 , 0 , 0 , 0 , 0
BR U #Sta/Elev= 104
  2734.6    40.6  2874.6      40  2904.6      39  3204.6    39.4  3494.6    38.8
  3537.2   38.84  3614.6    38.9  3664.6    38.5  3714.6    37.4  3734.6    38.5
  3772.3    38.1  3812.3    36.5  3852.3    36.9  3872.3    35.5  3882.3    35.9
  3892.3    35.2  3922.3    34.7  3932.3    33.5  3942.3    33.1  3952.3    33.5
  3957.2   34.14  3962.3    34.8  3982.3    34.9  4002.3    34.2  4032.3    33.3
  4052.3    31.7  4082.3    32.3  4102.3    32.4  4172.3    29.1  4180.5    29.1
  4190.5    29.5  4205.9   28.42  4210.5    28.1  4350.5    26.7  4358.2    26.9
  4418.2    27.9  4438.2    29.2  4473.3   29.62  4533.3   30.34  4538.2    30.4
  4545.6    30.9  4568.1   32.73  4572.1   33.06  4600.1   33.66  4657.2   32.86
  4674.2   32.62  4683.6   31.99  4698.2   31.01  4726.9   30.92    4742   30.88
 4752.99   30.86  4753.1   30.86 4753.21   30.86  4831.9   30.74  4839.4   30.73
  4840.8   30.73    4841   30.65 4841.11    30.6  4841.2   30.57  4841.8   30.32
  4857.3   24.03  4879.1   15.19  4885.8    14.2  4900.4   14.78  4912.1   13.87
  4934.6   12.98  4961.1    4.68  4965.7    1.43  4973.7   -1.37  4999.8   -2.37
  5018.8   -1.32  5028.8    -.51  5034.4    1.42  5058.3   12.39    5076   11.17
    5079   12.06  5108.1   21.65  5136.7   30.84 5136.79   30.87  5136.9    30.9
    5137   30.93  5137.8   31.19  5149.3   29.84  5175.7    30.7  5217.3   32.05
  5219.8   32.13  5227.3   32.37  5277.9      34  5307.3   34.94 5313.69   35.04
  5313.8   35.04 5313.91   35.04  5333.2   35.33  5359.9   35.74  5391.7   36.68
  5416.2   37.11  5470.9    37.7  5490.9    37.6  5495.1   37.81  5500.9    38.1
  5538.4    38.4  5568.4    38.2  5668.4    38.9  5688.4    40.2
BR U #Mann= 7
  2734.6     .14  4683.6      .1  4839.4     .14  4934.6    .035  5058.3     .14
  5219.8      .1  5495.1     .14
BR U Banks=4934.6,5058.3
BR D #Sta/Elev= 104
  2734.6   40.54  2874.6   39.94  2904.6   38.94  3204.6   39.34  3494.6   38.74
  3537.2   38.78  3614.6   38.84  3664.6   38.44  3714.6   37.34  3734.6   38.44
  3772.3   38.04  3812.3   36.44  3852.3   36.84  3872.3   35.44  3882.3   35.84
  3892.3   35.14  3922.3   34.64  3932.3   33.44  3942.3   33.04  3952.3   33.44
  3957.2   34.08  3962.3   34.74  3982.3   34.84  4002.3   34.14  4032.3   33.24
  4052.3   31.64  4082.3   32.24  4102.3   32.34  4172.3   29.04  4180.5   29.04
  4190.5   29.44  4205.9   28.36  4210.5   28.04  4350.5   26.64  4358.2   26.84
  4418.2   27.84  4438.2   29.14  4473.3   29.56  4533.3   30.28  4538.2   30.34
  4545.6   30.84  4568.1   32.67  4572.1      33  4600.1    33.6  4657.2    32.8
  4674.2   32.56  4683.6   31.93  4698.2   30.95  4726.9   30.86    4742   30.82
 4752.99    30.8  4753.1    30.8 4753.21    30.8  4831.9   30.68  4839.4   30.67
  4840.8   30.67    4841   30.59 4841.11   30.54  4841.2   30.51  4841.8   30.26
  4857.3   23.97  4879.1   15.13  4885.8   14.14  4900.4   14.72  4912.1   13.81
  4934.6   12.92  4961.1    4.62  4965.7    1.37  4973.7   -1.43  4999.8   -2.43
  5018.8   -1.38  5028.8    -.57  5034.4    1.36  5058.3   12.33    5076   11.11
    5079      12  5108.1   21.59  5136.7   30.78 5136.79   30.81  5136.9   30.84
    5137   30.87  5137.8   31.13  5149.3   29.78  5175.7   30.64  5217.3   31.99
  5219.8   32.07  5227.3   32.31  5277.9   33.94  5307.3   34.88 5313.69   34.98
  5313.8   34.98 5313.91   34.98  5333.2   35.27  5359.9   35.68  5391.7   36.62
  5416.2   37.05  5470.9   37.64  5490.9   37.54  5495.1   37.75  5500.9   38.04
  5538.4   38.34  5568.4   38.14  5668.4   38.84  5688.4   40.14
BR D #Mann= 7
  2734.6     .14  4683.6      .1  4839.4     .14  4934.6    .035  5058.3     .14
  5219.8      .1  5495.1     .14
BR D Banks=4934.6,5058.3
BC Design=,, 0 ,, 0 ,,,,,,
BC HTab HWMax=40.57
BC Use User HTab Curves=0
BC User HTab FreeFlow(D)= 0

Type RM Length L Ch R = 1 ,63324.4 ,1228.6,1228.6,1228.6
BEGIN DESCRIPTION:
Downstream Section of Bridge/Culvert/Weir
END DESCRIPTION:
XS GIS Cut Line= 6
       3164557.5     13871785.09      3163216.05     13871703.27
      3163094.01     13871667.19      3162731.34     13871497.73
      3162158.08      13870920.6      3161946.63     13870758.98
#Sta/Elev= 30
  2734.6    40.5  2904.6    38.9  3614.6    38.8  3714.6    37.3  3734.6    38.4
  3852.3    36.8  3942.3      33  3982.3    34.8  4052.3    31.6  4102.3    32.3
  4210.5      28  4350.5    26.6  4538.2    30.3  4600.1   33.56  4683.6   31.89
  4839.4   30.63  4879.1   15.09  4934.6   12.88  4961.1    4.58  4973.7   -1.47
  4999.8   -2.47  5028.8    -.61  5058.3   12.29    5076   11.07  5137.8   31.09
  5149.3   29.74  5219.8   32.03  5495.1   37.71  5668.4    38.8  5688.4    40.1
#Mann= 7 , 1 , 0
  2734.6     .14       0  4683.6      .1       0  4839.4     .14       0
  4934.6    .035       0  5058.3     .14       0  5219.8      .1       0
  5495.1     .14       0
#XS Ineff= 2 , 0
       0    4831    31.8    5147       0    34.8
Permanent Ineff=
       F       F
Bank Sta=4934.6,5058.3
XS Rating Curve= 0 ,0
Exp/Cntr=0.5,0.3

Type RM Length L Ch R = 1 ,62095.8 ,997.7,995.5,867.1
BEGIN DESCRIPTION:
Cross Section 62095.8
END DESCRIPTION:
XS GIS Cut Line= 5
      3165280.35     13871395.19      3163616.86     13870515.27
      3163126.56     13870265.85      3161676.99     13869659.13
      3161539.42     13869492.59
#Sta/Elev= 30
  2797.8   41.22  3045.8   38.32  4341.8   36.01  4373.8   38.29  4397.8   36.67
  4439.6   40.72  4541.8   35.72  4629.8   39.75  4669.8   31.66  4799.7   23.38
  4815.7    14.5  4839.7   10.25  4903.7   16.79  4938.3   15.36  4985.2   -6.18
    5025   -7.77  5028.6     .33  5050.8   12.76    5144   10.22  5177.1   17.57
    5201   22.87  5253.8   26.41  5269.8   19.79  5301.8   13.79  5662.9   13.67
  6749.8   13.29  6809.2   16.92  6905.2   39.62  6977.2   40.45  7017.2   44.96
#Mann= 6 , 1 , 0
  2797.8      .1       0  4439.6     .14       0  4938.3    .035       0
  5050.8     .12       0  5177.1     .08       0  5662.9      .2       0
Bank Sta=4938.3,5050.8
XS Rating Curve= 0 ,0
Exp/Cntr=0.3,0.1

Type RM Length L Ch R = 1 ,61100.3 ,1102.1,1092.7,1058.1
BEGIN DESCRIPTION:
Cross Section 61100.3
END DESCRIPTION:
XS GIS Cut Line= 6
      3165769.52     13870656.92      3164976.04     13869900.64
       3163843.8     13869587.73      3163563.42     13869444.29
      3163178.72     13869431.25       3163038.8     13869372.05
#Sta/Elev= 30
    2324   40.32  2577.3   38.39    2652   38.41    2676   35.62    2716   38.55
    3180   37.01    3316   38.64  3460.2   36.41  3732.2   37.23  4439.5   27.06
  4492.1   26.29  4508.1   23.05  4556.1   20.89  4682.8   18.32  4738.8   13.32
  4805.4   12.42  4837.4    8.96  4940.4   13.12  4970.2     .28  4971.4   -2.62
    4975   -4.22  4990.9   -8.68  5027.6   -1.52  5073.5   17.64  5168.2   10.23
  5177.1   13.08  5228.7   29.58  5285.8   32.44  5342.7   37.92  5446.7   52.45
#Mann= 6 , 1 , 0
    2324      .2       0  2577.3      .1       0  4439.5     .14       0
  4940.4    .035       0  5073.5     .12       0  5177.1     .08       0
Bank Sta=4940.4,5073.5
XS Rating Curve= 0 ,0
Exp/Cntr=0.3,0.1

Type RM Length L Ch R = 1 ,60007.6 ,1174,1126.4,990.9
BEGIN DESCRIPTION:
Cross Section 60007.6
END DESCRIPTION:
XS GIS Cut Line= 6
      3166266.72     13870399.04      3165577.33     13869515.98
      3163993.76     13868746.61      3163335.21       13868551.
      3163126.56     13868511.88      3162819.95     13868280.67
#Sta/Elev= 30
  1190.6   39.21  1222.6   37.02  1369.7   38.07  3190.9   35.99  3334.9   37.11
  3462.9   35.58  3846.9   36.12  3958.9   34.67  4054.9   36.39  4079.4   40.24
  4095.4   40.87  4203.7   36.32  4319.4   37.11  4578.5   31.75  4758.7   29.81
  4800.7   27.94  4830.7   17.86  4870.7    9.62  4955.7    9.23  4972.6     .44
  4974.6   -2.18  4995.1   -7.78  5025.3    -1.1  5071.9   14.77    5101    13.5
  5130.5   12.21  5193.4   33.67    5235   33.89    5267   40.36    5355   53.12
#Mann= 8 , 1 , 0
  1190.6      .2       0  1369.7      .1       0  4203.7     .14       0
  4578.5      .1       0  4800.7     .14       0  4955.7    .035       0
  5071.9     .12       0    5101     .08       0
Bank Sta=4955.7,5071.9
XS Rating Curve= 0 ,0
Exp/Cntr=0.3,0.1