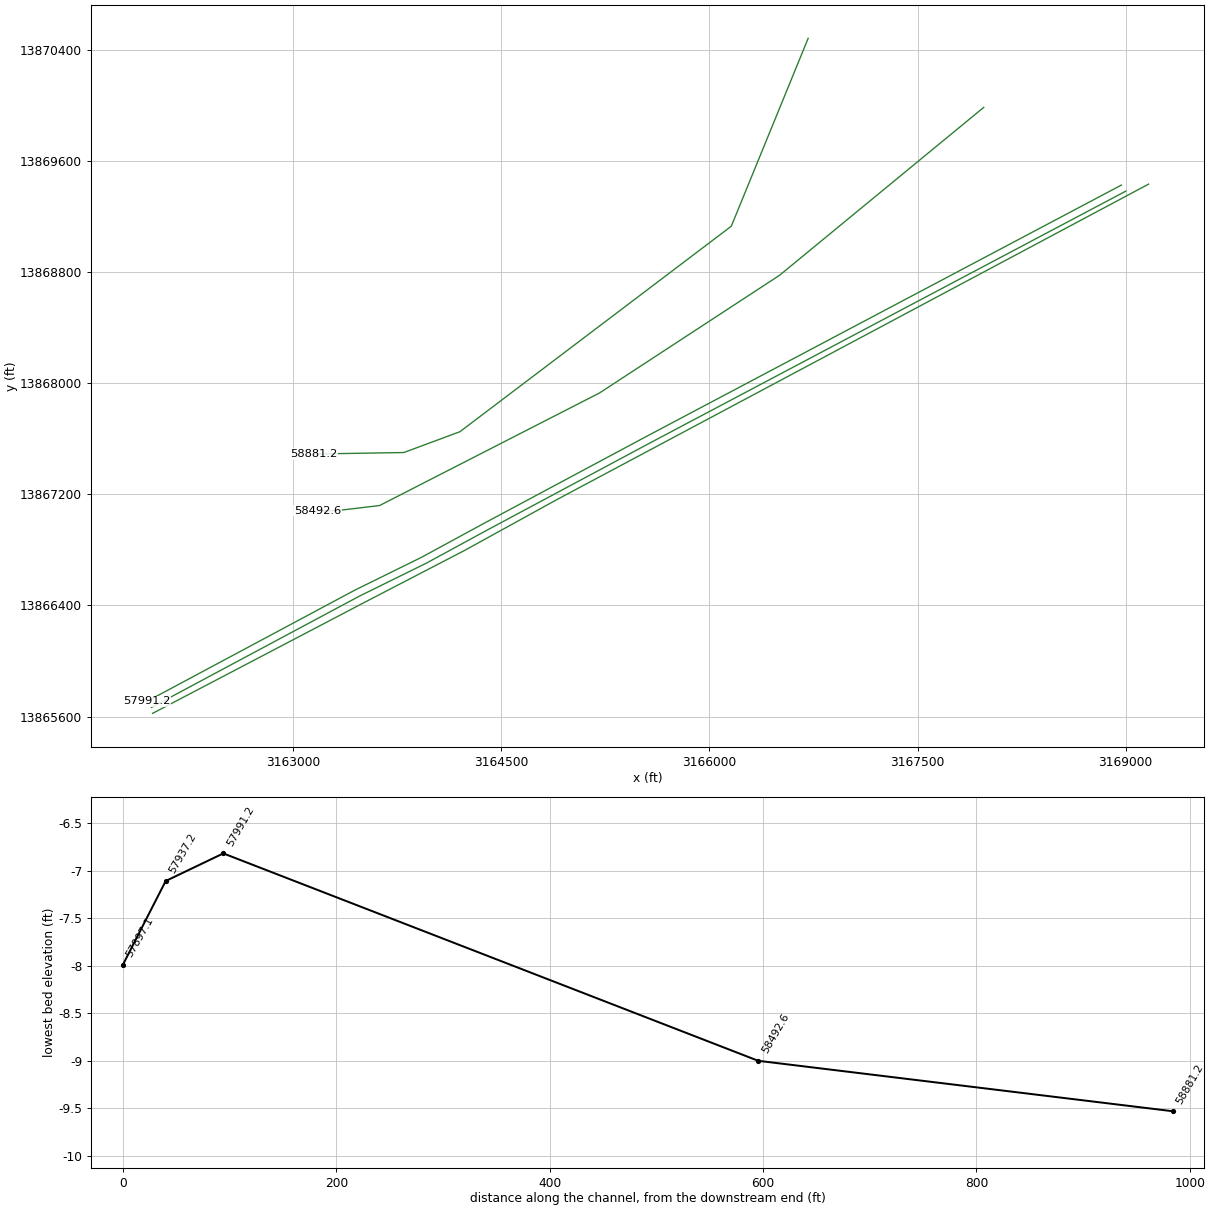
HEC-RAS study P100-00-00.prj: P100-00-00

--- P100-00-00.g01 (geometry) --- (continued)

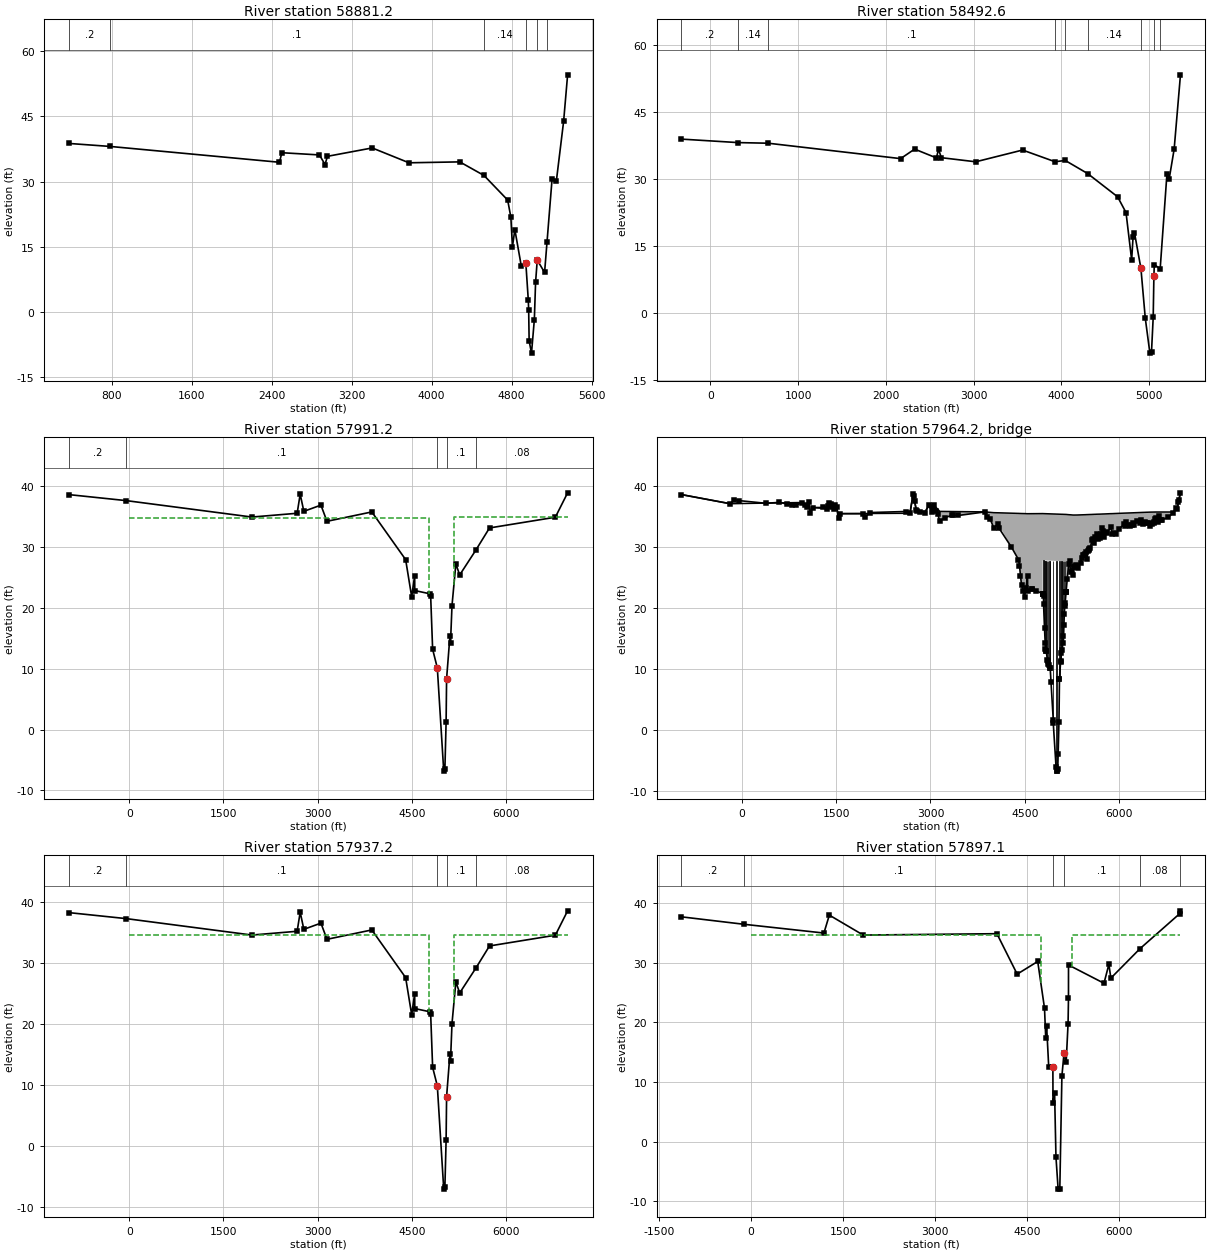
Type RM Length L Ch R = 1 ,58881.2 ,295.9,388.6,405.9
BEGIN DESCRIPTION:
Cross Section 58881.2
END DESCRIPTION:
XS GIS Cut Line= 5
      3166711.77     13870483.35      3166157.89     13869130.62
      3164202.42     13867651.19      3163798.15     13867501.22
      3163150.22      13867490.6
#Sta/Elev= 30
   367.1   38.77   780.2   38.08  2476.8   34.43  2500.8   36.63  2876.8   36.12
  2932.8   33.91  2956.8    35.8  3404.8   37.73  3772.8   34.31  4280.9   34.52
  4523.6   31.39  4760.1   25.73  4792.1   21.82  4808.1   14.96  4832.1   18.93
  4896.1   10.59  4941.8   11.33  4966.8    2.64  4970.5     .32  4975.1   -6.71
  4998.8   -9.53  5027.3   -1.79  5039.6    6.76  5056.2    11.9  5129.7    9.05
    5154   16.04  5204.9   30.67  5248.1   30.23  5320.1   43.84  5360.1   54.57
#Mann= 6 , 1 , 0
   367.1      .2       0   780.2      .1       0  4523.6     .14       0
  4941.8    .035       0  5056.2     .12       0    5154     .08       0
Bank Sta=4941.8,5056.2
XS Rating Curve= 0 ,0
Exp/Cntr=0.3,0.1

Type RM Length L Ch R = 1 ,58492.6 ,439.9,501.4,529.6
BEGIN DESCRIPTION:
Cross Section 58492.6-Interpolated
END DESCRIPTION:
XS GIS Cut Line= 6
      3167976.96     13869986.11      3166505.81     13868777.45
      3165208.55     13867930.22      3163623.45     13867119.61
      3163311.58     13867082.48      3163175.64     13867082.48
#Sta/Elev= 30
    -328   38.94   316.6   38.16   659.8   38.02  2167.9   34.57  2327.9    36.7
  2575.9   34.73  2599.9   36.66  2631.9   34.78  3023.9   33.86  3557.4   36.49
  3927.6   33.87  4043.1   34.16    4298   31.23  4639.8   26.02  4735.8   22.47
  4799.8   11.86  4815.8   16.99  4831.8   17.99  4905.4    9.97  4954.8   -1.14
  5007.5      -9    5026   -8.68  5045.2    -.99  5053.1     8.2  5057.8   10.84
  5124.6    9.87  5201.8   31.15  5227.8    30.1  5283.8   36.68  5355.8   53.34
#Mann= 9 , 1 , 0
    -328      .2       0   316.6     .14       0   659.8      .1       0
  3927.6     .14       0  4043.1      .1       0    4298     .14       0
  4905.4    .035       0  5053.1     .12       0  5124.6     .08       0
Bank Sta=4905.4,5053.1
XS Rating Curve= 0 ,0
Exp/Cntr=0.5,0.3

Type RM Length L Ch R = 1 ,57991.2 ,54,54,54
BEGIN DESCRIPTION:
Upstream Section of Bridge/Culvert/Weir
END DESCRIPTION:
XS GIS Cut Line= 6
      3168969.09     13869426.83      3165559.84     13867624.28
      3164374.28     13866990.56      3163924.97     13866746.54
      3163444.68     13866510.26      3161948.23     13865710.43
#Sta/Elev= 30
  -964.4   38.62   -47.4   37.63    1954   34.93    2674   35.55    2722   38.69
  2780.5   35.87  3052.5   36.89  3148.5   34.23  3862.7   35.77    4401   27.94
    4497   21.85    4545   25.31  4546.5   22.85  4783.8   22.33  4799.5   21.94
  4830.8    13.2  4905.4   10.15  5007.5   -6.82    5026    -6.5  5045.2    1.19
  5053.1    8.38  5106.5   15.42  5115.5   14.29  5139.1   20.39  5200.4   27.21
    5262   25.42  5518.4   29.49  5736.2   33.14  6784.2    34.9  6979.7   38.91
#Mann= 5 , 1 , 0
  -964.4      .2       0   -47.4      .1       0  4905.4    .035       0
  5053.1      .1       0  5518.4     .08       0
#XS Ineff= 2 , 0
       0    4775    34.8    5169       0    34.9
Permanent Ineff=
       F       F
Bank Sta=4905.4,5053.1
XS Rating Curve= 0 ,0
Exp/Cntr=0.5,0.3

Type RM Length L Ch R = 3 ,57964.2 ,,,
BEGIN DESCRIPTION:
SOUTHERN PACIFIC RAILROAD
Structure ID: P00-16
END DESCRIPTION:
Bridge Culvert--1,0,-1,-1, 0
Deck Dist Width WeirC Skew NumUp NumDn MinLoCord MaxHiCord MaxSubmerge Is_Ogee
10,34,2.6,0, 60, 60, , , 0.95, 0, 1,1,,
  -964.4  -188.4   955.6  1035.6  1059.6  1083.6    1130    1346    1378    1506
    1538    1554    2674    2722  2780.5  2916.5  2972.5  3020.5  3052.5  3148.5
  3862.7  4006.7  4078.7    4401    4449    4497    4545  4546.5 4785.21  4785.3
 5159.29  5159.4  5200.4    5214    5230    5262    5278    5342  5472.2  5488.2
  5568.2  5608.2  5656.2  5696.2  5736.2  5768.2  5872.2  5888.2  5952.2  6120.2
  6176.2  6344.2  6496.2  6592.2  6624.2  6640.2  6688.2  6864.2  6928.2  6979.7
   38.66   37.16   37.36   36.66   37.43   35.68   36.53   36.36   37.26   36.58
   34.87   35.53   35.59   38.73   35.92    35.9   36.91    35.9   36.94    35.9
   35.82   35.69   35.67   35.57   35.55   35.54   35.52   35.52   35.54   35.54
    35.4    35.4   35.36   35.35   35.34   35.31    35.3   35.31   35.36   35.37
    35.4   35.42   35.44   35.45   35.47   35.48   35.53   35.53   35.56   35.63
   35.65   35.72   35.78    35.8    35.8    35.8    35.8    35.8   36.37   38.95
   38.66   37.16   37.36   36.66   37.43   35.68   36.53   36.36   37.26   36.58
   34.87   35.53   35.59   38.73   35.91   35.68    36.9   35.83   36.93   34.27
   35.81   33.19   33.86   27.98   23.81   21.89   25.35   22.89   22.33   27.84
    27.7   22.72   27.25   27.69   25.95   25.46   26.73   26.54   29.26   28.08
   31.13   30.74   32.19   31.47   33.18   31.75   33.37   32.24   32.24   34.18
   33.45   34.54   33.58   34.86   34.16   35.13   34.49   35.64   36.36   38.95
  -964.4  -188.4   955.6  1035.6  1059.6  1083.6    1130    1346    1378    1506
    1538    1554    2674    2722  2780.5  2916.5  2972.5  3020.5  3052.5  3148.5
  3862.7  4006.7  4078.7    4401    4449    4497    4545  4546.5 4785.21  4785.3
 5159.29  5159.4  5200.4    5214    5230    5262    5278    5342  5472.2  5488.2
  5568.2  5608.2  5656.2  5696.2  5736.2  5768.2  5872.2  5888.2  5952.2  6120.2
  6176.2  6344.2  6496.2  6592.2  6624.2  6640.2  6688.2  6864.2  6928.2  6979.7
   38.66   37.16   37.36   36.66   37.43   35.68   36.53   36.36   37.26   36.58
   34.87   35.53   35.59   38.73   35.92    35.9   36.91    35.9   36.94    35.9
   35.82   35.69   35.67   35.57   35.55   35.54   35.52   35.52   35.54   35.54
    35.4    35.4   35.36   35.35   35.34   35.31    35.3   35.31   35.36   35.37
    35.4   35.42   35.44   35.45   35.47   35.48   35.53   35.53   35.56   35.63
   35.65   35.72   35.78    35.8    35.8    35.8    35.8    35.8   36.37   38.95
   38.55   37.05   37.25   36.55   37.32   35.57   36.42   36.25   37.15   36.47
   34.76   35.42   35.48   38.62    35.8   35.57   36.79   35.72   36.82   34.16
    35.7   33.08   33.75   27.87    23.7   21.78   25.24   22.78   22.22   27.73
   27.59   22.61   27.14   27.58   25.84   25.35   26.62   26.43   29.15   27.97
   31.02   30.63   32.08   31.36   33.07   31.64   33.26   32.13   32.13   34.07
   33.34   34.43   33.47   34.75   34.05   35.02   34.38   35.53   36.25   38.84
Pier Skew, UpSta & Num, DnSta & Num=  ,4799.5, 2 ,4799.5, 2 , 0 , 0 , 0 ,,
       1       1
   19.91   28.85
       1       1
    19.8   28.74
Pier Skew, UpSta & Num, DnSta & Num=  ,4815.5, 2 ,4815.5, 2 , 0 , 0 , 0 ,,
       1       1
   15.58   28.87
       1       1
   15.47   28.76
Pier Skew, UpSta & Num, DnSta & Num=  ,4830.8, 2 ,4830.8, 2 , 0 , 0 , 0 ,,
       1       1
   12.23   28.88
       1       1
   12.12   28.77
Pier Skew, UpSta & Num, DnSta & Num=  ,4843.5, 2 ,4843.5, 2 , 0 , 0 , 0 ,,
       1       1
   11.92   28.89
       1       1
   11.81   28.78
Pier Skew, UpSta & Num, DnSta & Num=  ,4860.6, 2 ,4860.6, 2 , 0 , 0 , 0 ,,
       1       1
   10.48   28.91
       1       1
   10.37    28.8
Pier Skew, UpSta & Num, DnSta & Num=  ,4873.7, 2 ,4873.7, 2 , 0 , 0 , 0 ,,
       1       1
   10.04   28.92
       1       1
    9.93   28.81
Pier Skew, UpSta & Num, DnSta & Num=  ,4894.4, 2 ,4894.4, 2 , 0 , 0 , 0 ,,
       1       1
    9.58   28.94
       1       1
    9.47   28.83
Pier Skew, UpSta & Num, DnSta & Num=  ,4905.5, 2 ,4905.5, 2 , 0 , 0 , 0 ,,
       4       4
    8.84   28.95
       4       4
    8.73   28.84
Pier Skew, UpSta & Num, DnSta & Num=  ,4954.7, 2 ,4954.7, 2 , 0 , 0 , 0 ,,
       4       4
    -.23   28.94
       4       4
    -.34   28.83
Pier Skew, UpSta & Num, DnSta & Num=  ,5007.3, 2 ,5007.3, 2 , 0 , 0 , 0 ,,
       4       4
   -7.75   28.92
       4       4
   -7.86   28.81
Pier Skew, UpSta & Num, DnSta & Num=  ,5053.6, 2 ,5053.6, 2 , 0 , 0 , 0 ,,
       4       4
    6.05   28.87
       4       4
    5.94   28.76
Pier Skew, UpSta & Num, DnSta & Num=  ,5070.5, 2 ,5070.5, 2 , 0 , 0 , 0 ,,
       1       1
   10.01   28.84
       1       1
     9.9   28.73
Pier Skew, UpSta & Num, DnSta & Num=  ,5085.6, 2 ,5085.6, 2 , 0 , 0 , 0 ,,
       1       1
   11.58   28.81
       1       1
   11.47    28.7
Pier Skew, UpSta & Num, DnSta & Num=  ,5100.7, 2 ,5100.7, 2 , 0 , 0 , 0 ,,
       1       1
   12.13   28.78
       1       1
   12.02   28.67
Pier Skew, UpSta & Num, DnSta & Num=  ,5115.4, 2 ,5115.4, 2 , 0 , 0 , 0 ,,
       1       1
   13.41   28.75
       1       1
    13.3   28.64
Pier Skew, UpSta & Num, DnSta & Num=  ,5129.9, 2 ,5129.9, 2 , 0 , 0 , 0 ,,
       1       1
   17.84   28.73
       1       1
   17.73   28.62
Pier Skew, UpSta & Num, DnSta & Num=  ,5144.3, 2 ,5144.3, 2 , 0 , 0 , 0 ,,
       1       1
   19.87   28.71
       1       1
   19.76    28.6
BR Coef= 1 , 1 , 0 ,1.25, 0 ,,,0.8,0,2,0,
WSPro=,,,, 1 ,,,, 0 ,,,, 0 ,,,,-1 ,-1 ,-1 , 0 , 0 , 0 , 0 , 0
BR U #Sta/Elev= 183
  -964.4   38.66  -188.4   37.16  -124.4   37.75   -47.4   37.67   379.6   37.23
   595.6   37.38   723.6    37.1   795.6   36.97   851.6   36.88   955.6   37.36
  1003.6   37.03  1035.6   36.66  1059.6   37.43  1083.6   35.68    1130   36.53
    1290   36.54    1346   36.36    1362   36.84    1378   37.26    1410   37.08
    1434    36.7    1458   36.26    1474   36.98    1506   36.58    1538   34.87
    1554   35.53    1930   35.52    1954   34.97    2042   35.71    2610   35.88
    2674   35.59    2722   38.73    2738   38.35  2749.2   37.59    2770   36.17
  2780.5   35.91  2836.5   35.87  2916.5   35.68  2972.5    36.9  3020.5   35.83
  3036.5    36.6  3052.5   36.93  3092.5   35.98  3116.5    35.4  3148.5   34.27
  3228.5   34.88  3348.5   35.27  3359.2   35.27  3444.5   35.23  3862.7   35.81
  3894.7   35.03  3950.7   34.63  4006.7   33.19  4078.7   33.86  4094.7   33.09
    4289   30.02    4401   27.98    4417      27    4433   25.31    4449   23.81
    4473   22.86    4497   21.89    4521   23.25    4545   25.35  4546.5   22.89
  4610.5   23.21  4613.7   23.19  4678.8   22.88  4783.8   22.37 4785.21   22.33
  4785.3   22.33  4785.4   22.33  4799.5   21.98  4800.1   20.69  4815.5   16.68
  4826.9   14.35  4830.8   13.24  4843.3   12.96  4843.5   12.96  4860.6   11.49
  4873.7   11.25  4874.8   10.79  4894.4    10.6  4905.4   10.19  4905.5   10.19
  4919.2     7.8  4954.7    1.59  4954.8    1.08  4999.2   -6.13  5007.3   -6.75
  5007.5   -6.78    5026   -6.46  5032.2   -3.98  5045.2    1.23  5053.1    8.42
  5053.6    8.42  5070.5   11.09  5073.8   11.24  5085.6   12.64  5100.7   13.15
  5106.5   15.46  5115.5   14.33  5124.5   17.25  5129.9      19  5139.1   20.43
  5144.3   20.92  5159.2   22.69 5159.29    22.7  5159.4   22.72  5176.4   24.74
  5200.4   27.25    5214   27.69    5230   25.95    5246   26.04    5262   25.46
    5278   26.73  5287.5   26.84    5294   26.92    5310   27.02    5326   26.93
    5342   26.54    5390   27.43    5406   28.29    5430   28.76    5446   28.66
    5462   28.89  5472.2   29.26  5488.2   28.08  5512.2   29.39  5518.4   29.53
  5528.2   29.75  5544.2   29.89  5568.2   31.13  5584.2   31.35  5608.2   30.74
  5624.2   31.64  5656.2   32.19  5672.2   31.38  5696.2   31.47  5720.2   32.18
  5736.2   33.18  5752.2   32.62  5768.2   31.75  5800.2   32.54  5816.2   32.36
  5872.2   33.37  5888.2   32.24  5920.2    32.3  5952.2   32.24  6008.2   33.08
  6088.2   33.79  6104.2   33.55  6120.2   34.18  6152.2   33.61  6176.2   33.45
  6200.2   33.68  6216.2   34.06  6240.2   33.66  6288.2    34.3  6328.2   33.91
  6344.2   34.54  6376.2    33.9  6392.2   33.91  6416.2   34.13  6448.2   33.99
  6472.2   34.01  6496.2   33.58  6528.2   33.77  6552.9   34.06  6560.2   34.14
  6576.2   34.67  6592.2   34.86  6624.2   34.16  6640.2   35.13  6664.2   34.52
  6688.2   34.49  6784.2   34.94  6864.2   35.64  6904.2   36.53  6928.2   36.36
  6944.2   37.48  6949.6    37.7  6979.7   38.95
BR U #Mann= 5
  -964.4      .2   -47.4      .1  4905.4    .035  5053.1      .1  5518.4     .08
BR U Banks=4905.4,5053.1
BR D #Sta/Elev= 183
  -964.4   38.55  -188.4   37.05  -124.4   37.64   -47.4   37.56   379.6   37.12
   595.6   37.27   723.6   36.99   795.6   36.86   851.6   36.77   955.6   37.25
  1003.6   36.92  1035.6   36.55  1059.6   37.32  1083.6   35.57    1130   36.42
    1290   36.43    1346   36.25    1362   36.73    1378   37.15    1410   36.97
    1434   36.59    1458   36.15    1474   36.87    1506   36.47    1538   34.76
    1554   35.42    1930   35.41    1954   34.86    2042    35.6    2610   35.77
    2674   35.48    2722   38.62    2738   38.24  2749.2   37.48    2770   36.06
  2780.5    35.8  2836.5   35.76  2916.5   35.57  2972.5   36.79  3020.5   35.72
  3036.5   36.49  3052.5   36.82  3092.5   35.87  3116.5   35.29  3148.5   34.16
  3228.5   34.77  3348.5   35.16  3359.2   35.16  3444.5   35.12  3862.7    35.7
  3894.7   34.92  3950.7   34.52  4006.7   33.08  4078.7   33.75  4094.7   32.98
    4289   29.91    4401   27.87    4417   26.89    4433    25.2    4449    23.7
    4473   22.75    4497   21.78    4521   23.14    4545   25.24  4546.5   22.78
  4610.5    23.1  4613.7   23.08  4678.8   22.77  4783.8   22.26 4785.21   22.22
  4785.3   22.22  4785.4   22.22  4799.5   21.87  4800.1   20.58  4815.5   16.57
  4826.9   14.24  4830.8   13.13  4843.3   12.85  4843.5   12.85  4860.6   11.38
  4873.7   11.14  4874.8   10.68  4894.4   10.49  4905.4   10.08  4905.5   10.08
  4919.2    7.69  4954.7    1.48  4954.8     .97  4999.2   -6.24  5007.3   -6.86
  5007.5   -6.89    5026   -6.57  5032.2   -4.09  5045.2    1.12  5053.1    8.31
  5053.6    8.31  5070.5   10.98  5073.8   11.13  5085.6   12.53  5100.7   13.04
  5106.5   15.35  5115.5   14.22  5124.5   17.14  5129.9   18.89  5139.1   20.32
  5144.3   20.81  5159.2   22.58 5159.29   22.59  5159.4   22.61  5176.4   24.63
  5200.4   27.14    5214   27.58    5230   25.84    5246   25.93    5262   25.35
    5278   26.62  5287.5   26.73    5294   26.81    5310   26.91    5326   26.82
    5342   26.43    5390   27.32    5406   28.18    5430   28.65    5446   28.55
    5462   28.78  5472.2   29.15  5488.2   27.97  5512.2   29.28  5518.4   29.42
  5528.2   29.64  5544.2   29.78  5568.2   31.02  5584.2   31.24  5608.2   30.63
  5624.2   31.53  5656.2   32.08  5672.2   31.27  5696.2   31.36  5720.2   32.07
  5736.2   33.07  5752.2   32.51  5768.2   31.64  5800.2   32.43  5816.2   32.25
  5872.2   33.26  5888.2   32.13  5920.2   32.19  5952.2   32.13  6008.2   32.97
  6088.2   33.68  6104.2   33.44  6120.2   34.07  6152.2    33.5  6176.2   33.34
  6200.2   33.57  6216.2   33.95  6240.2   33.55  6288.2   34.19  6328.2    33.8
  6344.2   34.43  6376.2   33.79  6392.2    33.8  6416.2   34.02  6448.2   33.88
  6472.2    33.9  6496.2   33.47  6528.2   33.66  6552.9   33.95  6560.2   34.03
  6576.2   34.56  6592.2   34.75  6624.2   34.05  6640.2   35.02  6664.2   34.41
  6688.2   34.38  6784.2   34.83  6864.2   35.53  6904.2   36.42  6928.2   36.25
  6944.2   37.37  6949.6   37.59  6979.7   38.84
BR D #Mann= 5
  -964.4      .2   -47.4      .1  4905.4    .035  5053.1      .1  5518.4     .08
BR D Banks=4905.4,5053.1
BC Design=,, 0 ,, 0 ,,,,,,
BC HTab HWMax=38.91
BC Use User HTab Curves=0
BC User HTab FreeFlow(D)= 0

Type RM Length L Ch R = 1 ,57937.2 ,40.1,40.1,40.1
BEGIN DESCRIPTION:
Downstream Section of Bridge/Culvert/Weir
END DESCRIPTION:
XS GIS Cut Line= 6
      3169000.55     13869382.95       3165591.3      13867580.4
      3164405.74     13866946.68      3163956.43     13866702.66
      3163476.14     13866466.38       3161979.7     13865666.55
#Sta/Elev= 30
  -964.4   38.33   -47.4   37.34    1954   34.64    2674   35.26    2722    38.4
  2780.5   35.58  3052.5    36.6  3148.5   33.94  3862.7   35.48    4401   27.65
    4497   21.56    4545   25.02  4546.5   22.56  4783.8   22.04  4799.5   21.65
  4830.8   12.91  4905.4    9.86  5007.5   -7.11    5026   -6.79  5045.2      .9
  5053.1    8.09  5106.5   15.13  5115.5      14  5139.1    20.1  5200.4   26.92
    5262   25.13  5518.4    29.2  5736.2   32.85  6784.2   34.61  6979.7   38.62
#Mann= 5 , 1 , 0
  -964.4      .2       0   -47.4      .1       0  4905.4    .035       0
  5053.1      .1       0  5518.4     .08       0
#XS Ineff= 2 , 0
       0    4775    34.6    5169       0    34.7
Permanent Ineff=
       F       F
Bank Sta=4905.4,5053.1
XS Rating Curve= 0 ,0
Exp/Cntr=0.5,0.3

Type RM Length L Ch R = 1 ,57897.1 ,72,72,72
BEGIN DESCRIPTION:
Upstream Section of Bridge/Culvert/Weir
END DESCRIPTION:
XS GIS Cut Line= 5
      3169165.26     13869433.77      3164903.01     13867163.38
       3164233.1     13866794.81      3163501.04     13866415.22
      3161987.41     13865623.15
#Sta/Elev= 30
 -1133.7   37.72  -115.5   36.47  1186.3      35  1274.3   38.01  1826.3   34.66
  4003.8   34.89  4333.7    28.1  4668.3   30.23  4778.9   22.38  4798.5   17.45
  4813.1   19.42  4847.6   12.49  4915.2   12.52    4917     6.4  4943.1    8.15
  4965.4   -2.61  5000.7   -7.99  5028.1   -7.97    5062   10.97  5096.4   14.84
  5131.5   13.28  5162.5   19.79  5169.3   24.03  5169.7   29.64  5747.4   26.57
  5827.4   29.75  5859.4   27.43  6335.3   32.39  6982.3   38.27  6993.1   38.73
#Mann= 6 , 1 , 0
 -1133.7      .2       0  -115.5      .1       0  4915.2    .035       0
  5096.4      .1       0  6335.3     .08       0  6982.3      .2       0
#XS Ineff= 2 , 0
       0    4723    34.6    5221       0    34.7
Permanent Ineff=
       F       F
Bank Sta=4915.2,5096.4
XS Rating Curve= 0 ,0
Exp/Cntr=0.5,0.3