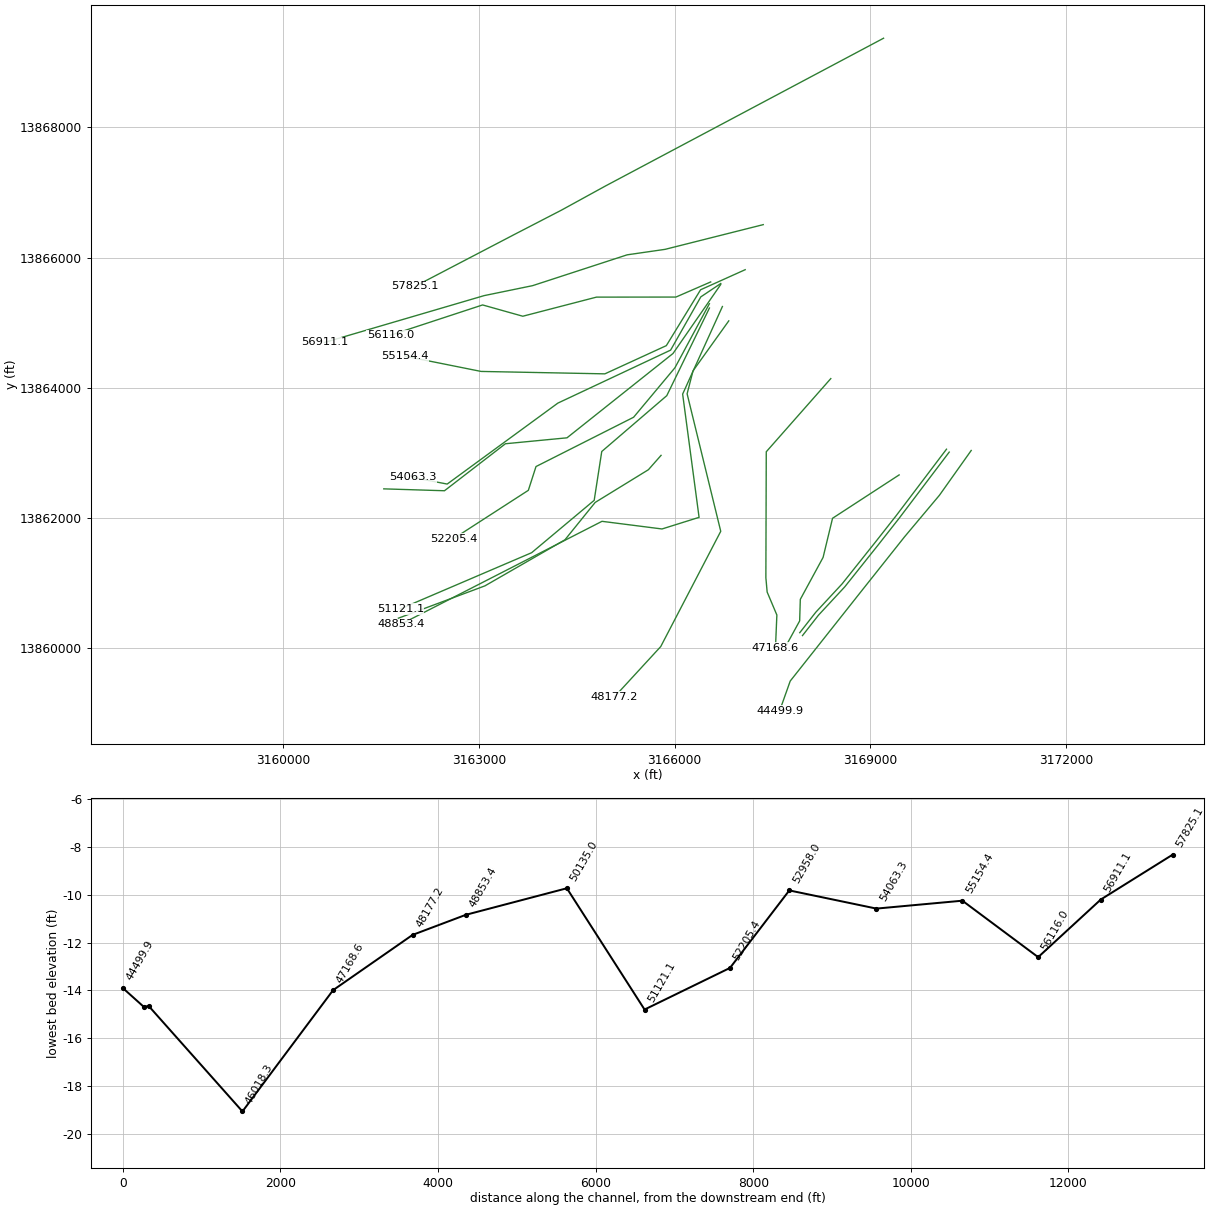
HEC-RAS study P100-00-00.prj: P100-00-00

--- P100-00-00.g01 (geometry) --- (continued)

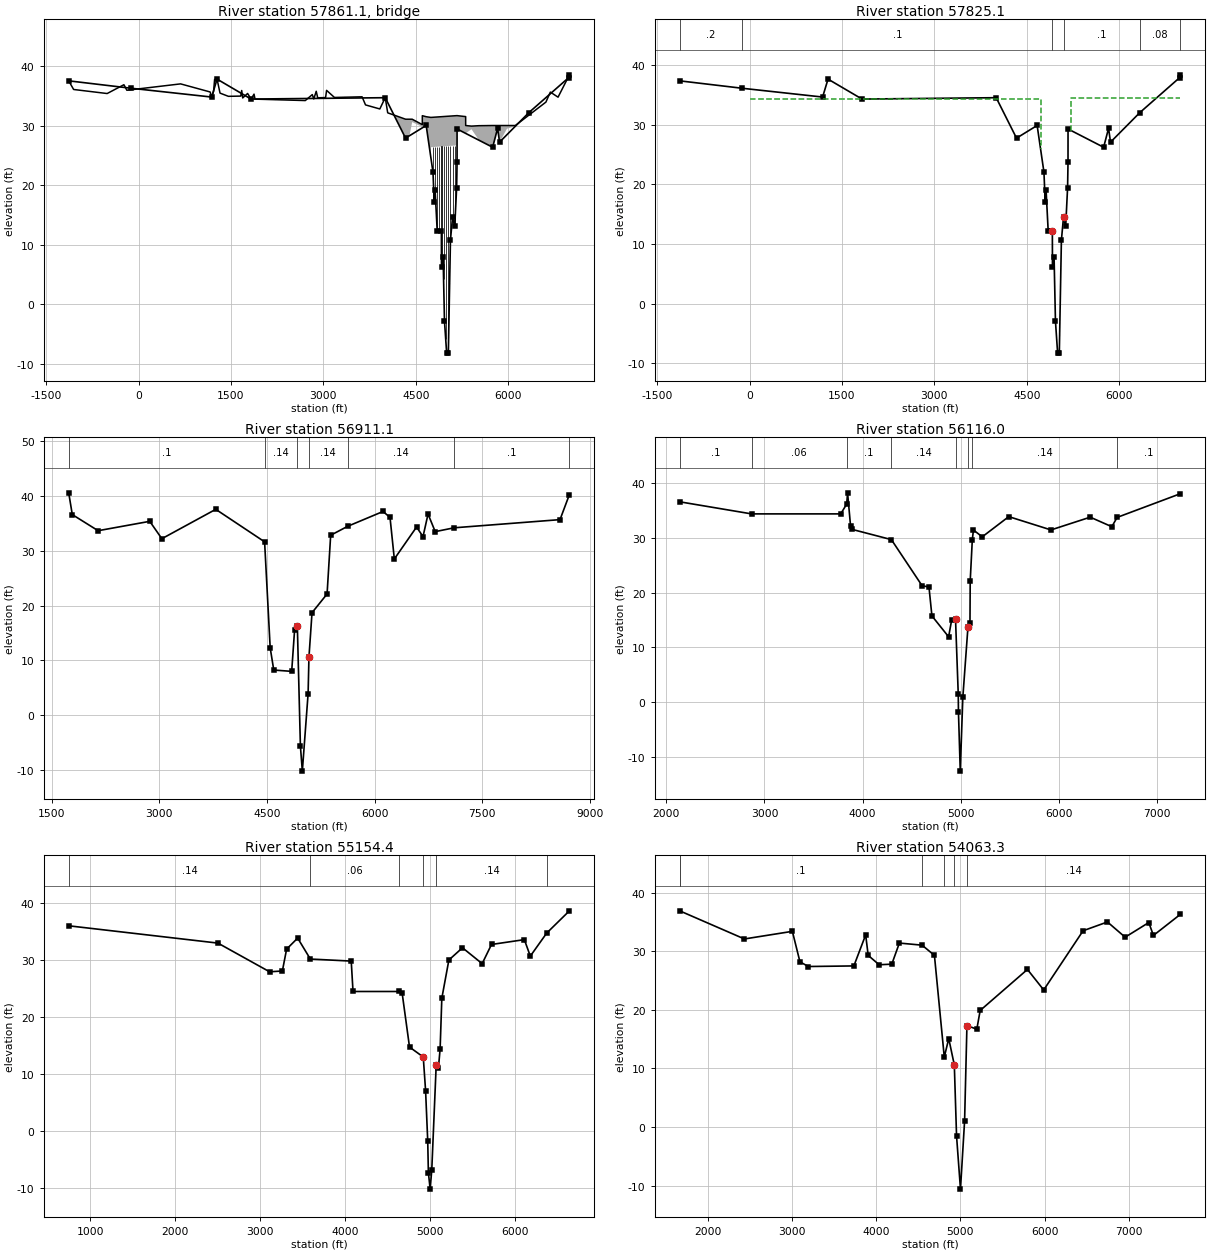
Type RM Length L Ch R = 3 ,57861.1 ,,,
BEGIN DESCRIPTION:
BEAUMONT HIGHWAY (HWY 90)
Structure ID: P00-15
END DESCRIPTION:
Bridge Culvert--1,0,-1,-1, 0
Deck Dist Width WeirC Skew NumUp NumDn MinLoCord MaxHiCord MaxSubmerge Is_Ogee
10,52,2.6,0, 60, 60, , , 0.95, 0, 1,1,,
 -1133.7 -1053.7  -509.7  -237.7  -189.7   682.3  1162.3  1186.3  1218.3  1234.3
  1274.3  1322.3  1458.3  1658.3  1674.3  1690.3  1770.3  1826.3  1874.3  1890.3
  2706.3  2819.8  2843.8  2883.8  2907.8  3035.8  3051.8  3179.8  3627.8  3683.8
  3915.8  4003.8  4043.8  4333.7  4397.7    4441 4605.59  4605.7  4668.3 4743.91
    4744 5166.09  5166.2  5169.3  5169.7  5279.7  5309.1 5309.21    5403  5523.4
  5747.4  5811.4  5827.4  5859.4  5979.4  6115.4  6611.4  6683.4  6808.7  6993.1
    37.5   36.05   35.37   36.85   35.92   36.99   35.63   34.78   35.75   37.74
   37.79   35.44    34.9   34.94   35.88   34.63   35.38   34.44   35.27   34.43
   34.19   35.19   34.46   35.75   34.65    34.7    35.9   34.71   34.82   33.46
   32.78   34.68   32.13   31.06   31.06   31.06   30.15   31.65   31.48   31.36
   31.36   31.66   31.66   31.66   31.66   31.53    31.5      30    29.9   29.97
      30      30      30      30      30      30   33.93   35.61   34.76   38.51
    37.5   36.05   35.37   36.85   35.92   36.99   35.63   34.78   35.75   37.74
   37.79   35.44    34.9   34.94   35.88   34.63   35.38   34.44   35.27   34.43
   34.19   35.18   34.45   35.74   34.64   34.69   35.89    34.7   34.81   33.45
   32.77   34.67   32.12   27.88   28.22   30.58   29.75   29.75   30.01   23.58
   26.36   26.66   21.88   23.81   29.42    28.1   28.63   28.63   29.38   27.58
   26.35   27.53   29.53   27.21   29.46   29.71   33.92    35.6   34.75   38.51
 -1133.7 -1053.7  -509.7  -237.7  -189.7   682.3  1162.3  1186.3  1218.3  1234.3
  1274.3  1322.3  1458.3  1658.3  1674.3  1690.3  1770.3  1826.3  1874.3  1890.3
  2706.3  2819.8  2843.8  2883.8  2907.8  3035.8  3051.8  3179.8  3627.8  3683.8
  3915.8  4003.8  4043.8  4333.7  4397.7    4441 4605.59  4605.7  4668.3 4743.91
    4744 5166.09  5166.2  5169.3  5169.7  5279.7  5309.1 5309.21    5403  5523.4
  5747.4  5811.4  5827.4  5859.4  5979.4  6115.4  6611.4  6683.4  6808.7  6993.1
    37.5   36.05   35.37   36.85   35.92   36.99   35.63   34.78   35.75   37.74
   37.79   35.44    34.9   34.94   35.88   34.63   35.38   34.44   35.27   34.43
   34.19   35.19   34.46   35.75   34.65    34.7    35.9   34.71   34.82   33.46
   32.78   34.68   32.13   31.06   31.06   31.06   30.15   31.65   31.48   31.36
   31.36   31.66   31.66   31.66   31.66   31.53    31.5      30    29.9   29.97
      30      30      30      30      30      30   33.93   35.61   34.76   38.51
   37.41   35.96   35.28   36.76   35.83    36.9   35.54   34.69   35.66   37.65
    37.7   35.35   34.81   34.85   35.79   34.54   35.29   34.35   35.18   34.34
    34.1   35.09   34.36   35.65   34.55    34.6    35.8   34.61   34.72   33.36
   32.68   34.58   32.03   27.79   28.13   30.49   29.66   29.66   29.92   23.49
   26.27   26.57   21.79   23.72   29.33   28.01   28.54   28.54   29.29   27.49
   26.26   27.44   29.44   27.12   29.37   29.62   33.83   35.51   34.66   38.42
Pier Skew, UpSta & Num, DnSta & Num=  ,4778.9, 2 ,4778.9, 2 , 0 , 0 , 0 ,,
     1.6     1.6
   20.96   27.47
     1.6     1.6
   20.87   27.38
Pier Skew, UpSta & Num, DnSta & Num=  ,4813.1, 2 ,4813.1, 2 , 0 , 0 , 0 ,,
     1.6     1.6
   18.06   27.57
     1.6     1.6
   17.97   27.48
Pier Skew, UpSta & Num, DnSta & Num=  ,4847.6, 2 ,4847.6, 2 , 0 , 0 , 0 ,,
     1.6     1.6
   11.27   27.68
     1.6     1.6
   11.18   27.59
Pier Skew, UpSta & Num, DnSta & Num=  ,4882.6, 2 ,4882.6, 2 , 0 , 0 , 0 ,,
     1.6     1.6
   10.23   27.78
     1.6     1.6
   10.14   27.69
Pier Skew, UpSta & Num, DnSta & Num=  ,4917, 2 ,4917, 2 , 0 , 0 , 0 ,,
     1.6     1.6
    5.23   27.86
     1.6     1.6
    5.14   27.77
Pier Skew, UpSta & Num, DnSta & Num=  ,4950.7, 2 ,4950.7, 2 , 0 , 0 , 0 ,,
     1.6     1.6
    2.27   27.92
     1.6     1.6
    2.18   27.83
Pier Skew, UpSta & Num, DnSta & Num=  ,4984.9, 2 ,4984.9, 2 , 0 , 0 , 0 ,,
     1.6     1.6
   -8.85    27.9
     1.6     1.6
   -8.94   27.81
Pier Skew, UpSta & Num, DnSta & Num=  ,5028.1, 2 ,5028.1, 2 , 0 , 0 , 0 ,,
     1.6     1.6
   -9.19   27.87
     1.6     1.6
   -9.28   27.78
Pier Skew, UpSta & Num, DnSta & Num=  ,5062, 2 ,5062, 2 , 0 , 0 , 0 ,,
     1.6     1.6
    8.86   27.81
     1.6     1.6
    8.77   27.72
Pier Skew, UpSta & Num, DnSta & Num=  ,5096.5, 2 ,5096.5, 2 , 0 , 0 , 0 ,,
     1.6     1.6
   12.44   27.75
     1.6     1.6
   12.35   27.66
Pier Skew, UpSta & Num, DnSta & Num=  ,5131.5, 2 ,5131.5, 2 , 0 , 0 , 0 ,,
     1.6     1.6
    12.1    27.7
     1.6     1.6
   12.01   27.61
BR Coef= 1 , 1 , 0 ,1.25, 0 ,,,0.8,0,2,0,
WSPro=,,,, 1 ,,,, 0 ,,,, 0 ,,,,-1 ,-1 ,-1 , 0 , 0 , 0 , 0 , 0
BR U #Sta/Elev= 30
 -1133.7    37.5  -115.5   36.25  1186.3   34.78  1274.3   37.79  1826.3   34.44
  4003.8   34.67  4333.7   27.88  4668.3   30.01  4778.9   22.16  4798.5   17.23
  4813.1    19.2  4847.6   12.27  4915.2    12.3    4917    6.18  4943.1    7.93
  4965.4   -2.83  5000.7   -8.21  5028.1   -8.19    5062   10.75  5096.4   14.62
  5131.5   13.06  5162.5   19.57  5169.3   23.81  5169.7   29.42  5747.4   26.35
  5827.4   29.53  5859.4   27.21  6335.3   32.17  6982.3   38.05  6993.1   38.51
BR U #Mann= 6
 -1133.7      .2  -115.5      .1  4915.2    .035  5096.4      .1  6335.3     .08
  6982.3      .2
BR U Banks=4915.2,5096.4
BR D #Sta/Elev= 30
 -1133.7   37.41  -115.5   36.16  1186.3   34.69  1274.3    37.7  1826.3   34.35
  4003.8   34.58  4333.7   27.79  4668.3   29.92  4778.9   22.07  4798.5   17.14
  4813.1   19.11  4847.6   12.18  4915.2   12.21    4917    6.09  4943.1    7.84
  4965.4   -2.92  5000.7    -8.3  5028.1   -8.28    5062   10.66  5096.4   14.53
  5131.5   12.97  5162.5   19.48  5169.3   23.72  5169.7   29.33  5747.4   26.26
  5827.4   29.44  5859.4   27.12  6335.3   32.08  6982.3   37.96  6993.1   38.42
BR D #Mann= 6
 -1133.7      .2  -115.5      .1  4915.2    .035  5096.4      .1  6335.3     .08
  6982.3      .2
BR D Banks=4915.2,5096.4
BC Design=,, 0 ,, 0 ,,,,,,
BC HTab HWMax=38.73
BC Use User HTab Curves=0
BC User HTab FreeFlow(D)= 0

Type RM Length L Ch R = 1 ,57825.1 ,914,914,914
BEGIN DESCRIPTION:
Downstream Section of Bridge/Culvert/Weir
END DESCRIPTION:
XS GIS Cut Line= 5
      3169200.19     13869370.81      3164937.95     13867100.42
      3164268.04     13866731.85      3163535.98     13866352.26
      3162022.34     13865560.19
#Sta/Elev= 30
 -1133.7   37.39  -115.5   36.14  1186.3   34.67  1274.3   37.68  1826.3   34.33
  4003.8   34.56  4333.7   27.77  4668.3    29.9  4778.9   22.05  4798.5   17.12
  4813.1   19.09  4847.6   12.16  4915.2   12.19    4917    6.07  4943.1    7.82
  4965.4   -2.94  5000.7   -8.32  5028.1    -8.3    5062   10.64  5096.4   14.51
  5131.5   12.95  5162.5   19.46  5169.3    23.7  5169.7   29.31  5747.4   26.24
  5827.4   29.42  5859.4    27.1  6335.3   32.06  6982.3   37.94  6993.1    38.4
#Mann= 6 , 1 , 0
 -1133.7      .2       0  -115.5      .1       0  4915.2    .035       0
  5096.4      .1       0  6335.3     .08       0  6982.3      .2       0
#XS Ineff= 2 , 0
       0    4723    34.4    5221       0    34.5
Permanent Ineff=
       F       F
Bank Sta=4915.2,5096.4
XS Rating Curve= 0 ,0
Exp/Cntr=0.5,0.3

Type RM Length L Ch R = 1 ,56911.1 ,785.9,795.1,804.2
BEGIN DESCRIPTION:
Cross Section 56911.1
END DESCRIPTION:
XS GIS Cut Line= 6
      3167357.31     13866508.22      3165853.39      13866128.7
      3165273.05     13866044.62      3163824.23      13865571.2
       3163082.7     13865418.37      3160635.42     13864698.48
#Sta/Elev= 30
  1735.9   40.57  1785.9    36.6  2145.9   33.66  2865.9   35.37  3034.6    32.2
  3786.2   37.56    4467   31.63  4544.6   12.32  4594.6    8.24  4844.6       8
  4884.6   15.47  4923.4   16.29  4966.1   -5.61  4992.9   -10.2  5073.6    3.95
  5085.1   10.55    5128    18.7    5338   22.12    5388   32.83  5626.3   34.47
  6118.4   37.17  6215.5   36.08  6275.5    28.5  6585.5   34.33  6675.5   32.58
  6745.5    36.7  6845.5   33.49  7108.8   34.19  8585.5   35.68  8716.5   40.26
#Mann= 7 , 1 , 0
  1735.9      .1       0    4467     .14       0  4923.4    .035       0
  5085.1     .14       0  5626.3     .14       0  7108.8      .1       0
  8716.5      .2       0
#XS Ineff= 2 , 0
       0  3786.2   37.56  6215.5       0   36.08
Permanent Ineff=
       F       F
Bank Sta=4923.4,5085.1
XS Rating Curve= 0 ,0
Exp/Cntr=0.3,0.1

Type RM Length L Ch R = 1 ,56116.0 ,1243.7,961.6,949.1
BEGIN DESCRIPTION:
Cross Section 56116.0
END DESCRIPTION:
XS GIS Cut Line= 6
      3166551.97     13865628.16      3166019.66     13865396.08
      3164802.29     13865395.15      3163674.27     13865101.73
       3163058.3     13865275.09      3161644.47     13864809.68
#Sta/Elev= 30
  2136.4   36.61    2869    34.4  3777.1    34.4    3838   36.19  3847.1   38.25
  3877.1   32.27  3897.1   31.55  4293.3    29.7  4606.4   21.27  4676.4   21.04
  4706.4   15.76  4876.5   11.94  4906.5   14.92  4946.8   15.22  4974.6    1.49
  4976.8    -1.8  4995.2  -12.61  5021.3     .87  5073.7   13.75  5094.1   14.54
  5096.5   22.12  5117.9   29.68  5129.4   31.45  5219.4   30.21  5489.4    33.9
  5919.3   31.47  6319.3    33.8  6539.3   32.06  6593.5   33.76  7237.8   38.09
#Mann= 8 , 1 , 0
  2136.4      .1       0    2869     .06       0    3838      .1       0
  4293.3     .14       0  4946.8    .035       0  5073.7     .14       0
  5117.9     .14       0  6593.5      .1       0
Bank Sta=4946.8,5073.7
XS Rating Curve= 0 ,0
Exp/Cntr=0.3,0.1

Type RM Length L Ch R = 1 ,55154.4 ,315.2,1091.1,1096.7
BEGIN DESCRIPTION:
Cross Section 55154.4
END DESCRIPTION:
XS GIS Cut Line= 6
      3167080.36     13865816.21      3166397.36     13865508.03
       3165872.6     13864650.09      3164931.36     13864216.95
      3163035.27     13864254.08      3161867.67     13864488.78
#Sta/Elev= 30
   747.9   36.01    2503   32.97  3110.8   27.93  3260.8   28.07  3310.8   31.91
  3440.8   33.85  3589.8   30.17  4070.7   29.81  4091.8   24.47    4627   24.47
  4669.4   24.22  4756.2   14.71  4917.9   12.96  4945.2    7.07  4970.4   -1.78
  4978.1   -7.34    4999  -10.25  5018.2   -6.82  5069.9   11.49  5096.2   11.05
  5116.2   14.38  5136.2   23.28  5219.2      30  5379.2   32.15  5610.6   29.36
  5720.6   32.73  6106.9   33.58  6176.9   30.68  6370.3   34.74  6636.9   38.64
#Mann= 6 , 1 , 0
   747.9     .14       0  3589.8     .06       0    4627     .14       0
  4917.9    .035       0  5069.9     .14       0  6370.3      .1       0
#XS Ineff= 2 , 0
       0  3440.8   33.85  5720.6       0   32.73
Permanent Ineff=
       F       F
Bank Sta=4917.9,5069.9
XS Rating Curve= 0 ,0
Exp/Cntr=0.3,0.1

Type RM Length L Ch R = 1 ,54063.3 ,1116.9,1105.3,1098.1
BEGIN DESCRIPTION:
Cross Section 54063.3
END DESCRIPTION:
XS GIS Cut Line= 6
      3166706.63     13865604.23       3166400.8     13865398.79
       3165938.3     13864581.34      3164211.13     13863767.55
      3162516.15     13862524.62      3161988.85     13862626.11
#Sta/Elev= 30
  1667.7    36.9  2436.1    32.1  3005.3    33.4  3095.3    28.2  3195.3    27.4
  3735.3    27.5  3875.3    32.8  3905.3    29.3  4035.3    27.7  4185.3    27.8
  4275.3    31.4  4545.1   31.04  4691.4    29.3  4808.4   11.95  4861.4    15.1
  4927.5    10.6  4954.1   -1.53  5000.6  -10.58  5049.5    1.07  5077.3   17.33
  5194.4    16.7  5234.4    19.9  5795.1    26.9  5988.5    23.4  6455.9    33.5
    6745      35    6955    32.4  7235.5    34.9  7290.6    32.7  7610.6    36.3
#Mann= 6 , 1 , 0
  1667.7      .2       0  1667.7      .1       0  4545.1     .14       0
  4808.4      .1       0  4927.5    .035       0  5077.3     .14       0
Bank Sta=4927.5,5077.3
XS Rating Curve= 0 ,0
Exp/Cntr=0.3,0.1

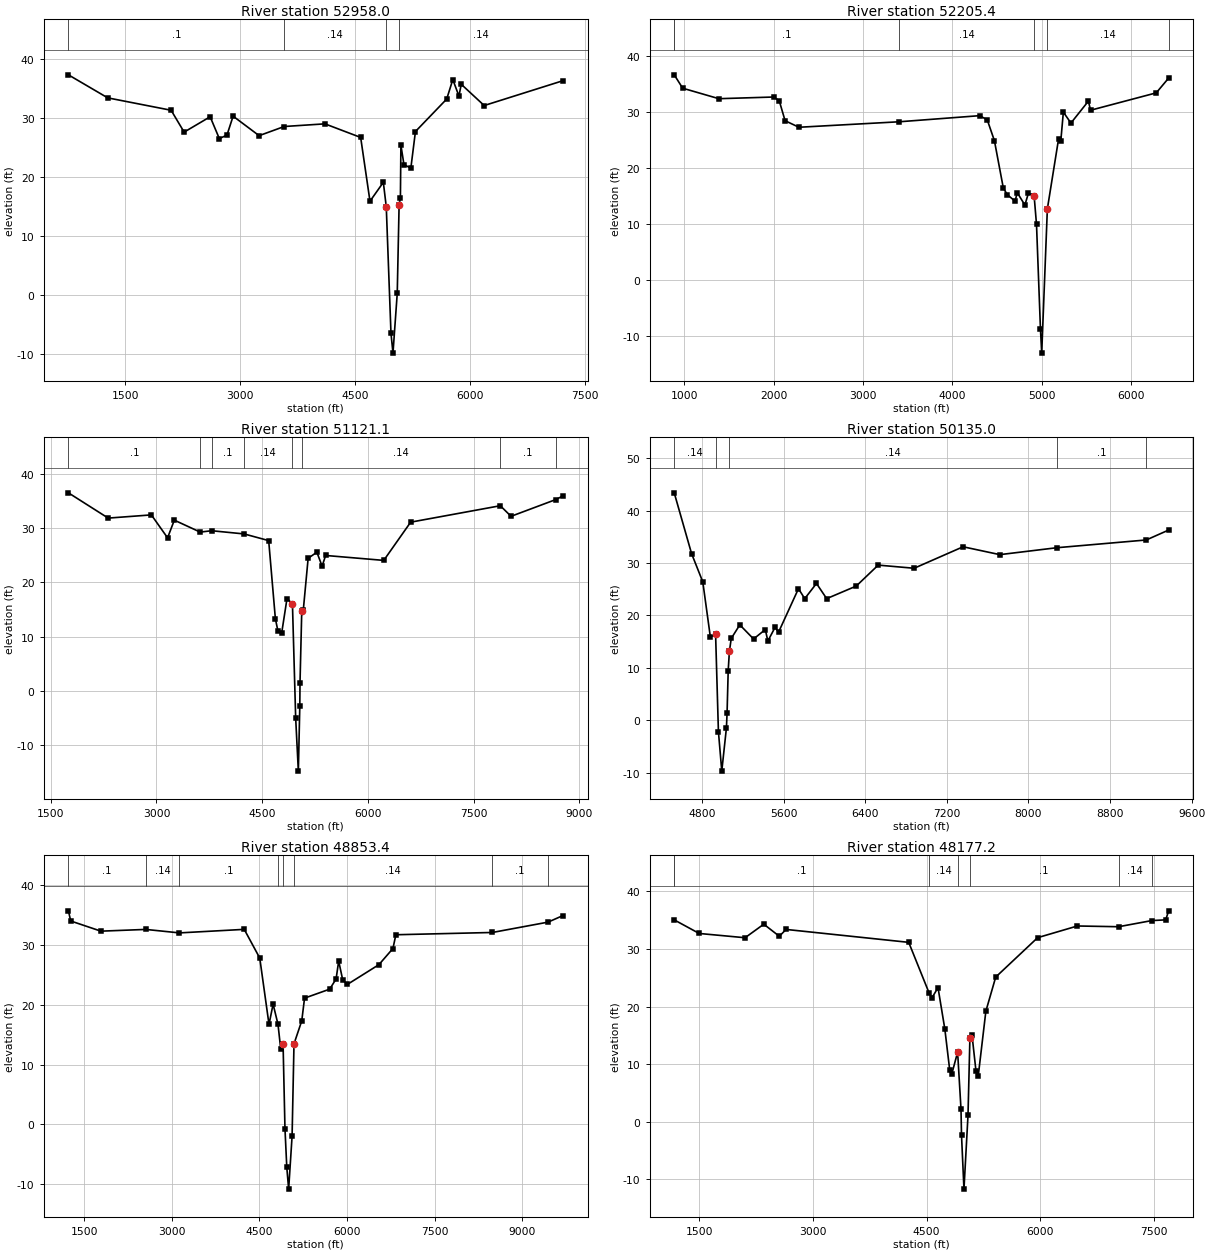
Type RM Length L Ch R = 1 ,52958.0 ,210.8,752.6,842.1
BEGIN DESCRIPTION:
Cross Section 52958.0
END DESCRIPTION:
XS GIS Cut Line= 6
      3166705.29     13865587.94      3165975.12      13864529.8
      3164351.13      13863234.7      3163407.82     13863143.66
      3162474.52     13862421.87      3161545.02     13862450.92
#Sta/Elev= 30
   753.9    37.3  1267.9    33.4  2096.6    31.3  2266.6    27.6  2606.6    30.2
  2726.6    26.5  2826.6    27.1  2906.6    30.3  3246.6      27  3574.8   28.55
  4106.6      29  4573.8    26.7  4695.5    15.9    4870    19.1  4908.4   14.96
    4970   -6.48  4996.1   -9.82  5051.8      .3  5076.2    15.3  5093.2   16.51
  5099.6    25.4  5139.6    22.1  5229.6    21.5  5289.6    27.7  5698.2    33.2
  5778.2    36.5  5858.2    33.7  5888.2    35.7  6188.2    32.1  7216.3    36.3
#Mann= 4 , 1 , 0
   753.9      .1       0  3574.8     .14       0  4908.4    .035       0
  5076.2     .14       0
Bank Sta=4908.4,5076.2
XS Rating Curve= 0 ,0
Exp/Cntr=0.3,0.1

Type RM Length L Ch R = 1 ,52205.4 ,596.2,1084.3,1211.1
BEGIN DESCRIPTION:
Cross Section 52205.4
END DESCRIPTION:
XS GIS Cut Line= 6
      3166532.38     13865293.81      3166004.45     13864310.44
      3165371.38     13863550.57       3163876.4     13862793.53
      3163759.03     13862428.39      3162611.45     13861685.07
#Sta/Elev= 30
   885.6   36.62   980.6   34.23  1385.6   32.36  2001.7   32.66  2061.7   31.98
  2126.7   28.43  2281.7   27.26  3404.6   28.24  4305.3   29.33  4390.3   28.58
  4470.3   24.87  4570.3    16.4  4615.3   15.22  4701.5   14.07  4726.5   15.58
  4811.5   13.37  4851.5   15.51  4914.8   15.05  4941.7    9.92  4985.8   -8.71
    5000  -13.06  5063.2   12.69  5188.8   25.18  5213.8   24.83  5242.2   29.96
  5327.2   28.01  5522.2   31.92  5547.2    30.3  6282.2    33.4  6421.6   36.05
#Mann= 6 , 1 , 0
   885.6      .2       0   885.6      .1       0  3404.6     .14       0
  4914.8    .035       0  5063.2     .14       0  6421.6      .2       0
Bank Sta=4914.8,5063.2
XS Rating Curve= 0 ,0
Exp/Cntr=0.3,0.1

Type RM Length L Ch R = 1 ,51121.1 ,1018.2,986.1,116.6
BEGIN DESCRIPTION:
Cross Section 51121.1
END DESCRIPTION:
XS GIS Cut Line= 6
      3166532.88     13865227.47       3165879.4     13863881.89
      3164883.55     13863024.53       3164767.7     13862274.91
      3163810.02     13861470.83      3161797.55     13860607.06
#Sta/Elev= 30
  1750.3   36.52  2315.3   31.86    2928   32.45    3158   28.22  3253.7   31.48
  3620.6   29.28  3784.6   29.53  4244.4   28.94  4592.9   27.71  4687.9    13.3
  4722.9   11.12  4777.9   10.71  4852.9   17.02  4930.1   16.05  4976.2   -5.08
  5013.9   -14.8  5034.5   -2.87  5037.5    1.49  5062.4    14.8  5083.6   14.83
  5152.9   24.45  5276.9   25.57  5351.1   22.99  5401.1   24.97  6226.1   24.06
  6607.9   31.11  7879.9   34.14  8032.9   32.19  8668.1   35.28  8767.9   35.94
#Mann= 8 , 1 , 0
  1750.3      .1       0  3620.6     .14       0  3784.6      .1       0
  4244.4     .14       0  4930.1    .035       0  5062.4     .14       0
  7879.9      .1       0  8668.1      .2       0
Bank Sta=4930.1,5062.4
XS Rating Curve= 0 ,0
Exp/Cntr=0.3,0.1

Type RM Length L Ch R = 1 ,50135.0 ,1199.3,1281.6,846.1
BEGIN DESCRIPTION:
Cross Section 50135.0
END DESCRIPTION:
XS GIS Cut Line= 6
      3165792.01     13862965.32      3165597.77     13862744.62
      3164782.73     13862242.56      3164319.78     13861668.76
      3163093.95     13860961.31       3161768.8     13860465.16
#Sta/Elev= 30
  4527.4    43.4  4697.4    31.8  4807.4    26.4  4881.4    15.9  4932.9   16.39
  4960.6   -2.17  4993.5   -9.73    5039   -1.49  5045.3     1.3  5056.5    9.46
  5068.2   13.16  5086.4    15.6  5170.2    18.2  5305.2    15.5  5420.2    17.3
  5445.2    15.1  5515.2    17.7  5550.2    16.8  5745.2    25.1  5806.7    23.2
  5921.7    26.1  6021.7    23.2  6311.7    25.6  6526.7    29.6  6878.9      29
  7358.9    33.1  7718.9    31.6  8277.8   32.92  9154.6    34.4  9374.2    36.3
#Mann= 5 , 1 , 0
  4527.4     .14       0  4932.9    .035       0  5068.2     .14       0
  8277.8      .1       0  9154.6      .2       0
Bank Sta=4932.9,5068.2
XS Rating Curve= 0 ,0
Exp/Cntr=0.3,0.1

Type RM Length L Ch R = 1 ,48853.4 ,416.5,676.2,1266.5
BEGIN DESCRIPTION:
Cross Section 48853.4
END DESCRIPTION:
XS GIS Cut Line= 6
      3166731.71     13865250.88      3166122.58     13863906.27
      3166374.22     13862013.36      3165806.42     13861835.03
      3164887.05      13861952.4      3161806.02     13860371.72
#Sta/Elev= 30
  1229.9    35.7  1269.9      34  1786.7    32.3    2554   32.59  3131.3   32.01
  4239.9    32.6  4505.6    27.8  4663.8    16.7  4733.8    20.1  4817.5   16.73
  4864.3    12.6  4904.7   13.35    4937    -.72  4968.3   -7.22    5000  -10.84
  5058.8   -1.98  5091.5   13.45  5224.3    17.3  5272.1    21.1  5702.1    22.6
  5812.1    24.3  5856.4    27.3  5926.4    24.1  6006.4    23.4  6545.1    26.7
  6785.1    29.4  6835.1    31.7  8486.6   32.08  9440.1   33.81  9693.5    34.9
#Mann= 8 , 1 , 0
  1229.9      .1       0    2554     .14       0  3131.3      .1       0
  4817.5     .14       0  4904.7    .035       0  5091.5     .14       0
  8486.6      .1       0  9440.1      .2       0
Bank Sta=4904.7,5091.5
XS Rating Curve= 0 ,0
Exp/Cntr=0.3,0.1

Type RM Length L Ch R = 1 ,48177.2 ,755.7,1008.6,1130.3
BEGIN DESCRIPTION:
Cross Section 48177.2
END DESCRIPTION:
XS GIS Cut Line= 6
      3166829.18     13865030.46      3166281.74     13864263.52
      3166191.06     13863910.42      3166706.23     13861799.17
      3165786.86     13860028.89      3165080.21     13859259.05
#Sta/Elev= 30
    1168   35.05    1498   32.69    2103   31.95  2350.3    34.3  2554.8   32.21
  2644.8   33.39  4263.2   31.15  4534.7   22.28  4570.4   21.53  4649.9   23.29
  4739.9    16.1  4804.9    8.92  4829.9    8.22  4908.7   12.09  4953.2    2.22
    4960   -2.31  4992.3  -11.68  5045.6    1.11  5070.7   14.47  5098.7   15.04
  5151.3    8.78  5181.3    8.02  5281.3   19.19  5411.3   25.12  5964.6   31.96
  6489.6   33.99  7033.3   33.86  7472.6   34.93  7654.6   35.05  7694.6   36.62
#Mann= 7 , 1 , 0
    1168      .2       0    1168      .1       0  4534.7     .14       0
  4908.7    .035       0  5070.7      .1       0  7033.3     .14       0
  7472.6      .1       0
Bank Sta=4908.7,5070.7
XS Rating Curve= 0 ,0
Exp/Cntr=0.3,0.1

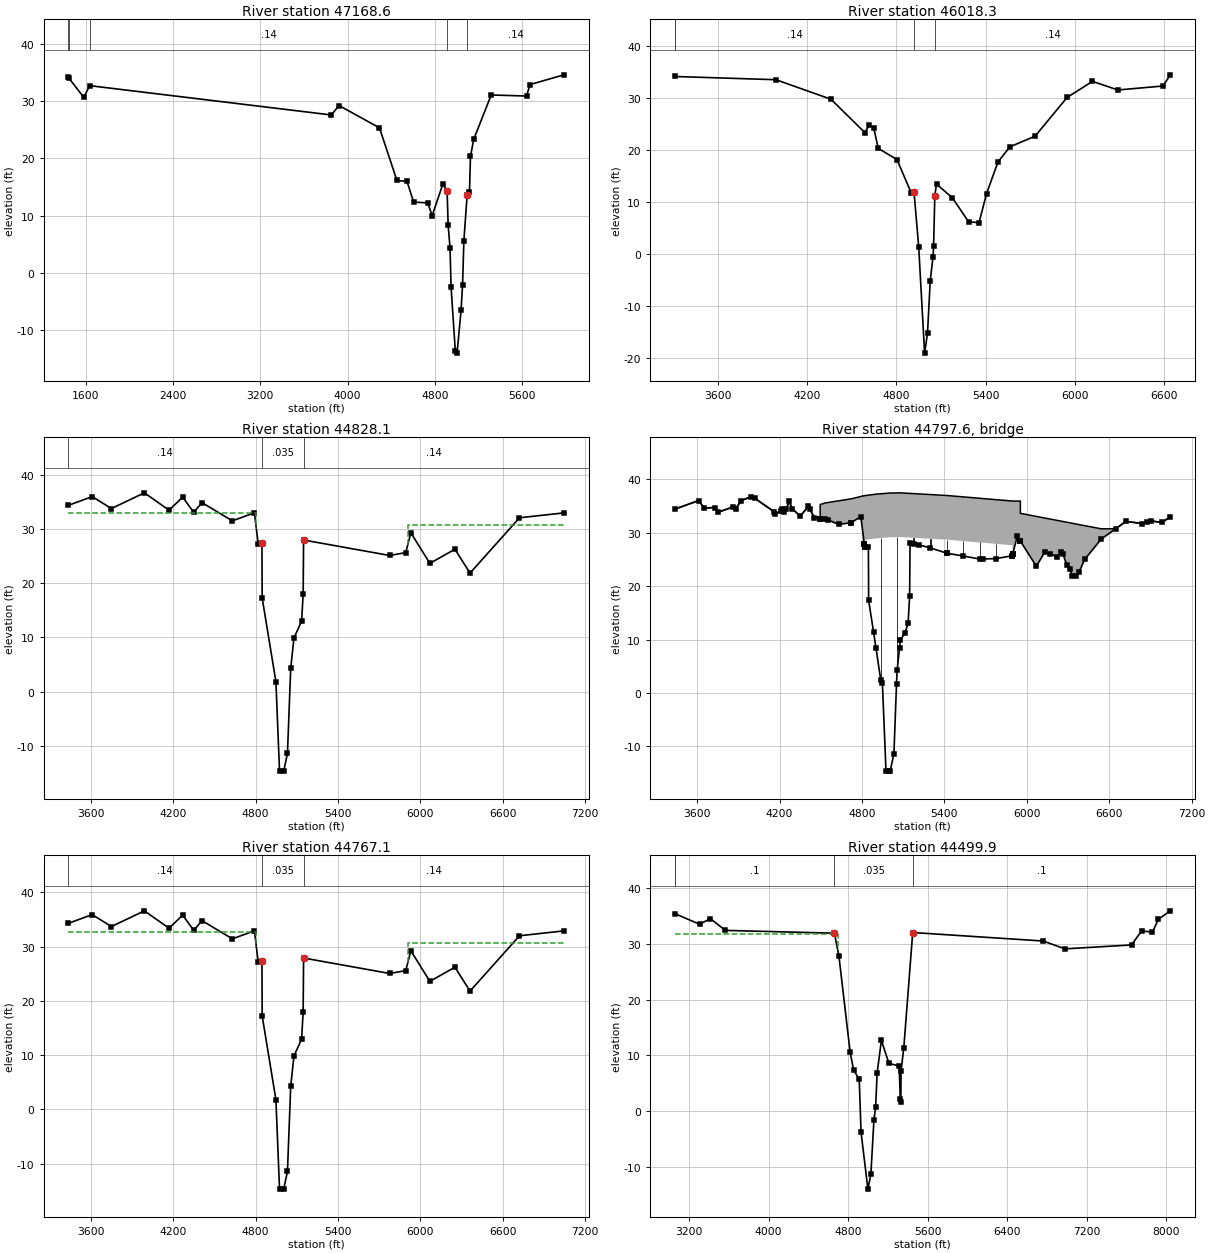
Type RM Length L Ch R = 1 ,47168.6 ,1211,1150.3,953.8
BEGIN DESCRIPTION:
Cross Section 47168.6
END DESCRIPTION:
XS GIS Cut Line= 6
      3168391.93      13864144.3      3167403.45     13863020.44
      3167397.39     13861088.45      3167416.95     13860866.76
      3167565.77      13860513.6      3167544.69     13860014.09
#Sta/Elev= 30
  1443.5   34.08  1444.1   34.05  1583.5   30.62  1638.7   32.65  3851.2   27.54
  3921.2   29.19  4291.9    25.3  4451.9   16.12  4544.5   15.95  4604.5   12.36
  4734.5    12.2  4774.5    9.97  4872.7   15.51  4911.5   14.25  4920.9    8.27
  4938.3    4.33  4947.5   -2.41  4986.7  -13.67  5002.7  -13.99  5039.2   -6.49
    5053    -2.1    5065    5.64  5095.1   13.61  5116.4   14.11  5125.2    20.3
  5155.2   23.29  5315.2   31.03  5638.5   30.84  5670.9   32.84  5980.9   34.54
#Mann= 5 , 1 , 0
  1443.5     .14       0  1444.1      .1       0  1638.7     .14       0
  4911.5    .035       0  5095.1     .14       0
Bank Sta=4911.5,5095.1
XS Rating Curve= 0 ,0
Exp/Cntr=0.3,0.1

Type RM Length L Ch R = 1 ,46018.3 ,1225.7,1190.2,587.9
BEGIN DESCRIPTION:
Cross Section 46018.3
END DESCRIPTION:
XS GIS Cut Line= 6
      3169438.63     13862664.96      3168418.74     13861999.35
      3168273.81     13861398.16       3167924.9     13860754.02
      3167914.86     13860423.11      3167708.61     13860045.63
#Sta/Elev= 30
  3309.7   34.09  3989.7   33.47  4359.7   29.72  4587.6   23.32  4617.6   24.76
  4647.6   24.21  4677.6   20.28  4803.6   18.14  4899.8   11.71  4918.6   11.86
  4949.9    1.42  4989.7  -19.06  5009.2  -15.21  5027.6   -5.19  5046.2    -.55
  5050.2    1.44  5058.4   11.21  5069.8   13.41  5176.2    10.8  5286.2    6.15
  5356.2    6.02  5406.2   11.56  5483.1   17.65  5563.1   20.57  5733.1   22.62
  5949.2   30.08  6119.2   33.15  6290.3    31.5  6593.2   32.26  6643.2   34.41
#Mann= 4 , 1 , 0
  3309.7      .2       0  3309.7     .14       0  4918.6    .035       0
  5058.4     .14       0
Bank Sta=4918.6,5058.4
XS Rating Curve= 0 ,0
Exp/Cntr=0.5,0.3

Type RM Length L Ch R = 1 ,44828.1 ,61,61,61
BEGIN DESCRIPTION:
Upstream Section of Bridge/Culvert/Weir
END DESCRIPTION:
XS GIS Cut Line= 6
      3170164.08     13863059.91       3169396.3     13862043.08
      3169084.97     13861645.86      3168564.29     13860990.99
      3168161.71      13860556.2      3167916.69     13860242.41
#Sta/Elev= 30
  3438.4   34.36  3611.2   35.96  3751.2   33.76  3991.2   36.66  4170.3   33.46
  4270.3   35.86  4350.3   33.06  4410.3   34.86  4631.4   31.49  4791.8   32.98
  4819.2   27.31  4846.6   27.36  4848.5   17.27  4948.5    1.84  4974.7  -14.57
  5005.2  -14.65  5032.5  -11.38  5056.3    4.35  5079.8     9.9  5135.6      13
  5146.8   18.08  5149.9   27.96  5776.4   25.11  5893.6   25.64  5930.5    29.3
  6069.1   23.66  6251.3   26.26  6361.3   21.86  6721.3   32.06  7044.5   32.96
#Mann= 3 , 1 , 0
  3438.4     .14       0  4846.6    .035       0  5149.9     .14       0
#XS Ineff= 2 , 0
       0    4806    32.9    5907       0    30.8
Permanent Ineff=
       F       F
Bank Sta=4846.6,5149.9
XS Rating Curve= 0 ,0
Exp/Cntr=0.5,0.3

Type RM Length L Ch R = 3 ,44797.6 ,,,
BEGIN DESCRIPTION:
SOUTH LAKE HOUSTON PARKWAY (SOUTHBOUND)
Structure ID: P00-14,,,,
END DESCRIPTION:
Bridge Culvert--1,0,-1,-1, 0
Deck Dist Width WeirC Skew NumUp NumDn MinLoCord MaxHiCord MaxSubmerge Is_Ogee
10,41,2.6,0, 58, 58, , , 0.95, 0, 1,1,,
  3438.4  3611.2  3651.2  3731.2  3751.2  3861.2  3881.2  3921.2  3991.2  4021.2
  4161.2  4170.3  4210.3  4220.3  4230.3  4250.3  4270.3  4290.3  4350.3  4410.3
    4453 4495.69  4495.8  4531.1  4551.3  4631.4  4721.9  4791.8 4816.61  4816.7
  4902.2  4998.1  5073.1  5418.5 5896.29  5896.4  5930.5    5953 5953.11  6069.1
  6129.1  6171.3  6221.3  6251.3  6261.3  6291.3  6311.3  6331.3  6361.3  6381.3
  6421.3  6541.3  6646.4  6721.3  6841.3  6901.3  6984.5  7044.5
    34.4   36.01   34.61   34.71   33.81   34.81   34.51   36.01   36.71   36.41
   33.91   33.51   34.01   34.41   33.81   34.51   35.91   34.51   33.11   34.91
   32.84   32.96   35.26   35.55   35.63   35.96   36.33   36.77   36.92   36.91
    37.2    37.4   37.45   36.95   35.91   35.91   35.91   35.91   33.61   33.04
   32.74   32.54   32.29   32.14   32.09   31.95   31.85   31.75    31.6    31.5
   31.31   30.72   30.74    32.1    31.7    32.2    31.9      33
    34.4      36    34.6    34.7    33.8    34.8    34.5      36    36.7    36.4
    33.9    33.5      34    34.4    33.8    34.5    35.9    34.5    33.1    34.9
   32.83   32.64   32.64   32.49    32.4   31.53   31.87   33.02   27.89   28.64
   28.93   29.13   29.18   28.68   27.64   25.96   29.34   28.42   28.42    23.7
    26.3    26.1    25.4    26.3    26.1    23.9    23.2    21.9    21.9    22.7
      25    28.8   30.73    32.1    31.7    32.2    31.9      33
  3438.4  3611.2  3651.2  3731.2  3751.2  3861.2  3881.2  3921.2  3991.2  4021.2
  4161.2  4170.3  4210.3  4220.3  4230.3  4250.3  4270.3  4290.3  4350.3  4410.3
    4453 4495.69  4495.8  4531.1  4551.3  4631.4  4721.9  4791.8 4816.61  4816.7
  4902.2  4998.1  5073.1  5418.5 5896.29  5896.4  5930.5    5953 5953.11  6069.1
  6129.1  6171.3  6221.3  6251.3  6261.3  6291.3  6311.3  6331.3  6361.3  6381.3
  6421.3  6541.3  6646.4  6721.3  6841.3  6901.3  6984.5  7044.5
    34.4   36.01   34.61   34.71   33.81   34.81   34.51   36.01   36.71   36.41
   33.91   33.51   34.01   34.41   33.81   34.51   35.91   34.51   33.11   34.91
   32.84   32.96   35.26   35.55   35.63   35.96   36.33   36.77   36.92   36.91
    37.2    37.4   37.45   36.95   35.91   35.91   35.91   35.91   33.61   33.04
   32.74   32.54   32.29   32.14   32.09   31.95   31.85   31.75    31.6    31.5
   31.31   30.72   30.74    32.1    31.7    32.2    31.9      33
   34.29   35.89   34.49   34.59   33.69   34.69   34.39   35.89   36.59   36.29
   33.79   33.39   33.89   34.29   33.69   34.39   35.79   34.39   32.99   34.79
   32.72   32.53   32.53   32.38   32.29   31.42   31.76   32.91   27.78   28.53
   28.82   29.02   29.07   28.57   27.53   25.85   29.23   28.31   28.31   23.59
   26.19   25.99   25.29   26.19   25.99   23.79   23.09   21.79   21.79   22.59
   24.89   28.69   30.62   31.99   31.59   32.09   31.79   32.89
Pier Skew, UpSta & Num, DnSta & Num=  ,4936.9, 2 ,4936.9, 2 , 0 , 0 , 0 ,,
     3.1     3.1
    1.34      30
     3.1     3.1
    1.23   29.89
Pier Skew, UpSta & Num, DnSta & Num=  ,5056.3, 2 ,5056.3, 2 , 0 , 0 , 0 ,,
     3.1     3.1
    2.53   30.17
     3.1     3.1
    2.42   30.06
Pier Skew, UpSta & Num, DnSta & Num=  ,5176.3, 2 ,5176.3, 2 , 0 , 0 , 0 ,,
     3.1     3.1
   26.96   30.01
     3.1     3.1
   26.85    29.9
Pier Skew, UpSta & Num, DnSta & Num=  ,5297.2, 2 ,5297.2, 2 , 0 , 0 , 0 ,,
     3.1     3.1
   26.14   29.84
     3.1     3.1
   26.03   29.73
Pier Skew, UpSta & Num, DnSta & Num=  ,5418, 2 ,5418, 2 , 0 , 0 , 0 ,,
     3.1     3.1
   25.15   29.68
     3.1     3.1
   25.04   29.57
Pier Skew, UpSta & Num, DnSta & Num=  ,5537.1, 2 ,5537.1, 2 , 0 , 0 , 0 ,,
     3.1     3.1
   24.62   29.43
     3.1     3.1
   24.51   29.32
Pier Skew, UpSta & Num, DnSta & Num=  ,5657.1, 2 ,5657.1, 2 , 0 , 0 , 0 ,,
     3.1     3.1
   24.06   29.17
     3.1     3.1
   23.95   29.06
Pier Skew, UpSta & Num, DnSta & Num=  ,5776.4, 2 ,5776.4, 2 , 0 , 0 , 0 ,,
     3.1     3.1
   24.15   28.91
     3.1     3.1
   24.04    28.8
Abutment Skew #Up #Dn= , 2 , 2
  4816.5  4819.2
   28.64   27.35
  4816.5  4819.2
   28.53   27.24
Abutment Skew #Up #Dn= , 2 , 2
  5893.6 5896.49
   25.68   27.64
  5893.6 5896.49
   25.57   27.53
BR Coef= 1 , 1 , 0 ,1.25, 0 ,,,0.8,0,2,0,
WSPro=,,,, 1 ,,,, 0 ,,,, 0 ,,,,-1 ,-1 ,-1 , 0 , 0 , 0 , 0 , 0
BR U #Sta/Elev= 94
  3438.4    34.4  3611.2      36  3651.2    34.6  3731.2    34.7  3751.2    33.8
  3861.2    34.8  3881.2    34.5  3921.2      36  3991.2    36.7  4021.2    36.4
  4161.2    33.9  4170.3    33.5  4210.3      34  4220.3    34.4  4230.3    33.8
  4250.3    34.5  4270.3    35.9  4290.3    34.5  4350.3    33.1  4410.3    34.9
  4419.7   34.44    4453   32.83 4495.69   32.64  4495.8   32.64 4495.91   32.64
  4531.1   32.49  4551.3    32.4  4631.4   31.53    4719   31.86  4721.9   31.87
  4791.8   33.02  4816.5   27.91 4816.61   27.89  4816.7   27.87  4816.8   27.85
  4819.1   27.37  4819.2   27.35  4846.6    27.4  4848.5   17.31    4884   11.48
  4902.2    8.36  4936.9    2.41  4948.5    1.88  4974.7  -14.53  4998.1  -14.59
  5005.2  -14.61  5032.5  -11.34  5051.4    1.67  5056.3    4.39  5073.1    8.36
  5079.8    9.94  5113.4   11.25  5135.6   13.04  5146.8   18.12  5149.9      28
  5176.3   27.97  5211.8   27.73  5297.2   27.15    5418   26.15  5418.5   26.15
  5537.1   25.63  5657.1   25.06  5682.3   25.08  5776.4   25.15  5893.5   25.68
  5893.6   25.68 5896.29   25.95  5896.4   25.96  5896.5   25.97  5896.7   25.99
  5930.5   29.34 5952.89   28.43    5953   28.42 5953.11   28.42  6069.1    23.7
  6129.1    26.3  6171.3    26.1  6221.3    25.4  6251.3    26.3  6261.3    26.1
  6291.3    23.9  6311.3    23.2  6331.3    21.9  6361.3    21.9  6381.3    22.7
  6421.3      25  6541.3    28.8  6646.4   30.73  6721.3    32.1  6841.3    31.7
  6871.3      32  6901.3    32.2  6984.5    31.9  7044.5      33
BR U #Mann= 3
  3438.4     .14  4846.6    .035  5149.9     .14
BR U Banks=4846.6,5149.9
BR D #Sta/Elev= 94
  3438.4   34.29  3611.2   35.89  3651.2   34.49  3731.2   34.59  3751.2   33.69
  3861.2   34.69  3881.2   34.39  3921.2   35.89  3991.2   36.59  4021.2   36.29
  4161.2   33.79  4170.3   33.39  4210.3   33.89  4220.3   34.29  4230.3   33.69
  4250.3   34.39  4270.3   35.79  4290.3   34.39  4350.3   32.99  4410.3   34.79
  4419.7   34.33    4453   32.72 4495.69   32.53  4495.8   32.53 4495.91   32.53
  4531.1   32.38  4551.3   32.29  4631.4   31.42    4719   31.75  4721.9   31.76
  4791.8   32.91  4816.5    27.8 4816.61   27.78  4816.7   27.76  4816.8   27.74
  4819.1   27.26  4819.2   27.24  4846.6   27.29  4848.5    17.2    4884   11.37
  4902.2    8.25  4936.9     2.3  4948.5    1.77  4974.7  -14.64  4998.1   -14.7
  5005.2  -14.72  5032.5  -11.45  5051.4    1.56  5056.3    4.28  5073.1    8.25
  5079.8    9.83  5113.4   11.14  5135.6   12.93  5146.8   18.01  5149.9   27.89
  5176.3   27.86  5211.8   27.62  5297.2   27.04    5418   26.04  5418.5   26.04
  5537.1   25.52  5657.1   24.95  5682.3   24.97  5776.4   25.04  5893.5   25.57
  5893.6   25.57 5896.29   25.84  5896.4   25.85  5896.5   25.86  5896.7   25.88
  5930.5   29.23 5952.89   28.32    5953   28.31 5953.11   28.31  6069.1   23.59
  6129.1   26.19  6171.3   25.99  6221.3   25.29  6251.3   26.19  6261.3   25.99
  6291.3   23.79  6311.3   23.09  6331.3   21.79  6361.3   21.79  6381.3   22.59
  6421.3   24.89  6541.3   28.69  6646.4   30.62  6721.3   31.99  6841.3   31.59
  6871.3   31.89  6901.3   32.09  6984.5   31.79  7044.5   32.89
BR D #Mann= 3
  3438.4     .14  4846.6    .035  5149.9     .14
BR D Banks=4846.6,5149.9
BC Design=,, 0 ,, 0 ,,,,,,
BC HTab HWMax=36.66
BC Use User HTab Curves=0
BC User HTab FreeFlow(D)= 0

Type RM Length L Ch R = 1 ,44767.1 ,267.2,267.2,267.2
BEGIN DESCRIPTION:
Downstream Section of Bridge/Culvert/Weir
END DESCRIPTION:
XS GIS Cut Line= 6
      3170205.78     13863015.39        3169438.     13861998.56
      3169126.67     13861601.34      3168605.99     13860946.47
      3168203.41     13860511.68      3167958.39     13860197.88
#Sta/Elev= 30
  3438.4   34.32  3611.2   35.92  3751.2   33.72  3991.2   36.62  4170.3   33.42
  4270.3   35.82  4350.3   33.02  4410.3   34.82  4631.4   31.45  4791.8   32.94
  4819.2   27.27  4846.6   27.32  4848.5   17.23  4948.5     1.8  4974.7  -14.61
  5005.2  -14.69  5032.5  -11.42  5056.3    4.31  5079.8    9.86  5135.6   12.96
  5146.8   18.04  5149.9   27.92  5776.4   25.07  5893.6    25.6  5930.5   29.26
  6069.1   23.62  6251.3   26.22  6361.3   21.82  6721.3   32.02  7044.5   32.92
#Mann= 3 , 1 , 0
  3438.4     .14       0  4846.6    .035       0  5149.9     .14       0
#XS Ineff= 2 , 0
       0    4806    32.8    5907       0    30.7
Permanent Ineff=
       F       F
Bank Sta=4846.6,5149.9
XS Rating Curve= 0 ,0
Exp/Cntr=0.5,0.3

Type RM Length L Ch R = 1 ,44499.9 ,58,58,58
BEGIN DESCRIPTION:
Upstream Section of Bridge/Culvert/Weir
END DESCRIPTION:
XS GIS Cut Line= 6
      3170542.82     13863040.25      3170055.59     13862352.19
      3169521.95     13861714.93      3168869.15     13860891.16
      3167770.27     13859499.63      3167608.34     13859042.21
#Sta/Elev= 30
  3057.9   35.37  3305.4   33.47  3415.4   34.47  3565.4   32.37    4662   31.87
  4707.4   27.83  4820.6   10.57  4855.1    7.43  4912.1    5.72  4930.4   -3.75
  4999.3   -13.9    5029  -11.25    5060    -1.5  5077.3     .83  5091.7    6.81
  5134.9    12.7  5210.3    8.61  5313.7     8.1  5324.7    2.28  5330.4    1.75
  5332.6    7.23  5360.3   11.39    5450   31.99  6761.5   30.47  6981.5   29.07
  7651.6   29.77  7751.6   32.27  7861.6   32.07  7921.6   34.37  8041.6   35.87
#Mann= 4 , 1 , 0
  3057.9      .2       0  3057.9      .1       0    4662    .035       0
    5450      .1       0
#XS Ineff= 2 , 0
       0    4696    31.8    5447       0    30.8
Permanent Ineff=
       F       F
Bank Sta=4662,5450
XS Rating Curve= 0 ,0
Exp/Cntr=0.5,0.3