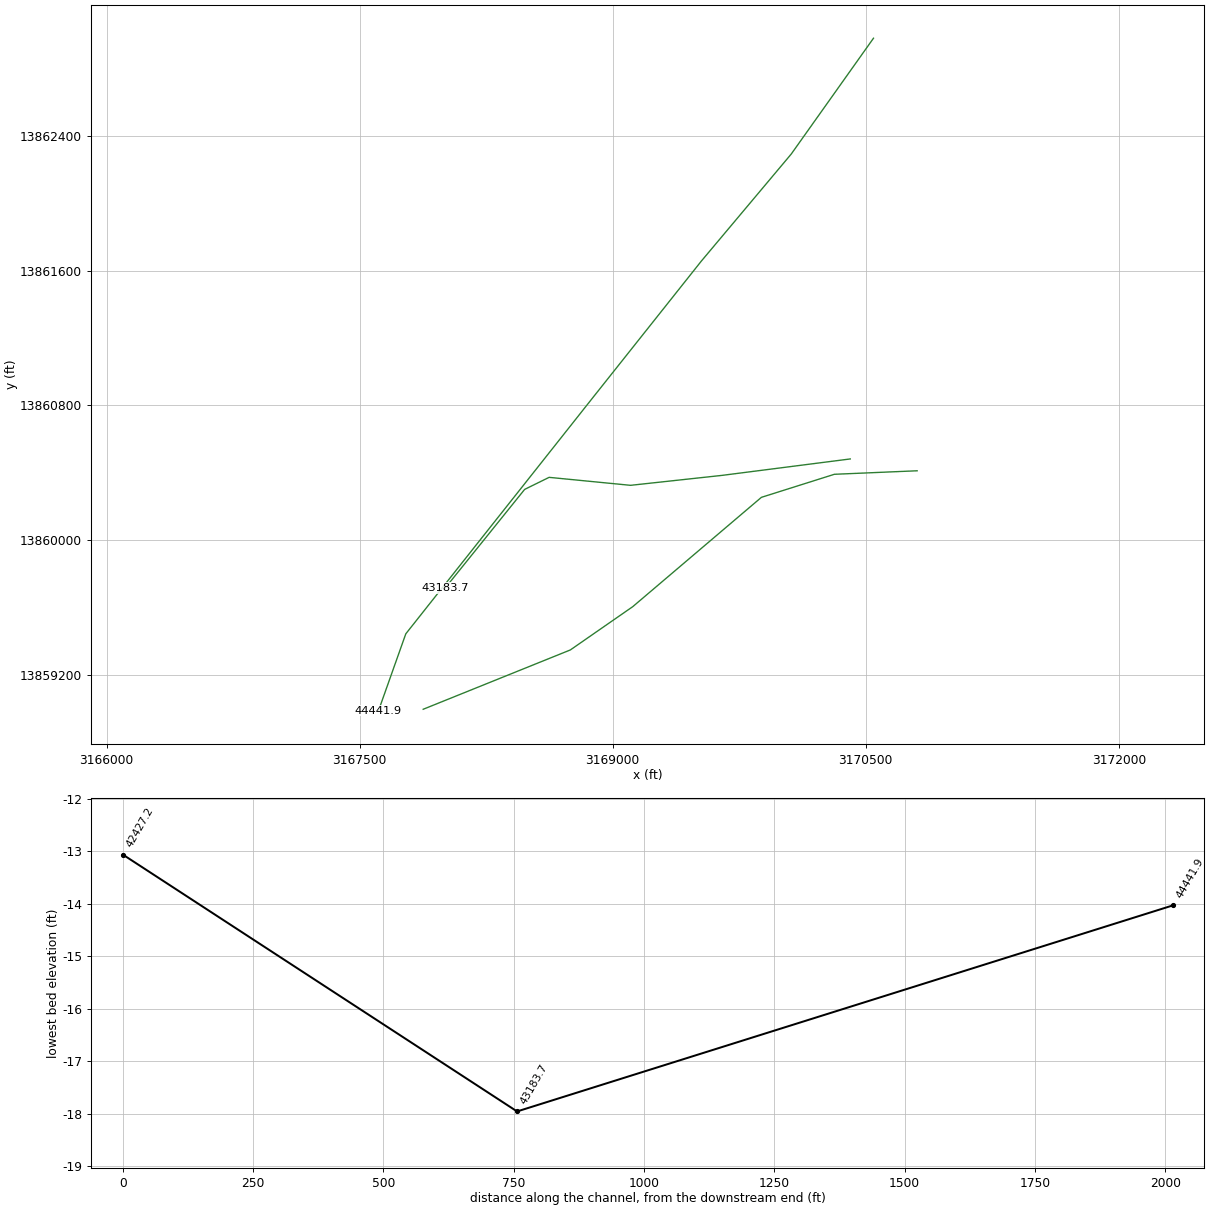
HEC-RAS study P100-00-00.prj: P100-00-00

--- P100-00-00.g01 (geometry) --- (continued)

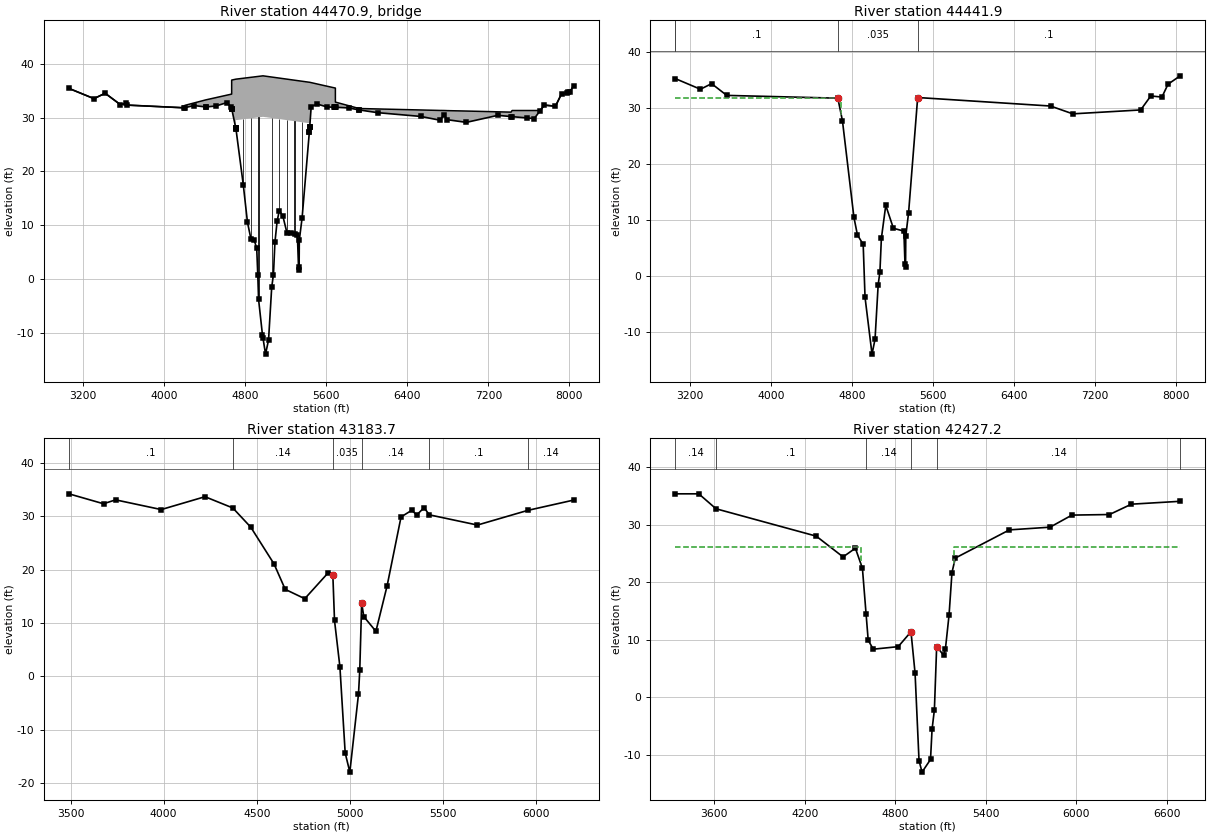
Type RM Length L Ch R = 3 ,44470.9 ,,,
BEGIN DESCRIPTION:
SOUTH LAKE HOUSTON PARKWAY (NORTHBOUND)
Structure ID: P00-13
END DESCRIPTION:
Bridge Culvert--1,0,-1,-1, 0
Deck Dist Width WeirC Skew NumUp NumDn MinLoCord MaxHiCord MaxSubmerge Is_Ogee
10,38,2.6,0, 45, 45, , , 0.95, 0, 1,1,,
  3057.9  3305.4  3415.4  3565.4  3625.4  3635.4  4198.7  4202.6  4291.4    4409
    4509  4618.3    4662 4664.59  4664.7 4705.61  4705.7  4973.9 5435.09  5435.2
    5450  5508.4  5607.5  5688.7 5688.81  5818.5  5922.3    6105  6531.5  6721.5
  6761.5  6791.5  6981.5  7291.6  7423.2  7433.2  7651.6  7711.4  7751.6  7861.6
  7921.6  7971.6  7981.6  8001.6  8041.6
    35.4    33.5    34.5    32.4    32.6    32.3    31.8   32.25   32.69   33.27
   33.69   34.15   34.33   34.34   36.94   37.11   37.11   37.73   36.53   36.53
   36.47   36.22    35.8   35.46   32.86    32.2   31.67   31.59    31.4   31.31
    31.3   31.28    31.2   31.06      31    31.3    31.3    31.3    32.3    32.1
    34.4    34.5    34.8    34.7    35.9
    35.4    33.5    34.5    32.4    32.6    32.3    31.8   31.82   32.22   31.96
   32.13   32.77    31.9   31.67   31.66   28.02   29.51   30.13   28.93   28.23
   32.02    32.5   31.95    31.9    31.9   31.78   31.41    30.9    30.2    29.5
    30.5    29.6    29.1    30.4   30.18   30.16    29.8   31.29    32.3    32.1
    34.4    34.5    34.8    34.7    35.9
  3057.9  3305.4  3415.4  3565.4  3625.4  3635.4  4198.7  4202.6  4291.4    4409
    4509  4618.3    4662 4664.59  4664.7 4705.61  4705.7  4973.9 5435.09  5435.2
    5450  5508.4  5607.5  5688.7 5688.81  5818.5  5922.3    6105  6531.5  6721.5
  6761.5  6791.5  6981.5  7291.6  7423.2  7433.2  7651.6  7711.4  7751.6  7861.6
  7921.6  7971.6  7981.6  8001.6  8041.6
    35.4    33.5    34.5    32.4    32.6    32.3    31.8   32.25   32.69   33.27
   33.69   34.15   34.33   34.34   36.94   37.11   37.11   37.73   36.53   36.53
   36.47   36.22    35.8   35.46   32.86    32.2   31.67   31.59    31.4   31.31
    31.3   31.28    31.2   31.06      31    31.3    31.3    31.3    32.3    32.1
    34.4    34.5    34.8    34.7    35.9
   35.27   33.37   34.37   32.27   32.47   32.17   31.67   31.69   32.09   31.83
      32   32.64   31.77   31.54   31.53   27.89   29.38      30    28.8    28.1
   31.89   32.37   31.82   31.77   31.77   31.65   31.28   30.77   30.07   29.37
   30.37   29.47   28.97   30.27   30.05   30.03   29.67   31.16   32.17   31.97
   34.27   34.37   34.67   34.57   35.77
Pier Skew, UpSta & Num, DnSta & Num=  ,4779.6, 2 ,4779.6, 2 , 0 , 0 , 0 ,,
     3.1     3.1
   16.24   30.68
     3.1     3.1
   16.11   30.55
Pier Skew, UpSta & Num, DnSta & Num=  ,4855.1, 2 ,4855.1, 2 , 0 , 0 , 0 ,,
     3.1     3.1
    6.45   30.86
     3.1     3.1
    6.32   30.73
Pier Skew, UpSta & Num, DnSta & Num=  ,4930.4, 2 ,4930.4, 2 , 0 , 0 , 0 ,,
     3.1     3.1
   -4.99   31.03
     3.1     3.1
   -5.12    30.9
Pier Skew, UpSta & Num, DnSta & Num=  ,5060, 2 ,5060, 2 , 0 , 0 , 0 ,,
     3.1     3.1
   -2.96   30.91
     3.1     3.1
   -3.09   30.78
Pier Skew, UpSta & Num, DnSta & Num=  ,5134.9, 2 ,5134.9, 2 , 0 , 0 , 0 ,,
     3.1     3.1
   11.59   30.71
     3.1     3.1
   11.46   30.58
Pier Skew, UpSta & Num, DnSta & Num=  ,5210.3, 2 ,5210.3, 2 , 0 , 0 , 0 ,,
     3.1     3.1
    7.64   30.52
     3.1     3.1
    7.51   30.39
Pier Skew, UpSta & Num, DnSta & Num=  ,5285.1, 2 ,5285.1, 2 , 0 , 0 , 0 ,,
     3.1     3.1
     7.4   30.32
     3.1     3.1
    7.27   30.19
Pier Skew, UpSta & Num, DnSta & Num=  ,5360.3, 2 ,5360.3, 2 , 0 , 0 , 0 ,,
     3.1     3.1
   10.19   30.12
     3.1     3.1
   10.06   29.99
Abutment Skew #Up #Dn= , 2 , 2
  4705.5  4707.4
   29.51   27.86
  4705.5  4707.4
   29.38   27.73
Abutment Skew #Up #Dn= , 2 , 2
  5431.5 5435.29
   27.29   28.93
  5431.5 5435.29
   27.16    28.8
BR Coef= 1 , 1 , 0 ,1.25, 0 ,,,0.8,0,2,0,
WSPro=,,,, 1 ,,,, 0 ,,,, 0 ,,,,-1 ,-1 ,-1 , 0 , 0 , 0 , 0 , 0
BR U #Sta/Elev= 83
  3057.9    35.4  3305.4    33.5  3415.4    34.5  3565.4    32.4  3625.4    32.6
  3635.4    32.3  4198.7    31.8  4202.6   31.82  4291.4   32.22    4409   31.96
  4409.8   31.96    4509   32.13  4618.3   32.77    4662    31.9 4664.59   31.67
  4664.7   31.66 4664.81   31.65  4705.4   28.04  4705.5   28.03 4705.61   28.02
  4705.7   28.01  4707.3   27.87  4707.4   27.86  4779.6    17.5  4820.6    10.6
  4855.1    7.46  4888.3    7.21  4912.1    5.75  4922.7     .76  4930.4   -3.72
  4968.5  -10.26  4973.9  -10.89  4999.3  -13.87    5029  -11.22    5060   -1.47
  5077.3     .86  5091.7    6.84  5113.8   10.81  5134.9   12.73    5170   11.74
  5210.3    8.64    5254    8.55  5285.1    8.42  5313.7    8.13  5324.7    2.31
  5330.4    1.78  5332.6    7.26  5360.3   11.42  5431.4   27.26  5431.5   27.29
 5435.09    28.2  5435.2   28.23  5435.3   28.26    5450   32.02  5508.4    32.5
  5607.5   31.95    5678   31.91 5688.59    31.9  5688.7    31.9 5688.81    31.9
  5692.4    31.9  5818.5   31.78  5922.3   31.41  5922.7   31.41    6105    30.9
  6531.5    30.2  6721.5    29.5  6761.5    30.5  6791.5    29.6  6981.5    29.1
  7291.6    30.4  7423.2   30.18  7433.2   30.16  7576.3   29.93  7651.6    29.8
  7711.4   31.29  7751.6    32.3  7861.6    32.1  7921.6    34.4  7971.6    34.5
  7981.6    34.8  8001.6    34.7  8041.6    35.9
BR U #Mann= 4
  3057.9      .2  3057.9      .1    4662    .035    5450      .1
BR U Banks=4662,5450
BR D #Sta/Elev= 83
  3057.9   35.27  3305.4   33.37  3415.4   34.37  3565.4   32.27  3625.4   32.47
  3635.4   32.17  4198.7   31.67  4202.6   31.69  4291.4   32.09    4409   31.83
  4409.8   31.83    4509      32  4618.3   32.64    4662   31.77 4664.59   31.54
  4664.7   31.53 4664.81   31.52  4705.4   27.91  4705.5    27.9 4705.61   27.89
  4705.7   27.88  4707.3   27.74  4707.4   27.73  4779.6   17.37  4820.6   10.47
  4855.1    7.33  4888.3    7.08  4912.1    5.62  4922.7     .63  4930.4   -3.85
  4968.5  -10.39  4973.9  -11.02  4999.3     -14    5029  -11.35    5060    -1.6
  5077.3     .73  5091.7    6.71  5113.8   10.68  5134.9    12.6    5170   11.61
  5210.3    8.51    5254    8.42  5285.1    8.29  5313.7       8  5324.7    2.18
  5330.4    1.65  5332.6    7.13  5360.3   11.29  5431.4   27.13  5431.5   27.16
 5435.09   28.07  5435.2    28.1  5435.3   28.13    5450   31.89  5508.4   32.37
  5607.5   31.82    5678   31.78 5688.59   31.77  5688.7   31.77 5688.81   31.77
  5692.4   31.77  5818.5   31.65  5922.3   31.28  5922.7   31.28    6105   30.77
  6531.5   30.07  6721.5   29.37  6761.5   30.37  6791.5   29.47  6981.5   28.97
  7291.6   30.27  7423.2   30.05  7433.2   30.03  7576.3    29.8  7651.6   29.67
  7711.4   31.16  7751.6   32.17  7861.6   31.97  7921.6   34.27  7971.6   34.37
  7981.6   34.67  8001.6   34.57  8041.6   35.77
BR D #Mann= 4
  3057.9      .2  3057.9      .1    4662    .035    5450      .1
BR D Banks=4662,5450
BC Design=,, 0 ,, 0 ,,,,,,
BC HTab HWMax=35.87
BC Use User HTab Curves=0
BC User HTab FreeFlow(D)= 0

Type RM Length L Ch R = 1 ,44441.9 ,1258.2,1258.2,1258.2
BEGIN DESCRIPTION:
Downstream Section of Bridge/Culvert/Weir
END DESCRIPTION:
XS GIS Cut Line= 6
      3170546.07     13862982.34      3170058.83     13862294.29
      3169525.19     13861657.03      3168872.39     13860833.26
      3167773.51     13859441.73      3167611.58      13858984.3
#Sta/Elev= 30
  3057.9   35.24  3305.4   33.34  3415.4   34.34  3565.4   32.24    4662   31.74
  4707.4    27.7  4820.6   10.44  4855.1     7.3  4912.1    5.59  4930.4   -3.88
  4999.3  -14.03    5029  -11.38    5060   -1.63  5077.3      .7  5091.7    6.68
  5134.9   12.57  5210.3    8.48  5313.7    7.97  5324.7    2.15  5330.4    1.62
  5332.6     7.1  5360.3   11.26    5450   31.86  6761.5   30.34  6981.5   28.94
  7651.6   29.64  7751.6   32.14  7861.6   31.94  7921.6   34.24  8041.6   35.74
#Mann= 4 , 1 , 0
  3057.9      .2       0  3057.9      .1       0    4662    .035       0
    5450      .1       0
#XS Ineff= 2 , 0
       0    4696    31.8    5447       0    30.8
Permanent Ineff=
       F       F
Bank Sta=4662,5450
XS Rating Curve= 0 ,0
Exp/Cntr=0.5,0.3

Type RM Length L Ch R = 1 ,43183.7 ,502.8,756.5,863.6
BEGIN DESCRIPTION:
Cross Section 43183.7
END DESCRIPTION:
XS GIS Cut Line= 6
      3170408.32     13860481.37      3169647.97     13860383.64
      3169105.82     13860324.59      3168623.09     13860371.96
      3168478.06     13860300.37      3168007.16      13859714.1
#Sta/Elev= 30
  3491.4   34.19  3677.2   32.33  3742.2   33.06  3987.2   31.24  4222.2   33.65
  4371.7   31.54    4468   27.94    4593   21.05    4653   16.29    4758   14.54
  4880.8   19.28  4908.8   18.97  4917.7   10.46  4946.7    1.76    4975  -14.36
    5000  -17.96  5046.5   -3.32  5053.3    1.11  5063.5   13.72  5075.1   11.17
    5140    8.43    5200   16.93    5275   29.86  5333.5   31.13  5358.5   30.21
  5398.5   31.59  5427.4   30.25  5685.2   28.34  5955.7   31.09  6202.2   33.02
#Mann= 6 , 1 , 0
  3491.4      .1       0  4371.7     .14       0  4908.8    .035       0
  5063.5     .14       0  5427.4      .1       0  5955.7     .14       0
Bank Sta=4908.8,5063.5
XS Rating Curve= 0 ,0
Exp/Cntr=0.5,0.3

Type RM Length L Ch R = 1 ,42427.2 ,80,80,80
BEGIN DESCRIPTION:
Upstream Section of Bridge/Culvert/Weir
END DESCRIPTION:
XS GIS Cut Line= 6
      3170804.91       13860411.      3170314.01     13860390.15
      3169881.63     13860253.19       3169119.4     13859603.68
      3168749.02     13859346.03      3167876.65     13858993.35
#Sta/Elev= 30
  3344.1   35.34  3499.1   35.34  3613.2   32.74  4276.9   27.98  4454.4   24.37
  4536.1   25.88  4582.6   22.39  4606.8   14.47  4620.8    9.89  4654.2    8.32
  4819.4    8.76  4904.2   11.35  4931.3    4.12  4957.4  -11.05  4977.3  -13.06
  5033.5  -10.86  5043.7   -5.63  5059.2   -2.21  5074.2    8.78  5119.8    7.28
    5132    8.32  5156.3   14.28  5175.5   21.64  5197.6   24.17  5555.9   29.07
  5824.8   29.54  5969.8   31.64  6218.6   31.74  6363.6   33.54  6686.6   34.04
#Mann= 6 , 1 , 0
  3344.1     .14       0  3613.2      .1       0  4606.8     .14       0
  4904.2    .035       0  5074.2     .14       0  6686.6      .2       0
#XS Ineff= 2 , 0
       0    4572    26.1    5188       0    26.1
Permanent Ineff=
       F       F
Bank Sta=4904.2,5074.2
XS Rating Curve= 0 ,0
Exp/Cntr=0.5,0.3