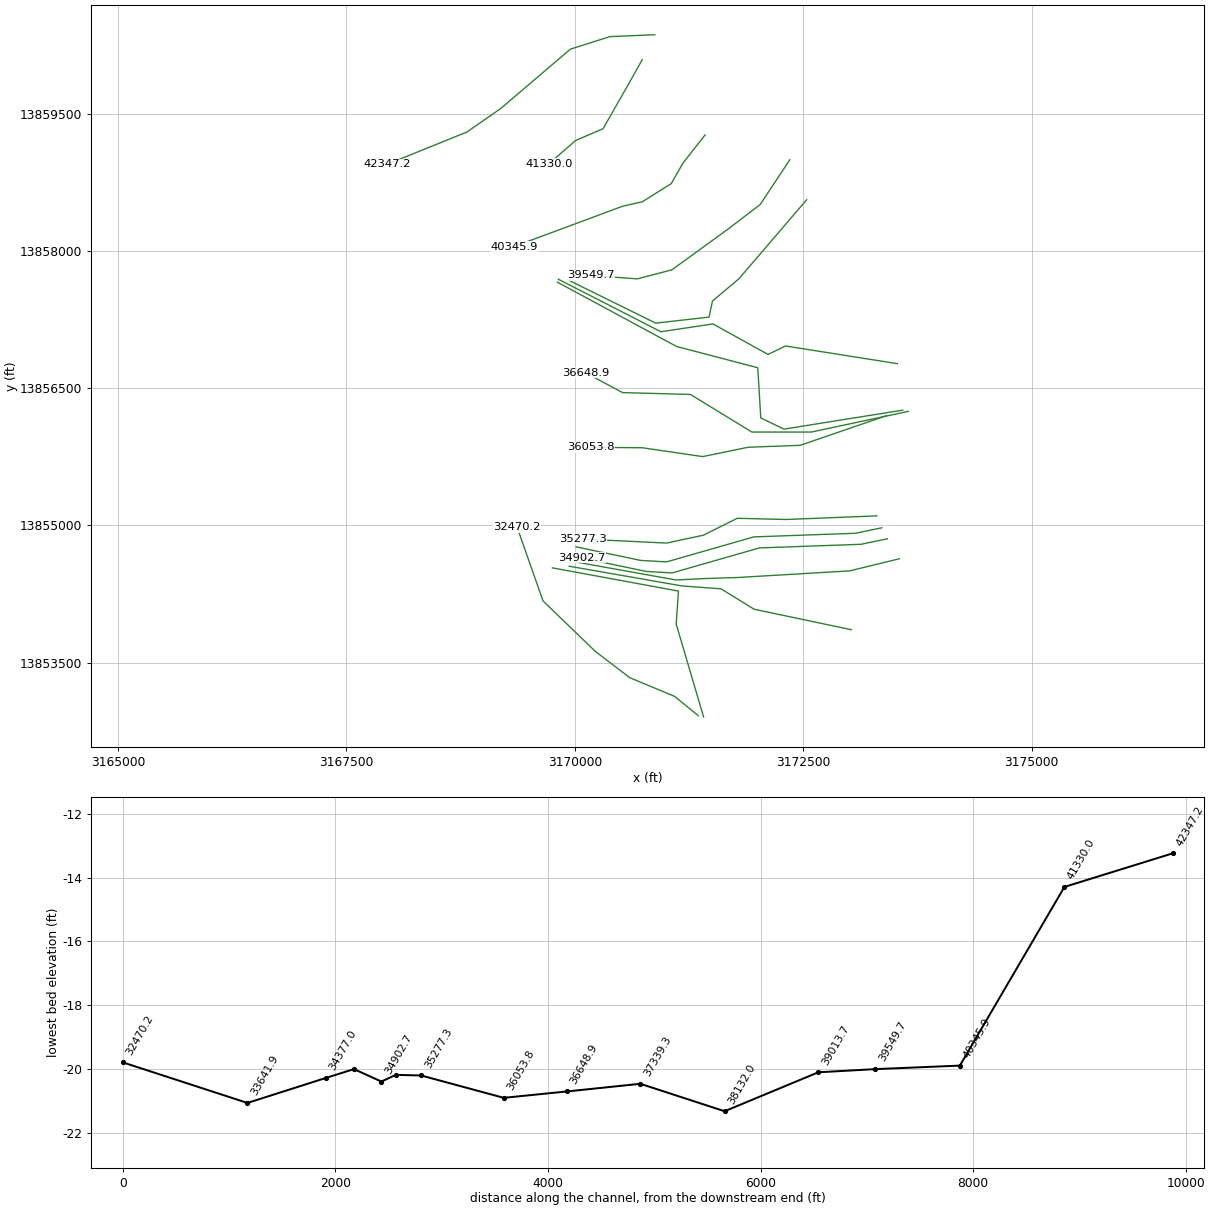
HEC-RAS study P100-00-00.prj: P100-00-00

--- P100-00-00.g01 (geometry) --- (continued)

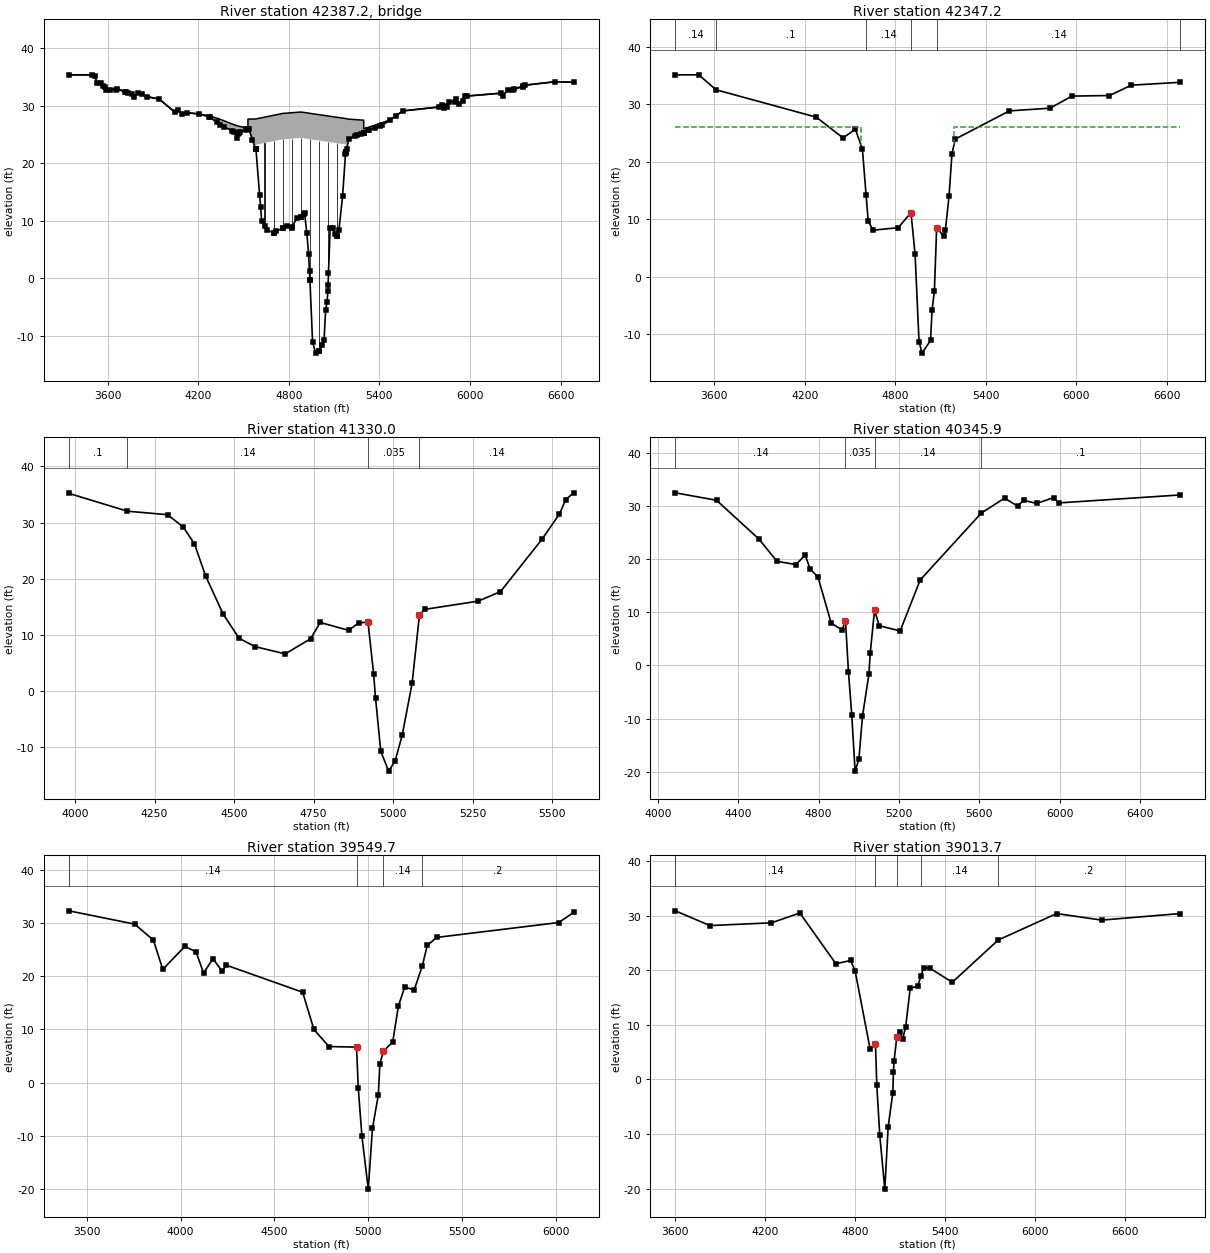
Type RM Length L Ch R = 3 ,42387.2 ,,,
BEGIN DESCRIPTION:
WALLISVILLE ROAD
Structure ID: P00-11
END DESCRIPTION:
Bridge Culvert--1,0,-1,-1, 0
Deck Dist Width WeirC Skew NumUp NumDn MinLoCord MaxHiCord MaxSubmerge Is_Ogee
10,60,2.6,0, 60, 60, , , 0.95, 0, 1,1,,
  3344.1  3499.1  3514.1  3529.1  3559.1  3589.1  3663.1  3763.1  3773.1  3803.1
  3858.1  3941.1  4046.1  4066.1  4096.1  4126.2  4208.1  4276.9  4342.7  4438.6
  4454.4    4463  4478.1 4529.59  4529.7  4536.1  4581.4 4581.51  4581.6  4582.6
  4760.9  4880.5 5177.69  5177.8  5197.6  5296.2 5296.31  5419.1  5472.3  5555.9
  5794.8  5814.8  5824.8  5834.8  5844.8  5859.8  5899.8  5909.8  5929.8  5954.8
  5969.8  6203.6  6218.6  6248.6  6283.6  6348.6  6353.6  6363.6  6563.6  6686.6
    35.4    35.4    35.2      34      34    32.8      33      32    31.5    32.3
    31.6    31.2    28.9    29.3    28.6    28.8   28.59   28.24    27.7   26.71
   26.58   26.51    26.4   26.19   27.69   27.71   27.72   27.72   27.72   27.73
   28.69   28.93   27.79   27.79   27.69   27.51   26.01   27.07    27.6   29.13
    29.8    30.1    29.6      30    29.8    30.7    30.7    31.2    30.4    30.9
    31.7    32.2    31.8    32.8    32.7    33.4    33.2    33.6    34.2    34.1
    35.4    35.4    35.2      34      34    32.8      33      32    31.5    32.3
    31.6    31.2    28.9    29.3    28.6    28.8   28.59   28.04   26.73   25.48
   24.43   25.11    25.5   25.97   25.97   25.94   22.47   22.47   23.22   23.23
   24.19   24.43   23.29   21.93   24.23   25.34   25.34   26.61   27.59   29.13
    29.8    30.1    29.6      30    29.8    30.7    30.7    31.2    30.4    30.9
    31.7    32.2    31.8    32.8    32.7    33.4    33.2    33.6    34.2    34.1
  3344.1  3499.1  3514.1  3529.1  3559.1  3589.1  3663.1  3763.1  3773.1  3803.1
  3858.1  3941.1  4046.1  4066.1  4096.1  4126.2  4208.1  4276.9  4342.7  4438.6
  4454.4    4463  4478.1 4529.59  4529.7  4536.1  4581.4 4581.51  4581.6  4582.6
  4760.9  4880.5 5177.69  5177.8  5197.6  5296.2 5296.31  5419.1  5472.3  5555.9
  5794.8  5814.8  5824.8  5834.8  5844.8  5859.8  5899.8  5909.8  5929.8  5954.8
  5969.8  6203.6  6218.6  6248.6  6283.6  6348.6  6353.6  6363.6  6563.6  6686.6
    35.4    35.4    35.2      34      34    32.8      33      32    31.5    32.3
    31.6    31.2    28.9    29.3    28.6    28.8   28.59   28.24    27.7   26.71
   26.58   26.51    26.4   26.19   27.69   27.71   27.72   27.72   27.72   27.73
   28.69   28.93   27.79   27.79   27.69   27.51   26.01   27.07    27.6   29.13
    29.8    30.1    29.6      30    29.8    30.7    30.7    31.2    30.4    30.9
    31.7    32.2    31.8    32.8    32.7    33.4    33.2    33.6    34.2    34.1
   35.17   35.17   34.97   33.77   33.77   32.57   32.77   31.77   31.27   32.07
   31.37   30.97   28.67   29.07   28.37   28.57   28.36   27.81    26.5   25.25
    24.2   24.88   25.27   25.74   25.74   25.71   22.24   22.24   22.99      23
   23.96    24.2   23.06    21.7      24   25.11   25.11   26.38   27.36    28.9
   29.57   29.87   29.37   29.77   29.57   30.47   30.47   30.97   30.17   30.67
   31.47   31.97   31.57   32.57   32.47   33.17   32.97   33.37   33.97   33.87
Pier Skew, UpSta & Num, DnSta & Num=  ,4639.6, 2 ,4639.6, 2 , 0 , 0 , 0 ,,
     1.4     1.4
    8.06   24.54
     1.4     1.4
    7.83   24.31
Pier Skew, UpSta & Num, DnSta & Num=  ,4699.7, 2 ,4699.7, 2 , 0 , 0 , 0 ,,
     1.4     1.4
    6.95   24.85
     1.4     1.4
    6.72   24.62
Pier Skew, UpSta & Num, DnSta & Num=  ,4759.8, 2 ,4759.8, 2 , 0 , 0 , 0 ,,
     1.4     1.4
    7.67   25.19
     1.4     1.4
    7.44   24.96
Pier Skew, UpSta & Num, DnSta & Num=  ,4819.4, 2 ,4819.4, 2 , 0 , 0 , 0 ,,
     1.4     1.4
    7.83   25.23
     1.4     1.4
     7.6      25
Pier Skew, UpSta & Num, DnSta & Num=  ,4878.8, 2 ,4878.8, 2 , 0 , 0 , 0 ,,
     1.4     1.4
    9.66   25.42
     1.4     1.4
    9.43   25.19
Pier Skew, UpSta & Num, DnSta & Num=  ,4940.1, 2 ,4940.1, 2 , 0 , 0 , 0 ,,
     1.4     1.4
   -1.78   25.33
     1.4     1.4
   -2.01    25.1
Pier Skew, UpSta & Num, DnSta & Num=  ,4999.6, 2 ,4999.6, 2 , 0 , 0 , 0 ,,
     1.4     1.4
  -13.59   25.16
     1.4     1.4
  -13.82   24.93
Pier Skew, UpSta & Num, DnSta & Num=  ,5059.2, 2 ,5059.2, 2 , 0 , 0 , 0 ,,
     1.4     1.4
   -3.37   24.78
     1.4     1.4
    -3.6   24.55
Pier Skew, UpSta & Num, DnSta & Num=  ,5119.8, 2 ,5119.8, 2 , 0 , 0 , 0 ,,
     1.4     1.4
    6.36    24.6
     1.4     1.4
    6.13   24.37
BR Coef= 1 , 1 , 0 ,1.25, 0 ,,,0.8,0,2,0,
WSPro=,,,, 1 ,,,, 0 ,,,, 0 ,,,,-1 ,-1 ,-1 , 0 , 0 , 0 , 0 , 0
BR U #Sta/Elev= 134
  3344.1    35.4  3499.1    35.4  3514.1    35.2  3529.1      34  3559.1      34
  3569.1    33.5  3584.1    33.2  3589.1    32.8  3613.2    32.8  3658.1    32.8
  3663.1      33  3713.1    32.4  3723.1    32.5  3738.1    32.2  3763.1      32
  3773.1    31.5  3803.1    32.3  3828.1    32.1  3858.1    31.6  3941.1    31.2
  4046.1    28.9  4066.1    29.3  4096.1    28.6  4126.2    28.8  4208.1   28.59
  4271.5   28.08  4276.9   28.04  4321.8   27.15  4342.7   26.73  4373.3   26.33
  4423.5   25.68  4438.6   25.48  4454.4   24.43    4463   25.11    4471   25.32
  4478.1    25.5  4515.4   25.75  4521.5      26  4521.9      26 4529.59   25.97
  4529.7   25.97 4529.81   25.97  4536.1   25.94  4559.7   24.08  4579.8   22.49
  4581.4   22.47 4581.51   22.47  4581.6   22.46  4581.8   22.46  4582.6   22.45
  4606.8   14.53  4613.1   12.47  4620.8    9.95  4639.6    9.09  4654.2    8.38
  4699.4    7.95  4699.7    7.95  4713.6    8.18  4759.8    8.68  4760.9    8.69
    4791    9.03  4819.4    8.82  4820.2    8.86  4852.6   10.48  4878.8   10.66
  4880.5   10.71  4898.9   11.22  4904.2   11.41  4919.7    7.86  4931.3    4.18
  4937.2    1.24    4940     -.3  4940.1    -.35  4957.4  -10.99  4977.3     -13
  4999.6  -12.58  5000.3  -12.55  5020.8  -11.55  5033.5   -10.8  5043.7   -5.57
  5052.9   -4.16  5059.2   -2.15  5060.4    -1.1  5062.8       1  5074.2    8.84
  5093.3    8.72  5107.9    7.73  5119.8    7.34  5120.2    7.37    5132    8.38
  5156.3   14.34  5175.5    21.7  5177.2   21.87 5177.69   21.92  5177.8   21.93
  5177.9   21.94    5183   22.45  5197.6   24.23  5235.2   24.71  5253.8   24.86
  5275.6   25.04 5296.09   25.34  5296.2   25.34 5296.31   25.34  5325.2   25.76
  5332.7   25.87  5370.9   26.11  5405.7   26.47  5419.1   26.61  5472.3   27.59
    5508   28.25  5555.9   29.13  5794.8    29.8  5814.8    30.1  5824.8    29.6
  5834.8      30  5844.8    29.8  5859.8    30.7  5899.8    30.7  5909.8    31.2
  5929.8    30.4  5954.8    30.9  5969.8    31.7  5978.6    31.7  6203.6    32.2
  6218.6    31.8  6248.6    32.8  6283.6    32.7  6293.6      33  6348.6    33.4
  6353.6    33.2  6363.6    33.6  6563.6    34.2  6686.6    34.1
BR U #Mann= 6
  3344.1     .14  3613.2      .1  4606.8     .14  4904.2    .035  5074.2     .14
  6686.6      .2
BR U Banks=4904.2,5074.2
BR D #Sta/Elev= 134
  3344.1   35.17  3499.1   35.17  3514.1   34.97  3529.1   33.77  3559.1   33.77
  3569.1   33.27  3584.1   32.97  3589.1   32.57  3613.2   32.57  3658.1   32.57
  3663.1   32.77  3713.1   32.17  3723.1   32.27  3738.1   31.97  3763.1   31.77
  3773.1   31.27  3803.1   32.07  3828.1   31.87  3858.1   31.37  3941.1   30.97
  4046.1   28.67  4066.1   29.07  4096.1   28.37  4126.2   28.57  4208.1   28.36
  4271.5   27.85  4276.9   27.81  4321.8   26.92  4342.7    26.5  4373.3    26.1
  4423.5   25.45  4438.6   25.25  4454.4    24.2    4463   24.88    4471   25.09
  4478.1   25.27  4515.4   25.52  4521.5   25.77  4521.9   25.77 4529.59   25.74
  4529.7   25.74 4529.81   25.74  4536.1   25.71  4559.7   23.85  4579.8   22.26
  4581.4   22.24 4581.51   22.24  4581.6   22.23  4581.8   22.23  4582.6   22.22
  4606.8    14.3  4613.1   12.24  4620.8    9.72  4639.6    8.86  4654.2    8.15
  4699.4    7.72  4699.7    7.72  4713.6    7.95  4759.8    8.45  4760.9    8.46
    4791     8.8  4819.4    8.59  4820.2    8.63  4852.6   10.25  4878.8   10.43
  4880.5   10.48  4898.9   10.99  4904.2   11.18  4919.7    7.63  4931.3    3.95
  4937.2    1.01    4940    -.53  4940.1    -.58  4957.4  -11.22  4977.3  -13.23
  4999.6  -12.81  5000.3  -12.78  5020.8  -11.78  5033.5  -11.03  5043.7    -5.8
  5052.9   -4.39  5059.2   -2.38  5060.4   -1.33  5062.8     .77  5074.2    8.61
  5093.3    8.49  5107.9     7.5  5119.8    7.11  5120.2    7.14    5132    8.15
  5156.3   14.11  5175.5   21.47  5177.2   21.64 5177.69   21.69  5177.8    21.7
  5177.9   21.71    5183   22.22  5197.6      24  5235.2   24.48  5253.8   24.63
  5275.6   24.81 5296.09   25.11  5296.2   25.11 5296.31   25.11  5325.2   25.53
  5332.7   25.64  5370.9   25.88  5405.7   26.24  5419.1   26.38  5472.3   27.36
    5508   28.02  5555.9    28.9  5794.8   29.57  5814.8   29.87  5824.8   29.37
  5834.8   29.77  5844.8   29.57  5859.8   30.47  5899.8   30.47  5909.8   30.97
  5929.8   30.17  5954.8   30.67  5969.8   31.47  5978.6   31.47  6203.6   31.97
  6218.6   31.57  6248.6   32.57  6283.6   32.47  6293.6   32.77  6348.6   33.17
  6353.6   32.97  6363.6   33.37  6563.6   33.97  6686.6   33.87
BR D #Mann= 6
  3344.1     .14  3613.2      .1  4606.8     .14  4904.2    .035  5074.2     .14
  6686.6      .2
BR D Banks=4904.2,5074.2
BC Design=,, 0 ,, 0 ,,,,,,
BC HTab HWMax=35.34
BC Use User HTab Curves=0
BC User HTab FreeFlow(D)= 0

Type RM Length L Ch R = 1 ,42347.2 ,1017.2,1017.2,1017.2
BEGIN DESCRIPTION:
Downstream Section of Bridge/Culvert/Weir
END DESCRIPTION:
XS GIS Cut Line= 6
      3170874.37     13860371.31      3170383.47     13860350.45
      3169951.09     13860213.49      3169188.86     13859563.98
      3168818.48     13859306.33      3167946.11     13858953.66
#Sta/Elev= 30
  3344.1   35.16  3499.1   35.16  3613.2   32.56  4276.9    27.8  4454.4   24.19
  4536.1    25.7  4582.6   22.21  4606.8   14.29  4620.8    9.71  4654.2    8.14
  4819.4    8.58  4904.2   11.17  4931.3    3.94  4957.4  -11.23  4977.3  -13.24
  5033.5  -11.04  5043.7   -5.81  5059.2   -2.39  5074.2     8.6  5119.8     7.1
    5132    8.14  5156.3    14.1  5175.5   21.46  5197.6   23.99  5555.9   28.89
  5824.8   29.36  5969.8   31.46  6218.6   31.56  6363.6   33.36  6686.6   33.86
#Mann= 6 , 1 , 0
  3344.1     .14       0  3613.2      .1       0  4606.8     .14       0
  4904.2    .035       0  5074.2     .14       0  6686.6      .2       0
#XS Ineff= 2 , 0
       0    4572      26    5188       0      26
Permanent Ineff=
       F       F
Bank Sta=4904.2,5074.2
XS Rating Curve= 0 ,0
Exp/Cntr=0.5,0.3

Type RM Length L Ch R = 1 ,41330.0 ,1006.2,984.1,944
BEGIN DESCRIPTION:
Cross Section 41330.0
END DESCRIPTION:
XS GIS Cut Line= 5
      3170736.96      13860097.8      3170565.87     13859793.18
      3170308.21     13859342.28      3170007.61     13859213.45
      3169713.36     13858957.41
#Sta/Elev= 30
  3981.1    35.2  4164.8   32.03  4291.1    31.4  4340.5    29.2  4375.5    26.2
  4410.5    20.5  4465.5    13.7  4515.5     9.4  4565.5     7.9  4660.5     6.6
  4740.5     9.3  4770.5    12.2  4859.8    10.8  4891.8   12.13  4920.6   12.27
  4938.5    2.95  4944.3   -1.22  4960.8  -10.77  4985.7  -14.29  5006.1  -12.41
  5028.1    -7.9  5059.3    1.37  5082.2   13.51  5098.7   14.53  5266.9      16
  5336.9    17.7  5466.9      27  5521.9    31.5  5541.9    34.1  5566.9    35.3
#Mann= 4 , 1 , 0
  3981.1      .1       0  4164.8     .14       0  4920.6    .035       0
  5082.2     .14       0
Bank Sta=4920.6,5082.2
XS Rating Curve= 0 ,0
Exp/Cntr=0.3,0.1

Type RM Length L Ch R = 1 ,40345.9 ,775.7,796.2,837.4
BEGIN DESCRIPTION:
Cross Section 40345.9
END DESCRIPTION:
XS GIS Cut Line= 6
      3171424.86     13859274.35      3171183.17     13858966.53
      3171054.34     13858741.09      3170737.64     13858542.48
      3170522.92     13858494.17      3169332.32     13858052.24
#Sta/Elev= 30
  4086.2    32.5  4291.2    31.1  4502.5    23.8  4592.5    19.6  4687.5      19
  4732.5    20.8  4757.2    18.2  4797.2    16.6  4862.2       8  4916.7    6.66
  4933.6    8.43  4948.5   -1.21  4964.8   -9.24  4981.6  -19.89  5000.5  -17.64
  5018.4   -9.58  5050.6   -1.57  5057.1    2.36  5078.3   10.39  5102.1    7.48
    5206     6.5    5306    16.1  5610.1   28.68  5726.1    31.5  5791.1      30
  5821.1    31.1  5886.1    30.5  5971.1    31.6  5996.1    30.6  6601.1    32.1
#Mann= 4 , 1 , 0
  4086.2     .14       0  4933.6    .035       0  5078.3     .14       0
  5610.1      .1       0
Bank Sta=4933.6,5078.3
XS Rating Curve= 0 ,0
Exp/Cntr=0.3,0.1

Type RM Length L Ch R = 1 ,39549.7 ,518,536,657.3
BEGIN DESCRIPTION:
Cross Section 39549.7-Interpolated
END DESCRIPTION:
XS GIS Cut Line= 6
      3172352.29     13859002.43      3172028.06     13858512.77
      3171664.12     13858234.85      3171061.97     13857798.12
      3170684.79     13857698.87      3170176.11     13857736.09
#Sta/Elev= 30
  3405.3    32.3  3755.3    29.8  3855.3    26.8  3905.3    21.3  4022.6    25.6
  4082.6    24.6  4122.6    20.6  4172.6    23.3  4222.6    20.9  4242.6    22.1
  4650.5      17  4710.5      10  4790.5     6.8  4937.7    6.68  4946.6    -.96
  4966.3  -10.09    5000     -20  5022.3   -8.59  5053.5   -2.32  5061.9    3.55
  5080.2    5.87  5130.5     7.7  5160.5    14.4  5194.3      18  5244.3    17.4
  5287.6   21.93  5314.3    25.8  5364.3    27.3  6014.4    30.1  6094.4      32
#Mann= 5 , 1 , 0
  3405.3      .2       0  3405.3     .14       0  4937.7    .035       0
  5080.2     .14       0  5287.6      .2       0
Bank Sta=4937.7,5080.2
XS Rating Curve= 0 ,0
Exp/Cntr=0.3,0.1

Type RM Length L Ch R = 1 ,39013.7 ,1048.9,881.7,500.1
BEGIN DESCRIPTION:
Cross Section 39013.7
END DESCRIPTION:
XS GIS Cut Line= 6
      3172535.86     13858563.95       3171795.1     13857699.73
      3171506.18     13857457.01      3171468.52     13857280.49
      3170884.86      13857214.6      3169921.73     13857688.99
#Sta/Elev= 30
  3603.7    30.9  3833.7    28.2  4243.7    28.7  4433.7    30.5  4673.7    21.2
  4771.9    21.8  4801.9    19.9  4901.9     5.6  4937.7    6.58  4946.6   -1.06
  4966.3  -10.19    5000   -20.1  5022.3   -8.69  5053.5   -2.42  5057.5    1.45
  5061.9    3.45  5080.2    7.77    5099    8.68  5119.3     7.4  5139.3     9.7
  5169.3    16.7  5219.3    17.1  5240.3   18.88  5259.3    20.5  5299.8    20.4
  5449.8    17.8  5755.8   25.55  6145.6    30.4  6445.6    29.2  6969.2    30.4
#Mann= 6 , 1 , 0
  3603.7      .2       0  3603.7     .14       0  4937.7    .035       0
  5080.2     .14       0  5240.3     .14       0  5755.8      .2       0
#XS Ineff= 2 , 0
       0  4433.7    30.5               0
Permanent Ineff=
       F       F
Bank Sta=4937.7,5080.2
XS Rating Curve= 0 ,0
Exp/Cntr=0.3,0.1

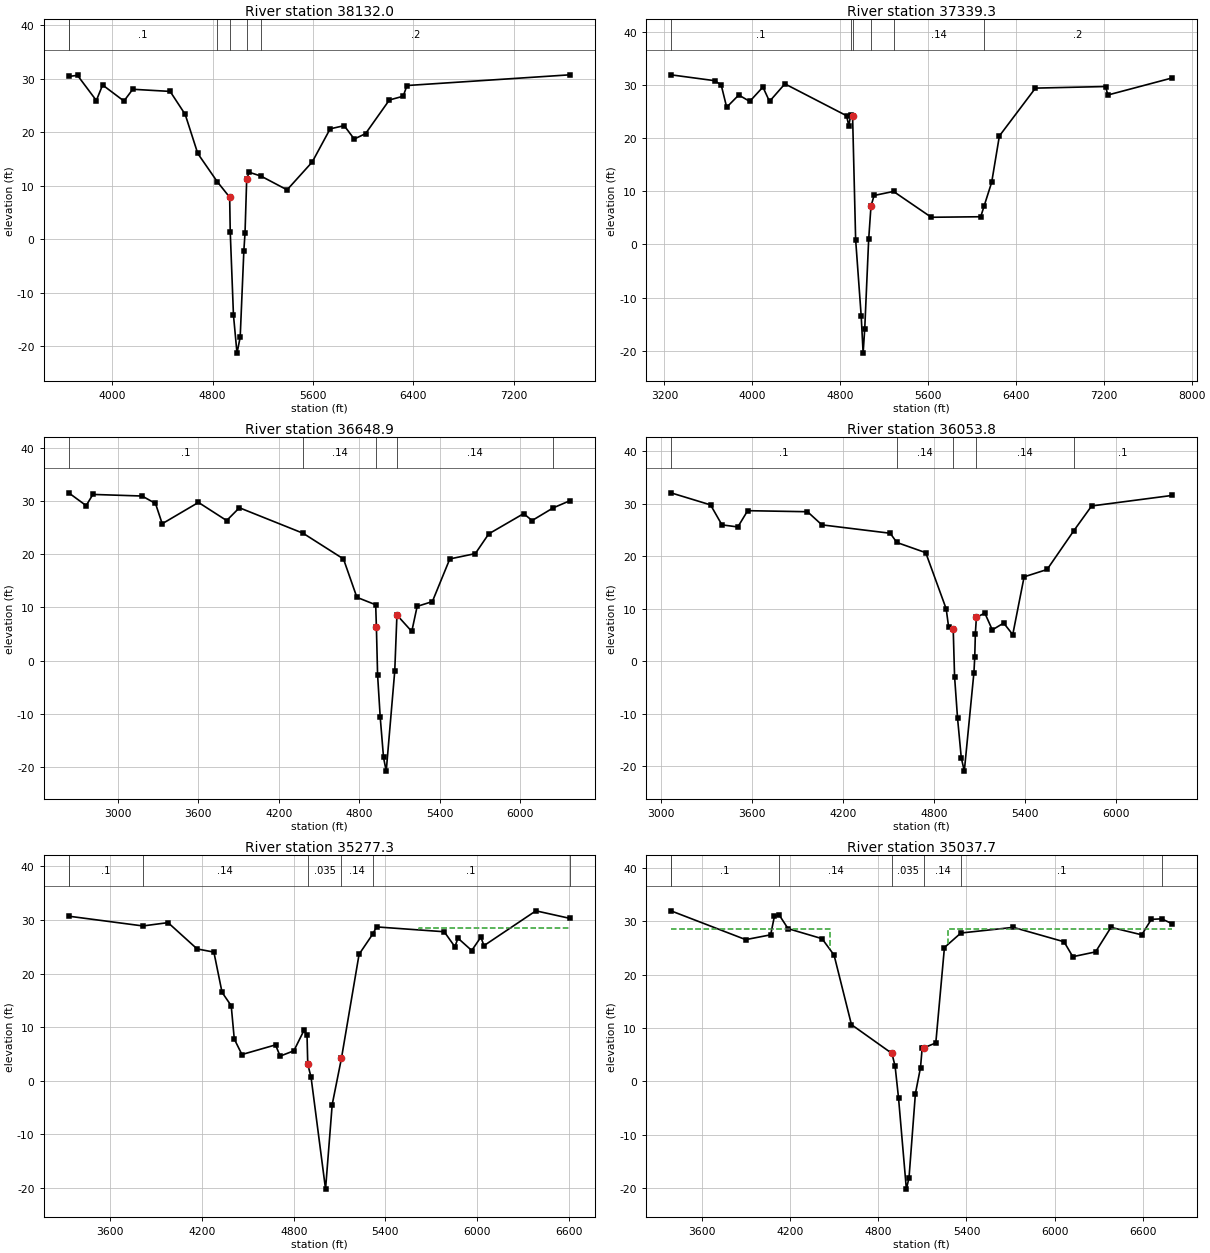
Type RM Length L Ch R = 1 ,38132.0 ,1152.6,792.7,332.6
BEGIN DESCRIPTION:
Cross Section 38132.0
END DESCRIPTION:
XS GIS Cut Line= 6
       3173528.9      13856771.1      3172305.97     13856964.38
      3172114.08     13856871.74       3171510.6     13857205.89
      3170941.61     13857120.01      3169819.74     13857694.36
#Sta/Elev= 30
  3654.7    30.4  3724.7    30.6  3874.7    25.9  3924.7    28.8  4094.7    25.8
  4164.7      28  4462.4    27.6  4582.4    23.3  4682.4      16  4838.5    10.7
  4936.5    7.82  4941.1    1.33  4966.7  -14.19  4994.9  -21.32  5020.3  -18.34
  5049.6   -2.15  5058.8    1.12  5072.3   11.31  5093.1   12.48    5186   11.77
  5393.8     9.2  5593.8    14.4  5736.7    20.6  5848.5    21.2  5928.5    18.7
  6018.5    19.7  6208.5      26  6318.5    26.7  6348.5    28.7  7644.3    30.7
#Mann= 6 , 1 , 0
  3654.7      .2       0  3654.7      .1       0  4838.5     .14       0
  4936.5    .035       0  5072.3     .14       0    5186      .2       0
#XS Ineff= 2 , 0
       0  4164.7      28               0
Permanent Ineff=
       F       F
Bank Sta=4936.5,5072.3
XS Rating Curve= 0 ,0
Exp/Cntr=0.3,0.1

Type RM Length L Ch R = 1 ,37339.3 ,390.6,690.4,954.6
BEGIN DESCRIPTION:
Cross Section 37339.3
END DESCRIPTION:
XS GIS Cut Line= 6
      3173589.31     13856262.13      3172288.94     13856054.49
      3172034.67     13856176.95      3172001.59     13856726.16
      3171113.38     13856958.97        3169809.     13857662.15
#Sta/Elev= 30
    3259    31.9  3656.4    30.8  3716.4      30  3766.4    25.8  3876.4    28.1
  3976.4    26.9  4096.4    29.6  4156.4    26.9  4296.4    30.2  4858.4    24.2
  4878.4    22.3  4895.5   24.32  4912.8   24.16  4940.6     .89  4991.4  -13.55
  5008.8  -20.46  5023.5  -15.84  5059.3     .95  5080.2    7.16  5108.4     9.2
  5285.4    9.96  5629.4     5.1  6079.4     5.2  6109.8    7.18  6179.4    11.7
  6249.4    20.4  6577.6    29.4  7216.5    29.7  7236.5    28.1  7820.1    31.3
#Mann= 6 , 1 , 0
    3259      .1       0  4895.5     .14       0  4912.8    .035       0
  5080.2     .14       0  5285.4     .14       0  6109.8      .2       0
#XS Ineff= 2 , 0
       0  4296.4    30.2               0
Permanent Ineff=
       F       F
Bank Sta=4912.8,5080.2
XS Rating Curve= 0 ,0
Exp/Cntr=0.3,0.1

Type RM Length L Ch R = 1 ,36648.9 ,343.5,595.1,701.5
BEGIN DESCRIPTION:
Cross Section 36648.9-Interpolated
END DESCRIPTION:
XS GIS Cut Line= 6
      3173648.19      13856248.4      3172589.33     13856022.49
      3171937.02     13856022.49      3171264.64     13856433.95
      3170522.02     13856454.02      3170119.98      13856669.6
#Sta/Elev= 30
    2635    31.5    2765    29.1    2815    31.2  3181.4    30.9  3281.4    29.5
  3331.4    25.7  3601.4    29.7  3811.4    26.3  3906.3    28.7  4380.6   23.92
  4681.5    19.1  4781.5    11.9  4921.5    10.5  4926.8    6.31  4935.7   -2.68
  4955.2  -10.56  4979.9  -18.14    5000   -20.7  5063.5   -1.93  5079.8    8.58
  5190.3     5.5  5230.3    10.2  5343.6    11.1  5473.6    19.1  5663.6    20.1
  5763.6    23.8  6023.6    27.6  6086.4    26.3  6243.8   28.68  6366.4      30
#Mann= 5 , 1 , 0
    2635      .1       0  4380.6     .14       0  4926.8     .04       0
  5079.8     .14       0  6243.8     .03       0
Bank Sta=4926.8,5079.8
XS Rating Curve= 0 ,0
Exp/Cntr=0.3,0.1

Type RM Length L Ch R = 1 ,36053.8 ,754,776.5,899.9
BEGIN DESCRIPTION:
Cross Section 36053.8
END DESCRIPTION:
XS GIS Cut Line= 6
      3173407.13     13856200.12      3172466.07     13855877.36
      3171897.09     13855855.88      3171397.88      13855753.9
      3170737.64     13855850.52      3170177.61     13855855.22
#Sta/Elev= 30
    3063    32.1  3324.6    29.8  3399.6      26  3504.6    25.6  3569.6    28.7
  3964.6    28.5  4059.6      26    4511    24.4  4554.2   22.65  4745.4    20.7
  4880.4      10    4896    6.64  4926.8    6.11  4935.7   -2.88  4955.2  -10.76
  4979.9  -18.34    5000   -20.9  5063.5   -2.13  5068.9     .81    5073     5.3
  5079.8    8.38  5135.4     9.2  5184.9       6  5259.9     7.3  5319.9     5.1
  5394.9    16.1  5546.6    17.5  5722.2   24.85  5840.7    29.6  6370.7    31.6
#Mann= 5 , 1 , 0
    3063      .1       0  4554.2     .14       0  4926.8    .035       0
  5079.8     .14       0  5722.2      .1       0
Bank Sta=4926.8,5079.8
XS Rating Curve= 0 ,0
Exp/Cntr=0.3,0.1

Type RM Length L Ch R = 1 ,35277.3 ,245.5,239.6,188
BEGIN DESCRIPTION:
Cross Section 35277.3-Interpolated
END DESCRIPTION:
XS GIS Cut Line= 6
      3173305.15     13855104.99      3172312.59     13855065.28
      3171776.61     13855078.52      3171406.05     13854893.24
      3171002.41     13854807.22      3170083.37     13854851.53
#Sta/Elev= 30
  3327.6    30.7  3813.2   28.88  3977.6    29.5  4167.6    24.6  4277.6      24
    4331    16.5    4391      14    4411     7.8    4461     4.9    4681     6.7
    4711     4.6    4801     5.6  4867.1     9.4  4887.1     8.5  4891.9    3.09
  4913.5     .67  5008.3   -20.2  5051.8   -4.43  5112.2    4.18  5227.8    23.6
  5316.8   27.35  5342.1    28.7  5784.8    27.8  5854.8      25  5874.8    26.6
  5964.8    24.3  6024.8    26.8  6044.8    25.2  6384.8    31.7  6605.8    30.3
#Mann= 7 , 1 , 0
  3327.6      .2       0  3327.6      .1       0  3813.2     .14       0
  4891.9    .035       0  5112.2     .14       0  5316.8      .1       0
  6605.8      .2       0
#XS Ineff= 2 , 0
       0                  5622.1       0    28.5
Permanent Ineff=
       F       F
Bank Sta=4891.9,5112.2
XS Rating Curve= 0 ,0
Exp/Cntr=0.5,0.3

Type RM Length L Ch R = 1 ,35037.7 ,135,135,135
BEGIN DESCRIPTION:
Upstream Section of Bridge/Culvert/Weir
END DESCRIPTION:
XS GIS Cut Line= 6
      3173360.37     13854974.89      3173071.77     13854914.64
      3171958.15      13854874.9      3171003.72     13854601.33
      3170719.78     13854617.56       3170013.9      13854765.7
#Sta/Elev= 30
  3385.7      32  3895.2    26.6  4065.2    27.5    4091      31    4122   31.27
    4184   28.66  4415.4   26.78  4497.4    23.7  4615.9   10.66  4891.9    5.26
  4913.5    2.84  4936.8   -3.09  4990.2  -20.18  5008.3  -18.03  5051.8   -2.26
  5086.6    2.62  5098.1    6.37  5112.2    6.35  5190.8    7.23  5249.6   25.12
  5361.7   27.84  5719.3    28.9  6064.6    26.2  6124.6    23.4  6279.6    24.3
  6384.6    28.9  6594.6    27.5  6659.6    30.4  6729.9    30.5  6799.9    29.6
#Mann= 7 , 1 , 0
  3385.7      .2       0  3385.7      .1       0    4122     .14       0
  4891.9    .035       0  5112.2     .14       0  5361.7      .1       0
  6729.9      .2       0
#XS Ineff= 2 , 0
       0    4468    28.6    5275       0    28.5
Permanent Ineff=
       F       F
Bank Sta=4891.9,5112.2
XS Rating Curve= 0 ,0
Exp/Cntr=0.5,0.3

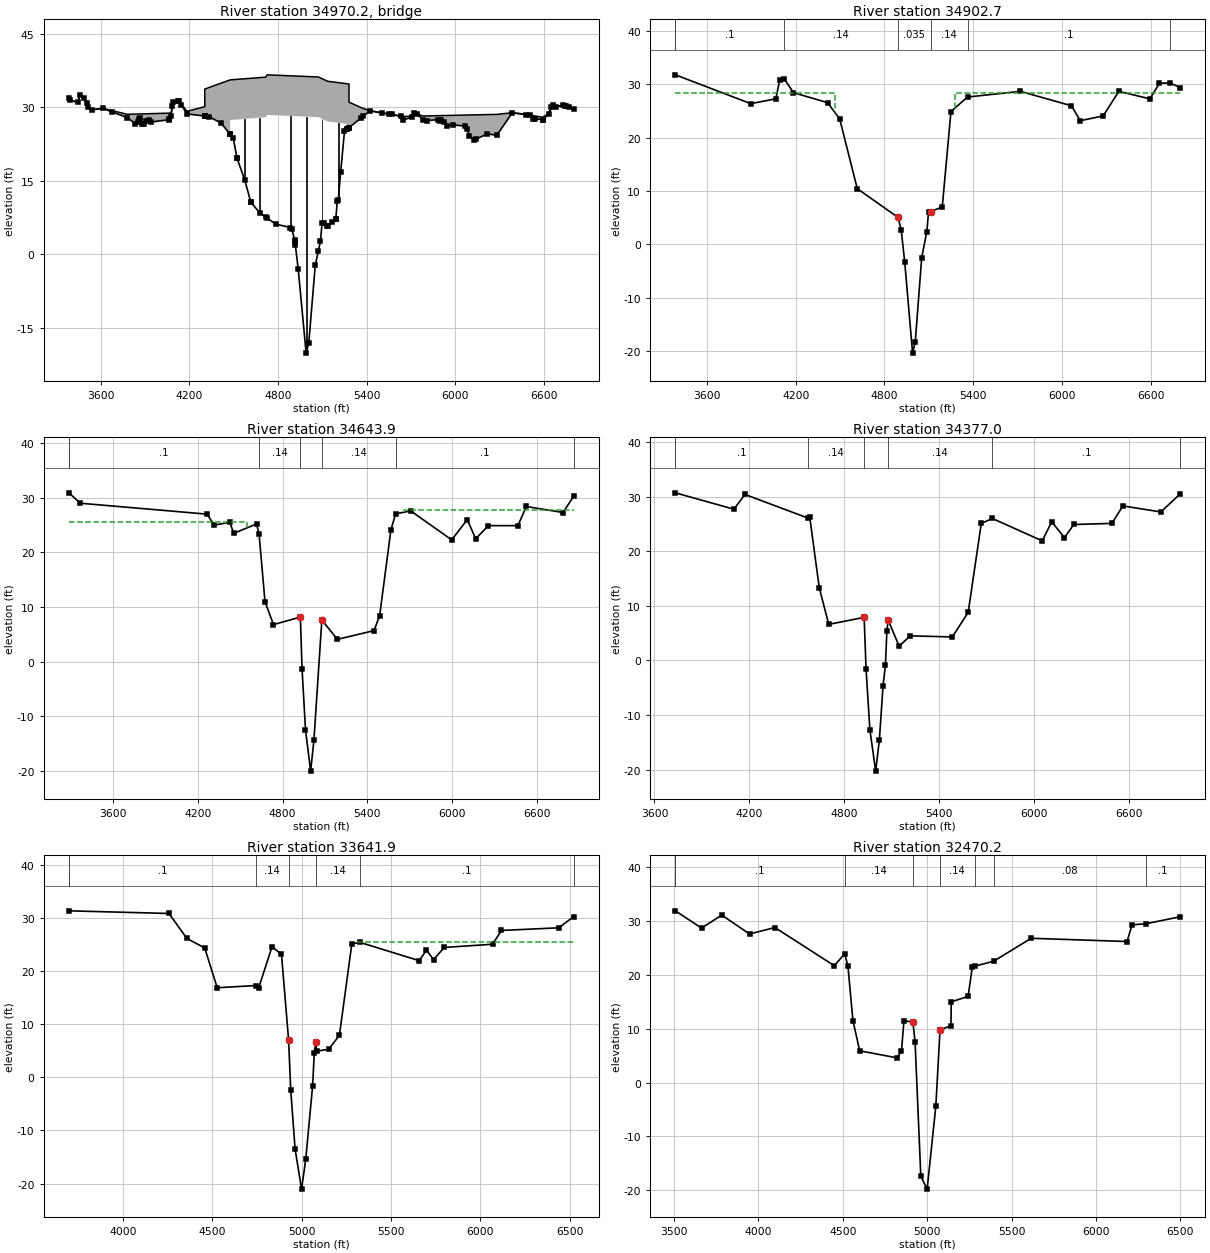
Type RM Length L Ch R = 3 ,34970.2 ,,,
BEGIN DESCRIPTION:
WOODFOREST BOULEVARD
Structure ID: P00-9
END DESCRIPTION:
Bridge Culvert--1,0,-1,-1, 0
Deck Dist Width WeirC Skew NumUp NumDn MinLoCord MaxHiCord MaxSubmerge Is_Ogee
10,115,2.6,0, 60, 60, , , 0.95, 0, 1,1,,
  3385.7  3395.7  3445.7  3460.7  3485.7  3515.7  3540.7  3615.7  3780.2  3835.2
  3865.2  3880.2  3895.2  3910.2  3925.2  3940.2  4065.2    4076    4091  4128.9
    4184 4304.59  4304.7  4415.4 4476.91    4477  4717.1  4726.5  5073.1  5134.3
 5265.89    5266  5279.8    5280 5280.11  5374.7  5421.8  5633.3    5644  5704.3
  5719.3  5779.3  5805.4  5905.4  5940.4  6064.6  6079.6  6094.6  6124.6  6214.6
  6279.6  6384.6  6504.6  6524.6  6588.9  6629.6  6659.6  6679.6  6729.9  6799.9
      32    31.5      31    32.5      32      30    29.5    29.8   28.59   28.63
   28.66   28.67   28.68    28.7   28.71   28.72   28.83   28.84   31.01   31.34
    29.2   30.14   33.74   34.96   35.62   35.62   36.18   36.65   36.21   35.34
   34.83   34.83   34.78   34.66   31.06    29.8   29.34   28.18   28.16    28.2
   28.91   28.25   28.26   28.33   28.35   28.43   28.44   28.45   28.47   28.53
   28.57   28.91   28.49   28.32      28   28.71   30.41   30.11   30.51    29.6
      32    31.5      31    32.5      32      30    29.5    29.8    27.9    26.7
    27.8    26.7    26.6    27.3    27.4      27    27.5    28.2      31   31.33
   28.66   28.24   28.24   26.78   24.47   27.42   27.98   28.45   28.01   27.14
   26.63   25.52   25.85   25.86   25.86   28.16    29.3   28.17   27.41      28
    28.9    27.5    27.3    27.5    26.2    26.2    25.5    24.1    23.4    24.6
    24.3    28.9    28.4    27.7   27.52    28.7    30.4    30.1    30.5    29.6
  3385.7  3395.7  3445.7  3460.7  3485.7  3515.7  3540.7  3615.7  3780.2  3835.2
  3865.2  3880.2  3895.2  3910.2  3925.2  3940.2  4065.2    4076    4091  4128.9
    4184 4304.59  4304.7  4415.4 4476.91    4477  4717.1  4726.5  5073.1  5134.3
 5265.89    5266  5279.8    5280 5280.11  5374.7  5421.8  5633.3    5644  5704.3
  5719.3  5779.3  5805.4  5905.4  5940.4  6064.6  6079.6  6094.6  6124.6  6214.6
  6279.6  6384.6  6504.6  6524.6  6588.9  6629.6  6659.6  6679.6  6729.9  6799.9
      32    31.5      31    32.5      32      30    29.5    29.8   28.59   28.63
   28.66   28.67   28.68    28.7   28.71   28.72   28.83   28.84   31.01   31.34
    29.2   30.14   33.74   34.96   35.62   35.62   36.18   36.65   36.21   35.34
   34.83   34.83   34.78   34.66   31.06    29.8   29.34   28.18   28.16    28.2
   28.91   28.25   28.26   28.33   28.35   28.43   28.44   28.45   28.47   28.53
   28.57   28.91   28.49   28.32      28   28.71   30.41   30.11   30.51    29.6
   31.77   31.27   30.77   32.27   31.77   29.77   29.27   29.57   27.67   26.47
   27.57   26.47   26.37   27.07   27.17   26.77   27.27   27.97   30.77    31.1
   28.43   28.01   28.01   26.55   24.24   27.19   27.75   28.22   27.78   26.91
    26.4   25.29   25.62   25.63   25.63   27.93   29.07   27.94   27.18   27.77
   28.67   27.27   27.07   27.27   25.97   25.97   25.27   23.87   23.17   24.37
   24.07   28.67   28.17   27.47   27.29   28.47   30.17   29.87   30.27   29.37
Pier Skew, UpSta & Num, DnSta & Num=  ,4575.7, 2 ,4575.7, 2 , 0 , 0 , 0 ,,
       5       5
   13.82   28.48
       5       5
   13.59   28.25
Pier Skew, UpSta & Num, DnSta & Num=  ,4676.2, 2 ,4676.2, 2 , 0 , 0 , 0 ,,
       5       5
    7.42   28.84
       5       5
    7.19   28.61
Pier Skew, UpSta & Num, DnSta & Num=  ,4884, 2 ,4884, 2 , 0 , 0 , 0 ,,
       5       5
     4.4   29.13
       5       5
    4.17    28.9
Pier Skew, UpSta & Num, DnSta & Num=  ,4990.2, 2 ,4990.2, 2 , 0 , 0 , 0 ,,
       5       5
  -20.88      29
       5       5
  -21.11   28.77
Pier Skew, UpSta & Num, DnSta & Num=  ,5098.1, 2 ,5098.1, 2 , 0 , 0 , 0 ,,
       5       5
    4.55   28.69
       5       5
    4.32   28.46
Pier Skew, UpSta & Num, DnSta & Num=  ,5207.2, 2 ,5207.2, 2 , 0 , 0 , 0 ,,
       5       5
    9.98   27.87
       5       5
    9.75   27.64
Abutment Skew #Up #Dn= , 2 , 2
  4476.8    4616
   27.42   10.66
  4476.8    4616
   27.19   10.43
Abutment Skew #Up #Dn= , 2 , 2
  5190.8 5266.09
    7.23   26.63
  5190.8 5266.09
       7    26.4
BR Coef= 1 , 1 , 0 ,1.25, 0 ,,,0.8,0,2,0,
WSPro=,,,, 1 ,,,, 0 ,,,, 0 ,,,,-1 ,-1 ,-1 , 0 , 0 , 0 , 0 , 0
BR U #Sta/Elev= 118
  3385.7      32  3395.7    31.5  3445.7      31  3460.7    32.5  3485.7      32
  3505.7    30.9  3515.7      30  3540.7    29.5  3615.7    29.8  3680.5   29.05
  3780.2    27.9  3835.2    26.7  3850.2    27.1  3860.2    27.7  3865.2    27.8
  3880.2    26.7  3895.2    26.6  3910.2    27.3  3925.2    27.4  3940.2      27
  4065.2    27.5    4066    27.6    4076    28.2    4086    30.3    4091      31
    4122   31.27  4128.9   31.33  4145.3   30.54    4184   28.66 4304.59   28.24
  4304.7   28.24 4304.81   28.24  4307.4   28.23  4332.2   28.14  4415.4   26.78
  4474.7   24.55 4476.91   24.47    4477   24.47  4497.4    23.7  4522.1   19.72
  4522.4   19.67  4575.7    15.1  4615.9   10.66    4616   10.66  4676.2    8.47
  4717.1     7.6  4726.5     7.4  4784.6    6.16    4884    5.47  4891.9    5.26
  4913.5    2.84  4914.7    2.53  4917.1    1.92  4936.8   -3.09  4990.2  -20.18
  5008.3  -18.03  5051.8   -2.26  5073.1     .73  5086.6    2.62  5098.1    6.37
  5112.2    6.35  5134.3    5.81  5136.7    5.75    5167    6.64  5190.7    7.23
  5190.8    7.23  5200.7   10.93  5207.2   11.01    5224    16.9  5249.6   25.12
 5265.89   25.52    5266   25.52  5279.8   25.85 5279.89   25.86    5280   25.86
 5280.11   25.86  5361.7   27.84  5374.7   28.16  5421.8    29.3  5502.1   28.84
    5550   28.65  5570.9   28.57  5633.3   28.17    5644   27.41  5704.3      28
  5719.3    28.9  5739.3    28.7  5779.3    27.5  5805.4    27.3  5880.4    27.5
  5895.4    27.3  5905.4    27.5  5925.4      27  5940.4    26.2  5984.6    26.4
  6064.6    26.2  6079.6    25.5  6094.6    24.1  6124.6    23.4  6139.6    23.5
  6214.6    24.6  6279.6    24.3  6384.6    28.9  6478.9   28.51  6504.6    28.4
  6524.6    27.7  6538.9   27.66  6588.9   27.52  6594.6    27.5  6629.6    28.7
  6649.6    30.1  6659.6    30.4  6679.6    30.1  6729.9    30.5  6738.9   30.38
  6748.9   30.26  6768.9      30  6799.9    29.6
BR U #Mann= 7
  3385.7      .2  3385.7      .1    4122     .14  4891.9    .035  5112.2     .14
  5361.7      .1  6729.9      .2
BR U Banks=4891.9,5112.2
BR D #Sta/Elev= 118
  3385.7   31.77  3395.7   31.27  3445.7   30.77  3460.7   32.27  3485.7   31.77
  3505.7   30.67  3515.7   29.77  3540.7   29.27  3615.7   29.57  3680.5   28.82
  3780.2   27.67  3835.2   26.47  3850.2   26.87  3860.2   27.47  3865.2   27.57
  3880.2   26.47  3895.2   26.37  3910.2   27.07  3925.2   27.17  3940.2   26.77
  4065.2   27.27    4066   27.37    4076   27.97    4086   30.07    4091   30.77
    4122   31.04  4128.9    31.1  4145.3   30.31    4184   28.43 4304.59   28.01
  4304.7   28.01 4304.81   28.01  4307.4      28  4332.2   27.91  4415.4   26.55
  4474.7   24.32 4476.91   24.24    4477   24.24  4497.4   23.47  4522.1   19.49
  4522.4   19.44  4575.7   14.87  4615.9   10.43    4616   10.43  4676.2    8.24
  4717.1    7.37  4726.5    7.17  4784.6    5.93    4884    5.24  4891.9    5.03
  4913.5    2.61  4914.7     2.3  4917.1    1.69  4936.8   -3.32  4990.2  -20.41
  5008.3  -18.26  5051.8   -2.49  5073.1      .5  5086.6    2.39  5098.1    6.14
  5112.2    6.12  5134.3    5.58  5136.7    5.52    5167    6.41  5190.7       7
  5190.8       7  5200.7    10.7  5207.2   10.78    5224   16.67  5249.6   24.89
 5265.89   25.29    5266   25.29  5279.8   25.62 5279.89   25.63    5280   25.63
 5280.11   25.63  5361.7   27.61  5374.7   27.93  5421.8   29.07  5502.1   28.61
    5550   28.42  5570.9   28.34  5633.3   27.94    5644   27.18  5704.3   27.77
  5719.3   28.67  5739.3   28.47  5779.3   27.27  5805.4   27.07  5880.4   27.27
  5895.4   27.07  5905.4   27.27  5925.4   26.77  5940.4   25.97  5984.6   26.17
  6064.6   25.97  6079.6   25.27  6094.6   23.87  6124.6   23.17  6139.6   23.27
  6214.6   24.37  6279.6   24.07  6384.6   28.67  6478.9   28.28  6504.6   28.17
  6524.6   27.47  6538.9   27.43  6588.9   27.29  6594.6   27.27  6629.6   28.47
  6649.6   29.87  6659.6   30.17  6679.6   29.87  6729.9   30.27  6738.9   30.15
  6748.9   30.03  6768.9   29.77  6799.9   29.37
BR D #Mann= 7
  3385.7      .2  3385.7      .1    4122     .14  4891.9    .035  5112.2     .14
  5361.7      .1  6729.9      .2
BR D Banks=4891.9,5112.2
BC Design=,, 0 ,, 0 ,,,,,,
BC HTab HWMax=32.5
BC Use User HTab Curves=0
BC User HTab FreeFlow(D)= 0

Type RM Length L Ch R = 1 ,34902.7 ,258.8,258.8,258.8
BEGIN DESCRIPTION:
Downstream Section of Bridge/Culvert/Weir
END DESCRIPTION:
XS GIS Cut Line= 6
      3173420.74     13854854.15      3173132.15      13854793.9
      3172018.53     13854754.16       3171064.1     13854480.59
      3170780.16     13854496.82      3170074.28     13854644.95
#Sta/Elev= 30
  3385.7   31.79  3895.2   26.39  4065.2   27.29    4091   30.79    4122   31.06
    4184   28.45  4415.4   26.57  4497.4   23.49  4615.9   10.45  4891.9    5.05
  4913.5    2.63  4936.8    -3.3  4990.2  -20.39  5008.3  -18.24  5051.8   -2.47
  5086.6    2.41  5098.1    6.16  5112.2    6.14  5190.8    7.02  5249.6   24.91
  5361.7   27.63  5719.3   28.69  6064.6   25.99  6124.6   23.19  6279.6   24.09
  6384.6   28.69  6594.6   27.29  6659.6   30.19  6729.9   30.29  6799.9   29.39
#Mann= 7 , 1 , 0
  3385.7      .2       0  3385.7      .1       0    4122     .14       0
  4891.9    .035       0  5112.2     .14       0  5361.7      .1       0
  6729.9      .2       0
#XS Ineff= 2 , 0
       0    4468    28.4    5275       0    28.3
Permanent Ineff=
       F       F
Bank Sta=4891.9,5112.2
XS Rating Curve= 0 ,0
Exp/Cntr=0.5,0.3

Type RM Length L Ch R = 1 ,34643.9 ,403.9,266.9,90.6
BEGIN DESCRIPTION:
Cross Section 34643.9-Interpolated
END DESCRIPTION:
XS GIS Cut Line= 6
      3173549.98     13854635.18      3173007.38     13854502.84
      3171776.61     13854430.05      3171431.41     13854419.28
      3171106.92     13854403.05      3170011.51     13854599.89
#Sta/Elev= 30
  3287.2    30.9  3367.2      29  4265.7      27  4315.7      25  4425.7    25.5
  4455.7    23.5  4615.7    25.2  4633.8   23.37  4675.7      11  4735.7     6.8
  4926.1    8.17  4938.2   -1.31  4962.5  -12.43  4998.9     -20  5022.3  -14.31
  5078.3    7.64  5188.6     4.1  5447.4     5.7  5487.4     8.4  5567.4    24.1
  5600.3   27.05  5707.2    27.6  5997.9    22.3  6107.9      26  6167.9    22.5
  6257.9    24.9  6466.4    24.9  6526.4    28.4  6786.4    27.3  6861.8    30.3
#Mann= 7 , 1 , 0
  3287.2      .2       0  3287.2      .1       0  4633.8     .14       0
  4926.1    .035       0  5078.3     .14       0  5600.3      .1       0
  6861.8      .2       0
#XS Ineff= 2 , 0
       0  4545.7    25.5  5657.2       0    27.7
Permanent Ineff=
       F       F
Bank Sta=4926.1,5078.3
XS Rating Curve= 0 ,0
Exp/Cntr=0.3,0.1

Type RM Length L Ch R = 1 ,34377.0 ,1013.5,735.1,367.7
BEGIN DESCRIPTION:
Cross Section 34377.0-Interpolated
END DESCRIPTION:
XS GIS Cut Line= 5
       3173024.4     13853859.25      3171962.53      13854082.8
      3171599.27     13854306.35      3171171.82     13854338.15
      3169938.48     13854553.77
#Sta/Elev= 30
  3732.3    30.7  4102.3    27.7  4172.3    30.4    4568   26.11  4582.3    26.2
  4642.3    13.3  4702.3     6.6  4926.1    7.89  4938.2   -1.59  4962.5  -12.71
  4998.9  -20.28  5022.3  -14.59  5045.7   -4.63  5060.8    -.77    5070    5.47
  5078.3    7.36  5147.4     2.6  5217.4     4.5    5484     4.3    5584     8.8
  5666.9    25.1  5737.1      26  6052.5    21.9  6112.5    25.4  6192.5    22.5
  6252.5    24.9  6492.5    25.1  6562.5    28.3  6802.5    27.2  6924.7    30.5
#Mann= 7 , 1 , 0
  3732.3      .2       0  3732.3      .1       0    4568     .14       0
  4926.1     .04       0  5078.3     .14       0  5737.1      .1       0
  6924.7      .2       0
#XS Ineff= 2 , 0
       0  4172.3    30.4  5737.1       0      26
Permanent Ineff=
       F       F
Bank Sta=4926.1,5078.3
XS Rating Curve= 0 ,0
Exp/Cntr=0.3,0.1

Type RM Length L Ch R = 1 ,33641.9 ,936.4,1171.7,1378.2
BEGIN DESCRIPTION:
Cross Section 33641.9
END DESCRIPTION:
XS GIS Cut Line= 4
      3171408.61     13852903.58      3171108.76     13853921.47
       3171133.7     13854281.76      3169754.31     13854535.87
#Sta/Elev= 30
  3696.8    31.4  4256.8    30.9  4356.8    26.2  4456.8    24.4  4526.8    16.9
  4743.3   17.32  4757.9    16.8  4833.7   24.64  4886.5   23.19  4926.1    7.11
  4938.2   -2.37  4962.5  -13.49  4998.9  -21.06  5022.3  -15.37  5060.8   -1.55
    5070    4.69  5078.3    6.58  5082.8    4.95  5149.9    5.29  5210.6    7.92
  5280.3   25.22  5327.5   25.43  5657.6      22  5697.6      24  5737.6    22.2
  5797.6    24.5  6067.6    25.1  6117.6    27.7  6437.6    28.2  6521.8    30.3
#Mann= 7 , 1 , 0
  3696.8      .2       0  3696.8      .1       0  4743.3     .14       0
  4926.1    .035       0  5078.3     .14       0  5327.5      .1       0
  6521.8      .2       0
#XS Ineff= 2 , 0
       0  4833.7   24.64  5317.1       0   25.53
Permanent Ineff=
       F       F
Bank Sta=4926.1,5078.3
XS Rating Curve= 0 ,0
Exp/Cntr=0.3,0.1

Type RM Length L Ch R = 1 ,32470.2 ,1126,1115.9,1043.2
BEGIN DESCRIPTION:
Cross Section 32470.2
END DESCRIPTION:
XS GIS Cut Line= 6
      3171351.09      13852917.6      3171091.72      13853129.2
      3170600.29     13853333.96      3170224.88     13853620.63
      3169651.54      13854173.5      3169367.85     13854980.07
#Sta/Elev= 30
  3508.2    31.9  3663.2    28.7  3783.2    31.1  3947.9    27.6  4097.9    28.8
  4450.3    21.7    4511   23.93  4530.3    21.7  4560.3    11.5  4600.3     5.9
  4820.3     4.6  4847.7     5.8  4862.5   11.45  4915.4   11.28  4928.6    7.49
  4962.4  -17.38    5000  -19.79  5051.4   -4.37  5076.4    9.84  5141.1   10.52
  5142.7      15  5242.7      16  5267.7    21.5  5280.9   21.61  5393.5   22.53
  5616.2    26.8  6184.2    26.2  6214.2    29.3  6294.4   29.49  6499.2    30.8
#Mann= 8 , 1 , 0
  3508.2      .2       0  3508.2      .1       0    4511     .14       0
  4915.4    .035       0  5076.4     .14       0  5280.9      .1       0
  5393.5     .08       0  6294.4      .1       0
Bank Sta=4915.4,5076.4
XS Rating Curve= 0 ,0
Exp/Cntr=0.3,0.1