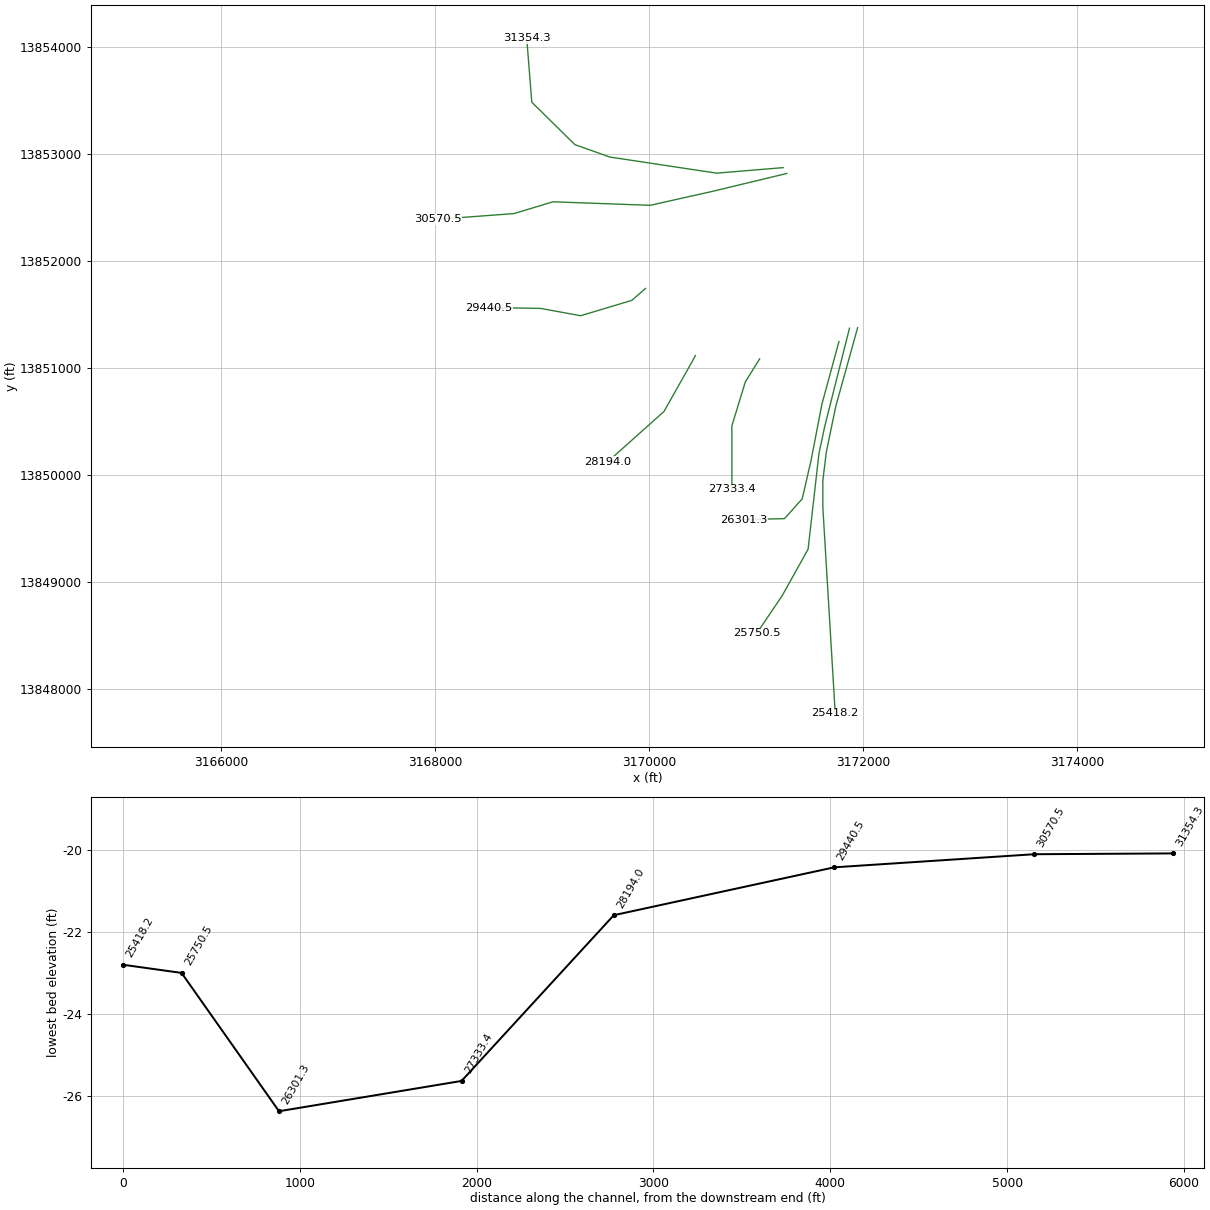
HEC-RAS study P100-00-00.prj: P100-00-00

--- P100-00-00.g01 (geometry) --- (continued)

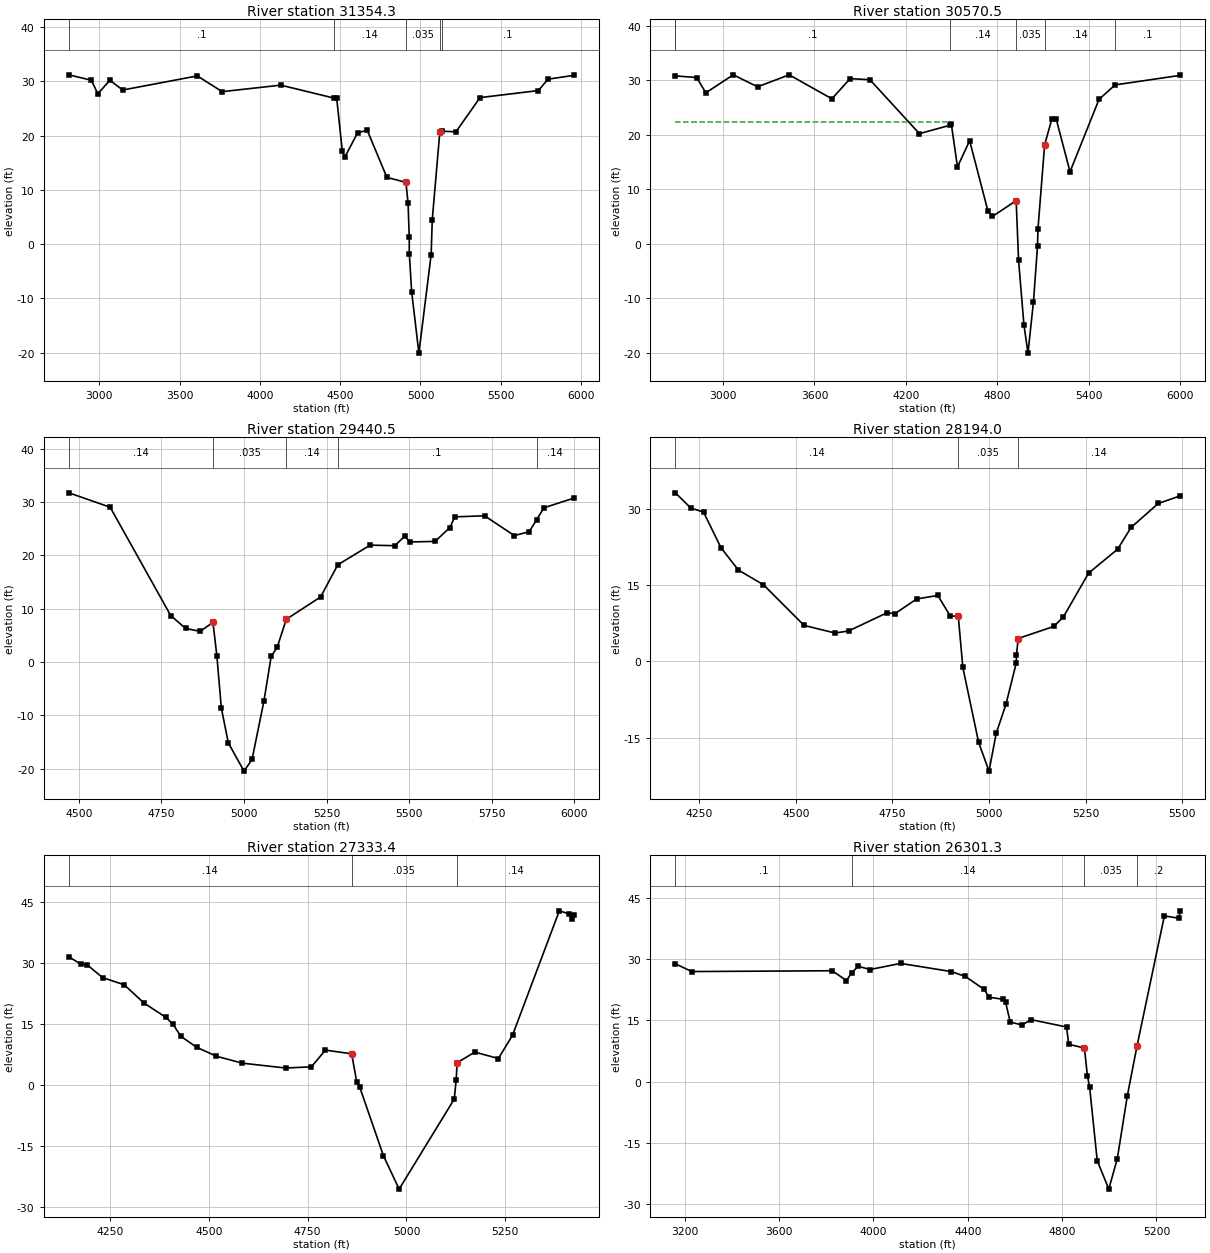
Type RM Length L Ch R = 1 ,31354.3 ,544.6,783.8,985.5
BEGIN DESCRIPTION:
Cross Section 31354.3
END DESCRIPTION:
XS GIS Cut Line= 6
      3171249.84     13852869.96      3170627.59     13852818.63
      3169631.06      13852968.8      3169303.44     13853084.83
      3168900.73     13853480.71      3168853.34      13854077.2
#Sta/Elev= 30
  2811.1    31.2  2951.1    30.2  2991.1    27.7  3066.1    30.2  3146.1    28.4
  3610.4      31  3765.4    28.1  4130.4    29.3    4463    26.9  4478.2    26.9
  4513.2    17.2  4528.2      16  4608.2    20.5  4668.2      21  4790.8    12.3
  4909.3   11.39  4922.5    7.61    4930    1.33  4930.3   -1.73    4945   -8.76
    4990  -20.08  5066.3   -1.92  5073.3    4.51  5120.2   20.61  5136.4   20.81
  5220.8    20.7  5370.5      27  5733.9    28.3  5793.9    30.4  5953.9    31.1
#Mann= 5 , 1 , 0
  2811.1      .1       0    4463     .14       0  4909.3    .035       0
  5120.2     .14       0  5136.4      .1       0
Bank Sta=4909.3,5120.2
XS Rating Curve= 0 ,0
Exp/Cntr=0.3,0.1

Type RM Length L Ch R = 1 ,30570.5 ,1086,1130,1160.4
BEGIN DESCRIPTION:
Cross Section 30570.5
END DESCRIPTION:
XS GIS Cut Line= 6
      3171284.18     13852815.66      3170586.64       13852648.
      3170006.46     13852518.31        3169099.     13852551.21
      3168733.98     13852441.12      3168023.29     13852388.01
#Sta/Elev= 30
  2686.7    30.8  2826.7    30.5  2886.7    27.7  3066.7      31  3226.7    28.8
  3434.1      31  3714.1    26.6  3834.1    30.3  3964.1    30.1  4288.6    20.2
  4486.8   21.72  4498.6    21.9  4538.6    14.1  4618.6    18.9  4738.6       6
  4768.6       5    4924     7.9  4939.8   -3.08  4975.1  -14.93  5001.5   -20.1
  5037.6  -10.67  5064.1    -.46  5067.1    2.73    5111   18.18  5157.6    22.8
  5187.6    22.8  5277.6    13.2    5468    26.5  5573.6   29.15  6000.7    30.9
#Mann= 6 , 1 , 0
  2686.7      .2       0  2686.7      .1       0  4486.8     .14       0
    4924    .035       0    5111     .14       0  5573.6      .1       0
#XS Ineff= 2 , 0
       0  4468.6    22.4  5187.6       0    22.8
Permanent Ineff=
       F       F
Bank Sta=4924,5111
XS Rating Curve= 0 ,0
Exp/Cntr=0.3,0.1

Type RM Length L Ch R = 1 ,29440.5 ,1090.2,1246.5,1391.2
BEGIN DESCRIPTION:
Cross Section 29440.5
END DESCRIPTION:
XS GIS Cut Line= 5
      3169962.71     13851741.83      3169835.83     13851630.99
      3169358.04     13851487.66      3168982.64     13851555.91
      3168502.77       13851564.
#Sta/Elev= 30
  4469.7    31.7  4594.7      29  4778.2     8.7  4823.2     6.3  4867.2    5.75
    4906    7.44  4917.9    1.09  4931.3   -8.57  4952.4  -15.12    5000  -20.42
  5024.3  -18.24  5060.5   -7.25  5082.2    1.05  5100.6    2.79  5128.1    8.02
    5232    12.2    5284   18.22    5382    21.9    5457    21.8    5487    23.6
    5502    22.5  5578.5    22.6  5623.5    25.2  5638.5    27.2  5728.5    27.4
  5818.5    23.7  5863.5    24.4    5886   26.65  5908.5    28.9  5998.5    30.7
#Mann= 5 , 1 , 0
  4469.7     .14       0    4906    .035       0  5128.1     .14       0
    5284      .1       0    5886     .14       0
#XS Ineff= 2 , 0
       0                  5728.5       0    27.4
Permanent Ineff=
       F       F
Bank Sta=4906,5128.1
XS Rating Curve= 0 ,0
Exp/Cntr=0.3,0.1

Type RM Length L Ch R = 1 ,28194.0 ,629.9,860.6,981.7
BEGIN DESCRIPTION:
Cross Section 28194.0
END DESCRIPTION:
XS GIS Cut Line= 5
      3170429.29     13851115.72      3170402.35     13851064.47
      3170136.15     13850593.51      3169631.06     13850143.03
      3169608.58     13850123.13
#Sta/Elev= 30
  4188.8    33.2  4228.8    30.2  4261.7    29.4  4306.7    22.4  4351.7      18
  4416.7    15.1  4521.7     7.1  4601.7     5.6  4636.7       6  4736.7     9.6
  4756.7     9.4  4812.7    12.3  4867.7      13  4899.6    8.96  4920.6    8.89
  4932.3   -1.16  4973.1  -15.91    5000  -21.59  5018.8  -14.11  5043.8   -8.46
  5070.3    -.36  5071.1    1.26  5075.5    4.52  5167.7     6.9  5192.7     8.8
  5257.7    17.4  5332.7    22.1  5367.7    26.4  5437.7    31.1  5494.5    32.6
#Mann= 3 , 1 , 0
  4188.8     .14       0  4920.6    .035       0  5075.5     .14       0
Bank Sta=4920.6,5075.5
XS Rating Curve= 0 ,0
Exp/Cntr=0.3,0.1

Type RM Length L Ch R = 1 ,27333.4 ,1273.9,1032.1,726.6
BEGIN DESCRIPTION:
Cross Section 27333.4
END DESCRIPTION:
XS GIS Cut Line= 4
       3171030.4     13851084.89      3170896.51     13850869.94
      3170770.92     13850460.41      3170770.92      13849865.4
#Sta/Elev= 30
  4146.4    31.6  4176.4    29.8  4191.4    29.7  4231.4    26.5  4286.4    24.7
  4336.4    20.2  4391.4    16.7  4409.6      15  4429.6      12  4469.6     9.3
  4519.6     7.1  4584.6     5.4  4694.6     4.2  4759.6     4.5  4795.2    8.61
  4861.4     7.7  4874.2     .87  4881.6    -.44  4941.7  -17.38  4981.5  -25.64
  5120.9   -3.46  5125.8    1.27  5128.1     5.5  5172.9    8.12  5232.5    6.54
  5268.3   12.29  5386.6   42.93  5411.5   42.17    5418      41    5423    41.9
#Mann= 3 , 1 , 0
  4146.4     .14       0  4861.4    .035       0  5128.1     .14       0
Bank Sta=4861.4,5128.1
XS Rating Curve= 0 ,0
Exp/Cntr=0.3,0.1

Type RM Length L Ch R = 1 ,26301.3 ,162.1,550.8,727.4
BEGIN DESCRIPTION:
Cross Section 26301.3
END DESCRIPTION:
XS GIS Cut Line= 6
      3171771.45     13851245.56      3171612.31     13850662.04
      3171511.03     13850137.25      3171428.17     13849778.17
      3171262.46     13849593.29      3170879.07     13849584.01
#Sta/Elev= 30
  3160.8    28.9  3230.8      27  3825.6    27.2  3885.6    24.8  3908.4    26.7
  3935.6    28.3  3985.6    27.5  4115.6      29  4330.1      27  4390.1    25.8
  4470.1    22.6  4490.1    20.7  4550.1    20.2  4560.1    19.6  4580.1    14.6
  4630.1    13.9  4668.6    15.2  4818.6    13.4  4828.2    9.15  4894.5    8.24
  4907.2    1.41  4916.6    -1.4  4948.8  -19.37  4997.8  -26.38  5033.9  -18.91
  5076.1   -3.58  5117.4    8.72  5233.4   40.65    5295   40.09  5300.4    41.9
#Mann= 4 , 1 , 0
  3160.8      .1       0  3908.4     .14       0  4894.5    .035       0
  5117.4      .2       0
Bank Sta=4894.5,5117.4
XS Rating Curve= 0 ,0
Exp/Cntr=0.3,0.1

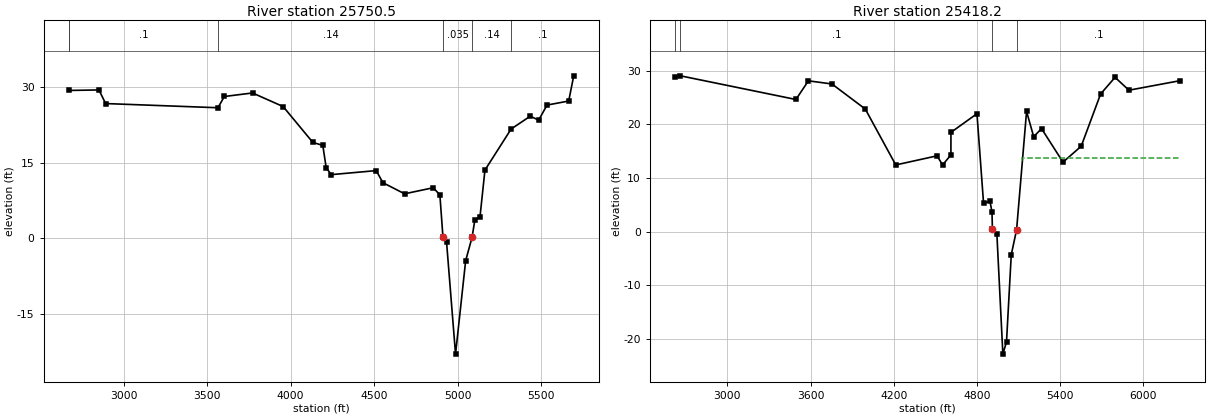
Type RM Length L Ch R = 1 ,25750.5 ,142.1,332.3,440
BEGIN DESCRIPTION:
Cross Section 25750.5-Interpolated
END DESCRIPTION:
XS GIS Cut Line= 6
      3171870.11     13851370.98      3171639.93     13850459.49
      3171584.69      13850201.7      3171483.41     13849308.62
      3171244.03     13848878.96      3171003.67     13848522.46
#Sta/Elev= 30
  2671.4    29.3  2851.4    29.4  2891.4    26.7  3564.3   25.87  3602.8    28.1
  3771.6    28.8  3955.2    26.1  4132.8      19  4192.8    18.4  4212.8      14
  4242.8    12.6  4512.8    13.4  4552.8      11  4682.8     8.8  4854.2      10
  4894.2     8.6  4912.6     .23  4934.3     -.8    4988     -23  5048.7   -4.46
  5087.1     .18  5104.2     3.7  5134.2     4.1  5164.2    13.5  5321.1   21.65
  5436.1    24.2  5486.1    23.4  5536.1    26.4  5666.1    27.2  5696.1    32.2
#Mann= 6 , 1 , 0
  2671.4      .2       0  2671.4      .1       0  3564.3     .14       0
  4912.6    .035       0  5087.1     .14       0  5321.1      .1       0
Bank Sta=4912.6,5087.1
XS Rating Curve= 0 ,0
Exp/Cntr=0.5,0.3

Type RM Length L Ch R = 1 ,25418.2 ,113,113,113
BEGIN DESCRIPTION:
Upstream Section of Bridge/Culvert/Weir
END DESCRIPTION:
XS GIS Cut Line= 6
       3171946.3      13851375.9      3171742.37     13850643.43
      3171652.92     13850211.09      3171621.02      13849948.3
      3171621.23     13849694.94      3171736.83     13847775.22
#Sta/Elev= 30
  2624.5   28.84  2661.2   29.07  3494.5   24.66  3584.5   28.14  3754.5   27.55
  3995.1   22.88  4215.1   12.46  4513.1   14.16  4553.1   12.46  4613.1   14.33
  4613.3   18.53  4801.1   22.01  4848.6    5.35    4895    5.67  4909.5    3.73
  4912.6     .43  4944.7    -.34    4988   -22.8  5014.3  -20.51  5048.7   -4.26
  5087.1     .38  5159.1   22.43  5210.4   17.72  5267.1   19.23    5422   12.98
  5553.4   15.95  5693.4   25.68  5797.7   28.79  5897.7   26.39  6267.7   28.17
#Mann= 4 , 1 , 0
  2624.5      .2       0  2661.2      .1       0  4912.6    .035       0
  5087.1      .1       0
#XS Ineff= 2 , 0
       0    4826    12.4    5129       0    13.8
Permanent Ineff=
       F       F
Bank Sta=4912.6,5087.1
XS Rating Curve= 0 ,0
Exp/Cntr=0.5,0.3