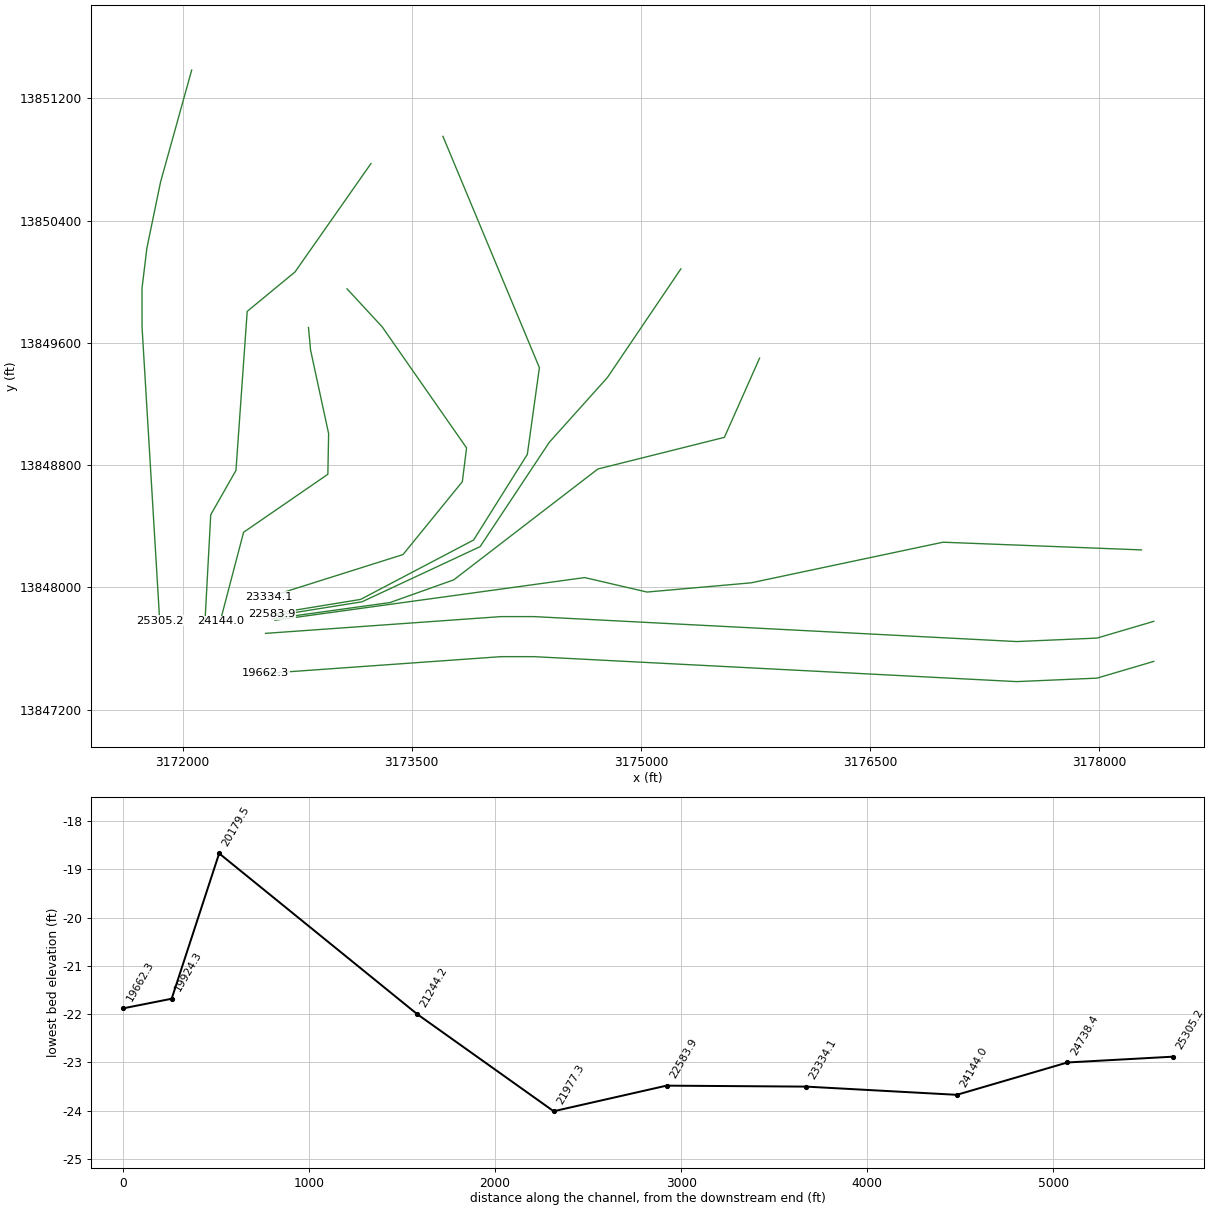
HEC-RAS study P100-00-00.prj: P100-00-00

--- P100-00-00.g01 (geometry) --- (continued)

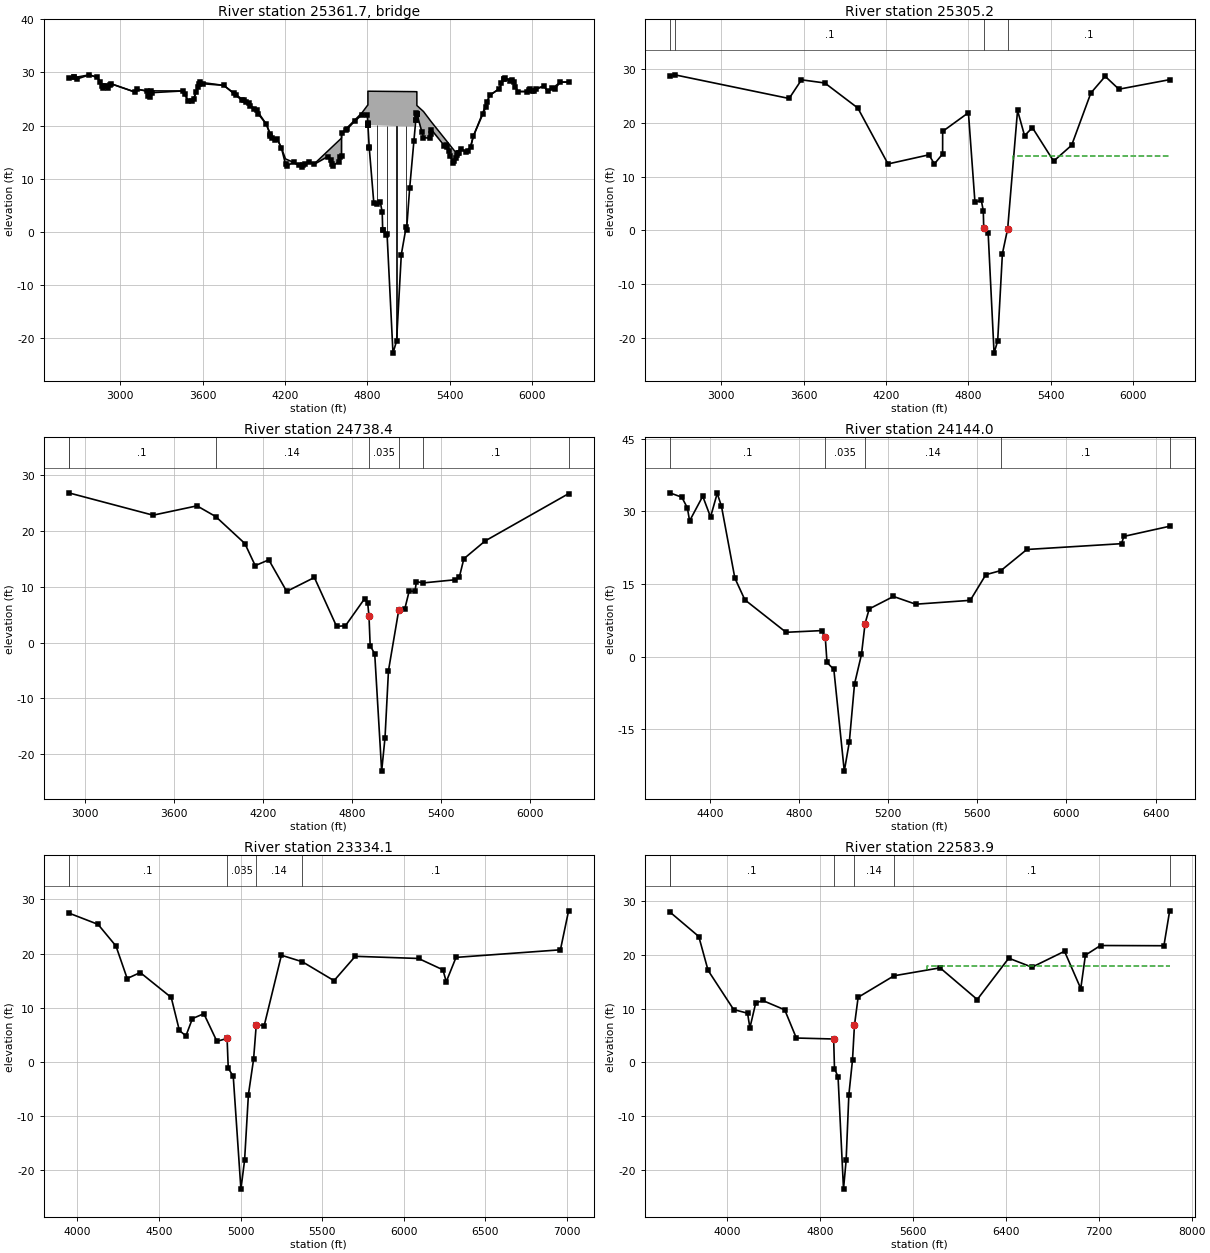
Type RM Length L Ch R = 3 ,25361.7 ,,,
BEGIN DESCRIPTION:
NORMANDY ROAD
Structure ID: P00-8
END DESCRIPTION:
Bridge Culvert--1,0,-1,-1, 0
Deck Dist Width WeirC Skew NumUp NumDn MinLoCord MaxHiCord MaxSubmerge Is_Ogee
10,93,2.6,0, 60, 60, , , 0.95, 0, 1,1,,
  2624.5  2774.5  2834.5  2874.5  2914.5  2934.5  3104.5  3124.5  3194.5  3214.5
  3224.5  3454.5  3494.5  3534.5  3584.5  3754.5  3995.1  4065.1  4105.1  4145.1
  4175.1  4205.1  4265.1  4325.1  4375.1  4413.1  4513.1  4553.1  4593.1  4613.1
  4613.3  4761.9  4801.1 4805.29  4805.4  5140.6 5154.39  5159.1  5162.1 5162.21
  5210.4  5260.6  5267.1    5373    5422  5444.1    5482    5522  5553.4  5573.4
  5693.4  5763.4  5797.7  5857.7  5897.7  5997.7  6087.7  6117.7  6207.7  6267.7
   28.85   29.54   29.04   27.14   27.07   27.85   26.33   26.83   26.49   25.44
   26.53   26.51   24.67   25.04   28.15   27.56    22.9   20.26   17.71   17.45
   15.79   13.73   13.07   12.17   13.17   12.77   15.21   16.19   17.16   17.65
   18.55    22.4   23.75   23.86   26.46   26.38   26.37   26.37   26.37   23.77
   22.64   20.93   20.71   17.29   15.71      15   15.55   15.19   15.97      18
    25.7   26.94    28.8   28.64    26.4   26.43   27.42   26.41   28.16   28.18
   28.85   29.54   29.04   27.14   27.07   27.85   26.33   26.83   26.49   25.44
   26.53   26.51   24.67   25.04   28.15   27.56   22.89   20.25    17.7   17.44
   15.78   12.72   13.06   12.16   13.16   12.71   14.17   12.47   13.23   14.34
   18.54   22.03   22.02   20.15    20.1   19.78   21.09   22.44   22.16   22.15
   17.73   17.61   19.24   16.31   12.99   13.99   15.54      15   15.96   17.99
   25.69   26.93    28.8   28.64    26.4   26.43   27.42   26.41   28.16   28.18
  2624.5  2774.5  2834.5  2874.5  2914.5  2934.5  3104.5  3124.5  3194.5  3214.5
  3224.5  3454.5  3494.5  3534.5  3584.5  3754.5  3995.1  4065.1  4105.1  4145.1
  4175.1  4205.1  4265.1  4325.1  4375.1  4413.1  4513.1  4553.1  4593.1  4613.1
  4613.3  4761.9  4801.1 4805.29  4805.4  5140.6 5154.39  5159.1  5162.1 5162.21
  5210.4  5260.6  5267.1    5373    5422  5444.1    5482    5522  5553.4  5573.4
  5693.4  5763.4  5797.7  5857.7  5897.7  5997.7  6087.7  6117.7  6207.7  6267.7
   28.85   29.54   29.04   27.14   27.07   27.85   26.33   26.83   26.49   25.44
   26.53   26.51   24.67   25.04   28.15   27.56    22.9   20.26   17.71   17.45
   15.79   13.73   13.07   12.17   13.17   12.77   15.21   16.19   17.16   17.65
   18.55    22.4   23.75   23.86   26.46   26.38   26.37   26.37   26.37   23.77
   22.64   20.93   20.71   17.29   15.71      15   15.55   15.19   15.97      18
    25.7   26.94    28.8   28.64    26.4   26.43   27.42   26.41   28.16   28.18
   28.76   29.45   28.95   27.05   26.98   27.76   26.24   26.74    26.4   25.35
   26.44   26.42   24.58   24.95   28.06   27.47    22.8   20.16   17.61   17.35
   15.69   12.63   12.97   12.07   13.07   12.62   14.08   12.38   13.14   14.25
   18.45   21.94   21.93   20.06   20.01   19.69      21   22.35   22.07   22.06
   17.64   17.52   19.15   16.22    12.9    13.9   15.45   14.91   15.87    17.9
    25.6   26.84   28.71   28.55   26.31   26.34   27.33   26.32   28.07   28.09
Pier Skew, UpSta & Num, DnSta & Num=  ,4874.3, 2 ,4874.3, 2 , 0 , 0 , 0 ,,
     1.6     1.6
     4.2   20.84
     1.6     1.6
    4.11   20.75
Pier Skew, UpSta & Num, DnSta & Num=  ,4944.7, 2 ,4944.7, 2 , 0 , 0 , 0 ,,
     1.6     1.6
   -1.74   20.82
     1.6     1.6
   -1.83   20.73
Pier Skew, UpSta & Num, DnSta & Num=  ,5014.3, 2 ,5014.3, 2 , 0 , 0 , 0 ,,
     1.6     1.6
  -21.57   20.81
     1.6     1.6
  -21.66   20.72
Pier Skew, UpSta & Num, DnSta & Num=  ,5084.2, 2 ,5084.2, 2 , 0 , 0 , 0 ,,
     1.6     1.6
     -.2   20.79
     1.6     1.6
    -.29    20.7
Abutment Skew #Up #Dn= , 2 , 2
  4804.7  4814.9
   20.32   15.85
  4804.7  4814.9
   20.23   15.76
Abutment Skew #Up #Dn= , 2 , 2
  5140.6 5154.59
   17.13   21.09
  5140.6 5154.59
   17.04      21
BR Coef= 1 , 1 , 0 ,1.25, 0 ,,,0.8,0,2,0,
WSPro=,,,, 1 ,,,, 0 ,,,, 0 ,,,,-1 ,-1 ,-1 , 0 , 0 , 0 , 0 , 0
BR U #Sta/Elev= 147
  2624.5   28.85  2661.2   29.08  2664.5    29.1  2684.5   28.75  2774.5   29.54
  2834.5   29.04  2854.5   28.22  2864.5   27.35  2874.5   27.14  2884.5   27.53
  2894.5   27.51  2914.5   27.07  2924.5    27.6  2934.5   27.85  3104.5   26.33
  3124.5   26.83  3194.5   26.49  3204.5   25.54  3214.5   25.44  3224.5   26.53
  3234.5   26.19  3454.5   26.51  3474.5   25.91  3494.5   24.67  3524.5   24.71
  3534.5   25.04  3554.5   26.28  3564.5   27.21  3574.5   27.83  3584.5   28.15
  3604.5   27.86  3754.5   27.56  3826.3   26.05  3845.1   25.66  3885.1   24.78
  3905.1   24.82  3915.1   24.52  3935.1   24.28  3945.1   23.71  3976.3    23.2
  3995.1   22.89  4005.1   22.22  4065.1   20.25    4091   18.42  4095.1   18.13
  4105.1    17.7  4125.1   17.26  4145.1   17.44  4175.1   15.78  4205.1   12.72
  4215.1   12.47  4265.1   13.06    4301   12.52  4325.1   12.16  4335.1   12.58
  4344.4   12.71  4375.1   13.16  4413.1   12.71  4513.1   14.17  4533.1   13.54
  4543.1   12.69  4553.1   12.47  4593.1   13.23  4603.1   14.07  4613.1   14.34
  4613.3   18.54    4648   19.22  4655.3   19.36  4708.1    20.8  4761.9   22.03
  4801.1   22.02  4804.7   20.41 4804.81   20.36  4804.9   20.32 4805.29   20.15
  4805.4    20.1 4805.51   20.05  4814.8   15.89  4814.9   15.85  4848.6    5.36
  4874.3    5.19    4895    5.68  4909.5    3.74  4912.6     .44  4912.9     .43
  4934.3    -.59  4944.7    -.33    4988  -22.79  5014.3   -20.5  5048.7   -4.25
  5084.2     .96  5087.1     .39  5109.6    8.23  5140.6   17.13 5154.39   21.09
  5154.5   21.12  5159.1   22.44 5161.99   22.17  5162.1   22.16 5162.21   22.15
  5199.1   18.77  5210.4   17.73  5260.6   17.61    5264   18.46  5267.1   19.24
    5363   16.21    5373   16.31    5383   15.89    5393    15.2    5402   14.35
    5422   12.99    5432   13.25  5444.1   13.99    5452   14.47    5462    14.8
    5472   14.88    5482   15.54    5522      15  5533.4   15.15  5553.4   15.96
  5573.4   17.99  5644.1   22.25  5663.4   23.41  5673.4   24.48  5693.4   25.69
  5763.4   26.93  5777.7   27.98  5796.7   28.76  5797.7    28.8  5807.7   28.89
  5837.7   28.42  5857.7   28.64  5867.7   28.14  5877.7    27.3  5897.7    26.4
  5967.7   26.38  5977.7   26.74  5987.7   26.84  5997.7   26.43  6017.7   26.59
  6027.7   26.96  6087.7   27.42  6117.7   26.41  6147.7   27.02  6167.7   26.92
  6207.7   28.16  6267.7   28.18
BR U #Mann= 4
  2624.5      .2  2661.2      .1  4912.6    .035  5087.1      .1
BR U Banks=4912.6,5087.1
BR D #Sta/Elev= 147
  2624.5   28.76  2661.2   28.99  2664.5   29.01  2684.5   28.66  2774.5   29.45
  2834.5   28.95  2854.5   28.13  2864.5   27.26  2874.5   27.05  2884.5   27.44
  2894.5   27.42  2914.5   26.98  2924.5   27.51  2934.5   27.76  3104.5   26.24
  3124.5   26.74  3194.5    26.4  3204.5   25.45  3214.5   25.35  3224.5   26.44
  3234.5    26.1  3454.5   26.42  3474.5   25.82  3494.5   24.58  3524.5   24.62
  3534.5   24.95  3554.5   26.19  3564.5   27.12  3574.5   27.74  3584.5   28.06
  3604.5   27.77  3754.5   27.47  3826.3   25.96  3845.1   25.57  3885.1   24.69
  3905.1   24.73  3915.1   24.43  3935.1   24.19  3945.1   23.62  3976.3   23.11
  3995.1    22.8  4005.1   22.13  4065.1   20.16    4091   18.33  4095.1   18.04
  4105.1   17.61  4125.1   17.17  4145.1   17.35  4175.1   15.69  4205.1   12.63
  4215.1   12.38  4265.1   12.97    4301   12.43  4325.1   12.07  4335.1   12.49
  4344.4   12.62  4375.1   13.07  4413.1   12.62  4513.1   14.08  4533.1   13.45
  4543.1    12.6  4553.1   12.38  4593.1   13.14  4603.1   13.98  4613.1   14.25
  4613.3   18.45    4648   19.13  4655.3   19.27  4708.1   20.71  4761.9   21.94
  4801.1   21.93  4804.7   20.32 4804.81   20.27  4804.9   20.23 4805.29   20.06
  4805.4   20.01 4805.51   19.96  4814.8    15.8  4814.9   15.76  4848.6    5.27
  4874.3     5.1    4895    5.59  4909.5    3.65  4912.6     .35  4912.9     .34
  4934.3    -.68  4944.7    -.42    4988  -22.88  5014.3  -20.59  5048.7   -4.34
  5084.2     .87  5087.1      .3  5109.6    8.14  5140.6   17.04 5154.39      21
  5154.5   21.03  5159.1   22.35 5161.99   22.08  5162.1   22.07 5162.21   22.06
  5199.1   18.68  5210.4   17.64  5260.6   17.52    5264   18.37  5267.1   19.15
    5363   16.12    5373   16.22    5383    15.8    5393   15.11    5402   14.26
    5422    12.9    5432   13.16  5444.1    13.9    5452   14.38    5462   14.71
    5472   14.79    5482   15.45    5522   14.91  5533.4   15.06  5553.4   15.87
  5573.4    17.9  5644.1   22.16  5663.4   23.32  5673.4   24.39  5693.4    25.6
  5763.4   26.84  5777.7   27.89  5796.7   28.67  5797.7   28.71  5807.7    28.8
  5837.7   28.33  5857.7   28.55  5867.7   28.05  5877.7   27.21  5897.7   26.31
  5967.7   26.29  5977.7   26.65  5987.7   26.75  5997.7   26.34  6017.7    26.5
  6027.7   26.87  6087.7   27.33  6117.7   26.32  6147.7   26.93  6167.7   26.83
  6207.7   28.07  6267.7   28.09
BR D #Mann= 4
  2624.5      .2  2661.2      .1  4912.6    .035  5087.1      .1
BR D Banks=4912.6,5087.1
BC Design=,, 0 ,, 0 ,,,,,,
BC HTab HWMax=29.53
BC Use User HTab Curves=0
BC User HTab FreeFlow(D)= 0

Type RM Length L Ch R = 1 ,25305.2 ,566.8,566.8,566.8
BEGIN DESCRIPTION:
Downstream Section of Bridge/Culvert/Weir
END DESCRIPTION:
XS GIS Cut Line= 6
      3172059.01     13851384.04      3171855.07     13850651.57
      3171765.62     13850219.23      3171733.72     13849956.44
      3171733.93     13849703.08      3171849.53     13847783.35
#Sta/Elev= 30
  2624.5   28.76  2661.2   28.99  3494.5   24.58  3584.5   28.06  3754.5   27.47
  3995.1    22.8  4215.1   12.38  4513.1   14.08  4553.1   12.38  4613.1   14.25
  4613.3   18.45  4801.1   21.93  4848.6    5.27    4895    5.59  4909.5    3.65
  4912.6     .35  4944.7    -.42    4988  -22.88  5014.3  -20.59  5048.7   -4.34
  5087.1      .3  5159.1   22.35  5210.4   17.64  5267.1   19.15    5422    12.9
  5553.4   15.87  5693.4    25.6  5797.7   28.71  5897.7   26.31  6267.7   28.09
#Mann= 4 , 1 , 0
  2624.5      .2       0  2661.2      .1       0  4912.6    .035       0
  5087.1      .1       0
#XS Ineff= 2 , 0
       0    4826    12.4    5129       0    13.8
Permanent Ineff=
       F       F
Bank Sta=4912.6,5087.1
XS Rating Curve= 0 ,0
Exp/Cntr=0.5,0.3

Type RM Length L Ch R = 1 ,24738.4 ,564,594.4,499.6
BEGIN DESCRIPTION:
Cross Section 24738.4-Interpolated
END DESCRIPTION:
XS GIS Cut Line= 6
      3173232.74     13850772.53      3172735.56     13850063.59
      3172422.53     13849805.79      3172348.87     13848765.41
      3172183.79     13848475.49      3172145.84     13847773.41
#Sta/Elev= 30
  2889.7    26.8  3459.2    22.8  3755.7   24.47  3882.2   22.55  4078.8   17.73
  4148.8   13.77  4240.3   14.81  4361.1    9.16  4547.9   11.65  4697.9     2.9
  4757.9    3.02  4887.9    7.89  4907.9    7.04  4916.6     4.7  4924.5    -.56
  4955.2      -2  5002.1     -23  5024.7     -17  5048.1      -5  5117.9     5.9
  5157.9       6  5187.9    9.23  5226.7    9.17  5236.7   10.93  5279.1   10.67
  5496.7   11.24  5526.7   11.76  5556.7      15  5700.4   18.19  6263.5   26.65
#Mann= 7 , 1 , 0
  2889.7      .2       0  2889.7      .1       0  3882.2     .14       0
  4916.6    .035       0  5117.9     .14       0  5279.1      .1       0
  6263.5      .2       0
Bank Sta=4916.6,5117.9
XS Rating Curve= 0 ,0
Exp/Cntr=0.3,0.1

Type RM Length L Ch R = 1 ,24144.0 ,647.4,809.9,1006.4
BEGIN DESCRIPTION:
Cross Section 24144.0
END DESCRIPTION:
XS GIS Cut Line= 6
      3172823.66     13849700.57      3172837.37     13849553.01
       3172955.6     13849006.22      3172950.67     13848740.21
      3172398.95      13848360.9      3172246.24     13847779.63
#Sta/Elev= 30
  4218.2    33.8  4272.3    32.9  4297.3    30.7  4307.3      28  4366.4    33.1
  4401.4    28.8  4431.4    33.7  4450.6      31  4510.6    16.2  4555.6    11.7
  4740.6       5  4901.1    5.35  4916.6    4.03  4924.5   -1.23  4955.2   -2.67
  5002.1  -23.67  5024.7  -17.67  5048.1   -5.67  5079.3     .42  5095.5    6.81
  5114.1    9.83    5223    12.4    5323    10.8    5568    11.6    5638    16.9
  5705.9   17.75  5822.1    22.1  6247.6    23.3  6257.6    24.8  6463.6    26.9
#Mann= 5 , 1 , 0
  4218.2      .1       0  4916.6    .035       0  5095.5     .14       0
  5705.9      .1       0  6463.6      .2       0
Bank Sta=4916.6,5095.5
XS Rating Curve= 0 ,0
Exp/Cntr=0.3,0.1

Type RM Length L Ch R = 1 ,23334.1 ,682.6,750.2,465.4
BEGIN DESCRIPTION:
Cross Section 23334.1-Interpolated
END DESCRIPTION:
XS GIS Cut Line= 6
      3173076.22     13849953.11       3173306.4     13849704.52
      3173858.81     13848912.72      3173831.19     13848691.75
      3173442.46     13848214.92      3172565.14      13847938.2
#Sta/Elev= 30
  3945.9    27.5  4125.9    25.4  4235.9    21.4  4304.7    15.4  4384.7    16.5
  4574.7    11.9  4624.7     5.8  4664.7     4.8  4704.7       8  4774.7     8.9
  4854.7     3.8  4917.2    4.33  4924.3   -1.18  4954.9   -2.66  5001.9   -23.5
  5024.4  -18.18  5047.9   -6.04  5079.5     .47    5096    6.84  5144.7     6.7
  5250.1    19.7  5378.6   18.49  5572.8      15  5702.8    19.5  6090.7    19.1
  6240.7      17  6260.7    14.8  6320.7    19.3  6960.7    20.7  7010.7    27.9
#Mann= 5 , 1 , 0
  3945.9      .2       0  3945.9      .1       0  4917.2    .035       0
    5096     .14       0  5378.6      .1       0
#XS Ineff= 2 , 0
       0                  5250.1       0    19.7
Permanent Ineff=
       F       F
Bank Sta=4917.2,5096
XS Rating Curve= 0 ,0
Exp/Cntr=0.3,0.1

Type RM Length L Ch R = 1 ,22583.9 ,1008.4,606.6,117.1
BEGIN DESCRIPTION:
Cross Section 22583.9
END DESCRIPTION:
XS GIS Cut Line= 6
      3173704.12     13850950.57      3174335.69     13849437.51
      3174256.71     13848870.24      3173904.86     13848310.16
       3173164.6      13847921.6      3172582.75     13847826.56
#Sta/Elev= 30
  3505.7   27.91  3755.7   23.35  3835.7   17.07  4055.7    9.81  4175.7    9.13
  4195.7    6.41  4245.7      11  4305.7   11.49  4495.7    9.76  4595.7    4.53
  4917.2    4.35  4924.3   -1.16  4954.9   -2.64  5001.9  -23.48  5024.4  -18.16
  5047.9   -6.02  5079.5     .49    5096    6.86  5127.9   12.08  5436.9   16.07
  5833.6   17.54  6153.6   11.67    6425   19.33    6625   17.66    6905   20.61
    7045    13.7    7085   19.89    7215   21.68    7761   21.64  7810.6   28.11
#Mann= 6 , 1 , 0
  3505.7      .2       0  3505.7      .1       0  4917.2    .035       0
    5096     .14       0  5436.9      .1       0  7810.6      .2       0
#XS Ineff= 2 , 0
       0                  5723.5       0    17.9
Permanent Ineff=
       F       F
Bank Sta=4917.2,5096
XS Rating Curve= 0 ,0
Exp/Cntr=0.3,0.1

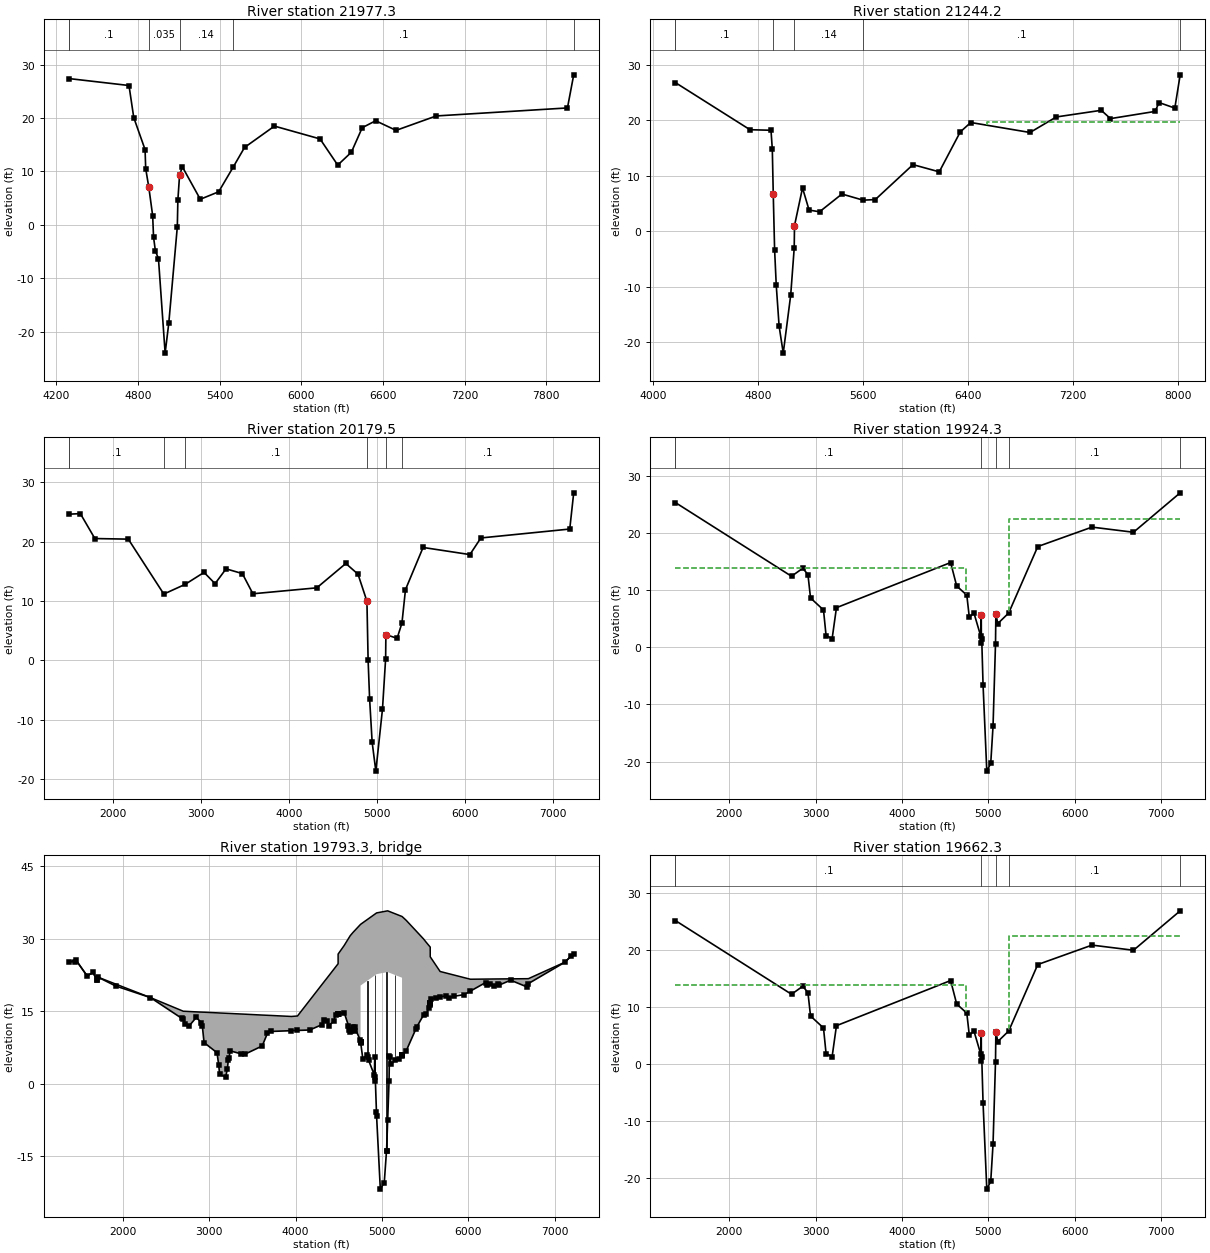
Type RM Length L Ch R = 1 ,21977.3 ,883.4,733.1,364.5
BEGIN DESCRIPTION:
Cross Section 21977.3
END DESCRIPTION:
XS GIS Cut Line= 6
      3175261.99     13850083.76      3174780.89     13849372.88
      3174400.32     13848949.23      3173947.94     13848267.07
      3173174.29     13847906.08      3172580.81     13847811.05
#Sta/Elev= 30
  4292.8    27.4  4734.1    26.1  4769.1    20.1  4852.2    14.1  4856.8   10.54
  4879.8    7.03    4908    1.73  4914.5   -2.29  4927.9   -4.84  4950.6   -6.33
  4999.6  -24.01  5026.5  -18.37  5089.1    -.35  5093.1    4.65  5105.6    9.29
  5125.9   10.88  5257.8     4.8  5392.8     6.2  5499.2   10.81  5582.8    14.5
  5802.3    18.5  6137.3    16.1  6267.3    11.2  6367.3    13.6  6447.3    18.2
  6545.8    19.5  6695.8    17.7  6990.8    20.4  7954.6    21.9  8000.6    28.1
#Mann= 6 , 1 , 0
  4292.8      .2       0  4292.8      .1       0  4879.8    .035       0
  5105.6     .14       0  5499.2      .1       0  8000.6      .2       0
#XS Ineff= 2 , 0
       0                  5802.3       0    18.5
Permanent Ineff=
       F       F
Bank Sta=4879.8,5105.6
XS Rating Curve= 0 ,0
Exp/Cntr=0.3,0.1

Type RM Length L Ch R = 1 ,21244.2 ,1075.7,1064.7,980.1
BEGIN DESCRIPTION:
Cross Section 21244.2-Interpolated
END DESCRIPTION:
XS GIS Cut Line= 6
      3175777.32     13849499.66      3175547.14     13848981.77
      3174718.52     13848774.61       3173774.8     13848049.56
      3173357.91     13847901.14      3172584.45     13847794.24
#Sta/Elev= 30
    4171    26.8    4739    18.3    4899    18.2    4909    14.8  4916.3    6.62
  4926.5   -3.35  4939.1   -9.79 4960.85  -17.14 4992.28     -22  5048.9  -11.56
 5075.75   -3.06 5077.93     .99    5139     7.8    5189     3.8    5269     3.5
    5439     6.7  5600.6    5.59  5693.1     5.7    5980      12    6180    10.7
    6340    17.9    6420    19.6    6871    17.8    7071    20.6  7413.5    21.8
  7483.5    20.3  7823.5    21.6  7853.5    23.2  7973.5    22.2  8014.3    28.2
#Mann= 6 , 1 , 0
    4171      .2       0    4171      .1       0  4916.3    .035       0
 5077.93     .14       0  5600.6      .1       0  8014.3      .2       0
#XS Ineff= 2 , 0
       0                  6544.5       0    19.7
Permanent Ineff=
       F       F
Bank Sta=4916.3,5077.93
XS Rating Curve= 0 ,0
Exp/Cntr=0.3,0.1

Type RM Length L Ch R = 1 ,20179.5 ,301.9,255.2,176.8
BEGIN DESCRIPTION:
Cross Section 20179.5
END DESCRIPTION:
XS GIS Cut Line= 6
      3178277.84     13848245.53      3176978.15     13848295.79
      3175721.55     13848030.11       3175040.1     13847969.84
      3174632.15     13848064.55      3172604.52     13847785.74
#Sta/Elev= 30
  1501.3    24.6  1631.3    24.7  1796.3    20.5  2176.3    20.4  2579.9   11.15
  2821.6   12.78  3037.4    14.8  3162.4    12.9  3287.4    15.4  3472.5    14.6
  3592.5    11.2  4318.7    12.2  4648.7    16.3  4786.9    14.5  4888.4    9.95
    4902    -.02  4918.8   -6.46  4947.8  -13.81  4989.7  -18.67  5065.2   -8.23
    5101     .27  5103.9    4.32  5231.6     3.7  5286.4    6.27  5326.6    11.9
  5526.6      19  6058.6    17.8  6183.6    20.6  7193.6    22.1  7238.6    28.2
#Mann= 7 , 1 , 0
  1501.3      .2       0  1501.3      .1       0  2579.9     .14       0
  2821.6      .1       0  4888.4    .035       0  5103.9     .14       0
  5286.4      .1       0
#XS Ineff= 2 , 0
       0                  5526.6       0      19
Permanent Ineff=
       F       F
Bank Sta=4888.4,5103.9
XS Rating Curve= 0 ,0
Exp/Cntr=0.5,0.3

Type RM Length L Ch R = 1 ,19924.3 ,262,262,262
BEGIN DESCRIPTION:
Upstream Section of Bridge/Culvert/Weir
END DESCRIPTION:
XS GIS Cut Line= 6
      3178358.74     13847778.22      3177986.23     13847668.66
      3177460.66     13847645.94      3174299.79     13847809.26
      3174084.37     13847809.26      3172542.53     13847699.57
#Sta/Elev= 30
  1377.8   25.32  2721.6   12.42  2851.6   13.82  2911.6   12.72  2941.6    8.62
  3091.6    6.52  3121.6    2.02  3191.6    1.52  3241.6    6.92  4562.6   14.82
  4632.6   10.72  4749.8    9.11  4778.7    5.25  4832.1       6  4911.6    1.91
  4917.1    5.71  4918.2     .71  4922.5     1.4  4937.8   -6.59    4981  -21.68
  5026.6  -20.32  5053.2  -13.83  5081.9     .63  5086.1    5.89  5107.7    4.13
  5234.4    5.99  5570.8   17.62  6198.3   21.02  6678.3   20.12  7218.5   27.02
#Mann= 6 , 1 , 0
  1377.8      .2       0  1377.8      .1       0  4917.1    .035       0
  5086.1     .14       0  5234.4      .1       0  7218.5      .2       0
#XS Ineff= 2 , 0
       0    4741    13.8    5242       0    22.5
Permanent Ineff=
       F       F
Bank Sta=4917.1,5086.1
XS Rating Curve= 0 ,0
Exp/Cntr=0.5,0.3

Type RM Length L Ch R = 3 ,19793.3 ,,,
BEGIN DESCRIPTION:
INTERSTATE ROUTE 10
Structure ID: P00-6
END DESCRIPTION:
Bridge Culvert--1,0,-1,-1, 0
Deck Dist Width WeirC Skew NumUp NumDn MinLoCord MaxHiCord MaxSubmerge Is_Ogee
10,242,2.6,0, 60, 60, , , 0.95, 0, 1,1,,
  1377.8  1457.8  1587.8  1657.8  1697.8  1717.8  2321.6  2701.6  2721.6  2771.6
  2851.6  2911.6  2921.6  2941.6  3091.6  3121.6  3191.6  3241.6  3414.4  3614.4
  3674.4  3714.4  3952.7  4022.6  4164.4  4304.4  4334.4  4362.6  4382.6  4442.6
  4462.6 4492.49  4492.6  4562.6  4632.6  4662.6  4682.6  4682.9 4752.51  4752.6
  4937.8    5066 5232.09  5232.2  5232.4  5280.8    5481  5510.3  5558.4 5558.51
  5570.8  5672.7  6022.7  6198.3  6298.3  6488.3  6678.3  6694.7  7114.7  7218.5
    25.2    25.6    22.3      23    21.5      22    17.8   14.98   14.97   14.92
   14.85    14.8   14.79   14.78   14.65   14.62   14.56   14.52   14.37   14.19
   14.14   14.11    13.9      14   17.26   20.48   21.17   21.81   22.27   23.65
   24.11    24.8    26.8   28.57    30.6   31.23   31.62   31.62   32.95   32.95
   35.31   35.74   34.57   34.57   34.57   33.77   29.93   29.27   28.24   26.24
   25.91    23.2    21.6   21.63   21.65   21.68   21.71   21.72   25.11    26.9
    25.2    25.6    22.3      23    21.5      22    17.8    13.3    12.3      12
    13.7    12.6    11.9     8.5     6.4     1.9     1.4     6.8     6.1     7.8
    10.4    10.8   10.96   11.01    11.1    12.2    13.2      13      12    12.9
    14.2   14.35   14.35    14.7    10.6    11.7    10.9   11.64    8.63   20.29
   22.65   23.08   21.91    5.83    5.83     6.8   14.19   14.38   16.69    16.7
    17.5   17.89   19.14    20.9    20.2    21.4      20    20.7    25.1    26.9
  1377.8  1457.8  1587.8  1657.8  1697.8  1717.8  2321.6  2701.6  2721.6  2771.6
  2851.6  2911.6  2921.6  2941.6  3091.6  3121.6  3191.6  3241.6  3414.4  3614.4
  3674.4  3714.4  3952.7  4022.6  4164.4  4304.4  4334.4  4362.6  4382.6  4442.6
  4462.6 4492.49  4492.6  4562.6  4632.6  4662.6  4682.6  4682.9 4752.51  4752.6
  4937.8    5066 5232.09  5232.2  5232.4  5280.8    5481  5510.3  5558.4 5558.51
  5570.8  5672.7  6022.7  6198.3  6298.3  6488.3  6678.3  6694.7  7114.7  7218.5
    25.2    25.6    22.3      23    21.5      22    17.8   14.98   14.97   14.92
   14.85    14.8   14.79   14.78   14.65   14.62   14.56   14.52   14.37   14.19
   14.14   14.11    13.9      14   17.26   20.48   21.17   21.81   22.27   23.65
   24.11    24.8    26.8   28.57    30.6   31.23   31.62   31.62   32.95   32.95
   35.31   35.74   34.57   34.57   34.57   33.77   29.93   29.27   28.24   26.24
   25.91    23.2    21.6   21.63   21.65   21.68   21.71   21.72   25.11    26.9
   25.08   25.48   22.18   22.88   21.38   21.88   17.68   13.18   12.18   11.88
   13.58   12.48   11.78    8.38    6.28    1.78    1.28    6.68    5.98    7.68
   10.28   10.68   10.84   10.89   10.98   12.08   13.08   12.88   11.88   12.78
   14.08   14.23   14.23   14.58   10.48   11.58   10.78   11.52    8.51   20.17
   22.53   22.96   21.79    5.71    5.71    6.68   14.07   14.26   16.57   16.58
   17.38   17.77   19.02   20.78   20.08   21.28   19.88   20.58   24.98   26.78
Pier Skew, UpSta & Num, DnSta & Num=  ,4832.1, 2 ,4832.1, 2 , 0 , 0 , 0 ,,
     1.5     1.5
    4.82   22.61
     1.5     1.5
     4.7   22.49
Pier Skew, UpSta & Num, DnSta & Num=  ,4922.4, 2 ,4922.4, 2 , 0 , 0 , 0 ,,
       3       3
    -.45   23.52
       3       3
    -.57    23.4
Pier Skew, UpSta & Num, DnSta & Num=  ,5052.6, 2 ,5052.6, 2 , 0 , 0 , 0 ,,
       3       3
  -15.27   24.04
       3       3
  -15.39   23.92
Pier Skew, UpSta & Num, DnSta & Num=  ,5147.9, 2 ,5147.9, 2 , 0 , 0 , 0 ,,
     1.5     1.5
    3.79   23.51
     1.5     1.5
    3.67   23.39
Abutment Skew #Up #Dn= , 2 , 2
  4752.4  4754.2
   20.29     8.4
  4752.4  4754.2
   20.17    8.28
Abutment Skew #Up #Dn= , 2 , 2
  5230.7 5232.29
     5.8   21.91
  5230.7 5232.29
    5.68   21.79
BR Coef= 1 , 1 , 0 ,1.25, 0 ,,,0.8,0,2,0,
WSPro=,,,, 1 ,,,, 0 ,,,, 0 ,,,,-1 ,-1 ,-1 , 0 , 0 , 0 , 0 , 0
BR U #Sta/Elev= 116
  1377.8    25.2  1447.8    25.2  1457.8    25.6  1587.8    22.3  1657.8      23
  1697.8    21.5  1707.8    21.5  1717.8      22  1919.5    20.2  2321.6    17.8
    2683   13.52  2701.6    13.3  2721.6    12.3  2771.6      12  2851.6    13.7
  2911.6    12.6  2921.6    11.9  2941.6     8.5  3091.6     6.4  3111.6     3.8
  3121.6     1.9  3191.6     1.4  3211.6     3.1  3221.6     4.8  3231.6     5.3
  3241.6     6.8  3364.4     6.2  3414.4     6.1  3614.4     7.8  3674.4    10.4
  3714.4    10.8  3952.7   10.96  4022.6   11.01  4164.4    11.1  4304.4    12.2
  4334.4    13.2  4362.6      13  4382.6      12  4442.6    12.9  4462.6    14.2
 4492.49   14.35  4492.6   14.35 4492.71   14.35  4501.8    14.4  4562.6    14.7
  4612.6      12  4622.6      11  4632.6    10.6  4638.1    10.8  4662.6    11.7
  4682.6    10.9  4682.9   11.64  4749.8    8.99  4752.4    8.64 4752.51    8.63
  4752.6    8.62  4752.7     8.6  4754.2     8.4  4778.7    5.13  4832.1    5.88
  4837.9    5.42  4845.1    4.85  4911.6    1.79  4917.1    5.59  4918.2     .59
  4922.5    1.28    4936   -5.77  4937.8   -6.71    4981   -21.8  5026.6  -20.44
  5052.6  -13.89  5053.2  -13.95    5066    -7.5  5081.9     .51  5086.1    5.77
  5092.1    5.56  5107.7    4.01  5147.9     4.8  5193.8    5.06  5230.7     5.8
 5232.09    5.83  5232.2    5.83  5232.3    5.83  5232.4    5.83  5234.4    5.87
  5280.8     6.8  5392.7   11.32  5404.1   11.78    5481   14.19  5510.3   14.38
    5545   15.65  5550.8    16.2  5555.9   16.53 5558.29   16.69  5558.4   16.69
 5558.51    16.7  5570.8    17.5  5630.8    17.7  5672.7   17.89  5740.8    18.2
  5770.8    17.8  5838.3    18.1  5948.3    18.4  6022.7   19.14  6198.3    20.9
  6218.3    20.4  6248.3    20.7  6298.3    20.2  6338.3    20.7  6358.3    20.4
  6488.3    21.4  6678.3      20  6694.7    20.7  7114.7    25.1  7190.3   26.41
  7218.5    26.9
BR U #Mann= 6
  1377.8      .2  1377.8      .1  4917.1    .035  5086.1     .14  5234.4      .1
  7218.5      .2
BR U Banks=4917.1,5086.1
BR D #Sta/Elev= 116
  1377.8   25.08  1447.8   25.08  1457.8   25.48  1587.8   22.18  1657.8   22.88
  1697.8   21.38  1707.8   21.38  1717.8   21.88  1919.5   20.08  2321.6   17.68
    2683    13.4  2701.6   13.18  2721.6   12.18  2771.6   11.88  2851.6   13.58
  2911.6   12.48  2921.6   11.78  2941.6    8.38  3091.6    6.28  3111.6    3.68
  3121.6    1.78  3191.6    1.28  3211.6    2.98  3221.6    4.68  3231.6    5.18
  3241.6    6.68  3364.4    6.08  3414.4    5.98  3614.4    7.68  3674.4   10.28
  3714.4   10.68  3952.7   10.84  4022.6   10.89  4164.4   10.98  4304.4   12.08
  4334.4   13.08  4362.6   12.88  4382.6   11.88  4442.6   12.78  4462.6   14.08
 4492.49   14.23  4492.6   14.23 4492.71   14.23  4501.8   14.28  4562.6   14.58
  4612.6   11.88  4622.6   10.88  4632.6   10.48  4638.1   10.68  4662.6   11.58
  4682.6   10.78  4682.9   11.52  4749.8    8.87  4752.4    8.52 4752.51    8.51
  4752.6     8.5  4752.7    8.48  4754.2    8.28  4778.7    5.01  4832.1    5.76
  4837.9     5.3  4845.1    4.73  4911.6    1.67  4917.1    5.47  4918.2     .47
  4922.5    1.16    4936   -5.89  4937.8   -6.83    4981  -21.92  5026.6  -20.56
  5052.6  -14.01  5053.2  -14.07    5066   -7.62  5081.9     .39  5086.1    5.65
  5092.1    5.44  5107.7    3.89  5147.9    4.68  5193.8    4.94  5230.7    5.68
 5232.09    5.71  5232.2    5.71  5232.3    5.71  5232.4    5.71  5234.4    5.75
  5280.8    6.68  5392.7    11.2  5404.1   11.66    5481   14.07  5510.3   14.26
    5545   15.53  5550.8   16.08  5555.9   16.41 5558.29   16.57  5558.4   16.57
 5558.51   16.58  5570.8   17.38  5630.8   17.58  5672.7   17.77  5740.8   18.08
  5770.8   17.68  5838.3   17.98  5948.3   18.28  6022.7   19.02  6198.3   20.78
  6218.3   20.28  6248.3   20.58  6298.3   20.08  6338.3   20.58  6358.3   20.28
  6488.3   21.28  6678.3   19.88  6694.7   20.58  7114.7   24.98  7190.3   26.29
  7218.5   26.78
BR D #Mann= 6
  1377.8      .2  1377.8      .1  4917.1    .035  5086.1     .14  5234.4      .1
  7218.5      .2
BR D Banks=4917.1,5086.1
BC Design=,, 0 ,, 0 ,,,,,,
BC HTab HWMax=27.02
BC Use User HTab Curves=0
BC User HTab FreeFlow(D)= 0

Type RM Length L Ch R = 1 ,19662.3 ,1574.2,1574.2,1574.2
BEGIN DESCRIPTION:
Downstream Section of Bridge/Culvert/Weir
END DESCRIPTION:
XS GIS Cut Line= 6
      3178358.74     13847516.22      3177986.23     13847406.66
      3177460.66     13847383.94      3174299.79     13847547.26
      3174084.37     13847547.26      3172542.53     13847437.57
#Sta/Elev= 30
  1377.8   25.12  2721.6   12.22  2851.6   13.62  2911.6   12.52  2941.6    8.42
  3091.6    6.32  3121.6    1.82  3191.6    1.32  3241.6    6.72  4562.6   14.62
  4632.6   10.52  4749.8    8.91  4778.7    5.05  4832.1     5.8  4911.6    1.71
  4917.1    5.51  4918.2     .51  4922.5     1.2  4937.8   -6.79    4981  -21.88
  5026.6  -20.52  5053.2  -14.03  5081.9     .43  5086.1    5.69  5107.7    3.93
  5234.4    5.79  5570.8   17.42  6198.3   20.82  6678.3   19.92  7218.5   26.82
#Mann= 6 , 1 , 0
  1377.8      .2       0  1377.8      .1       0  4917.1    .035       0
  5086.1     .14       0  5234.4      .1       0  7218.5      .2       0
#XS Ineff= 2 , 0
       0    4741    13.8    5242       0    22.5
Permanent Ineff=
       F       F
Bank Sta=4917.1,5086.1
XS Rating Curve= 0 ,0
Exp/Cntr=0.5,0.3