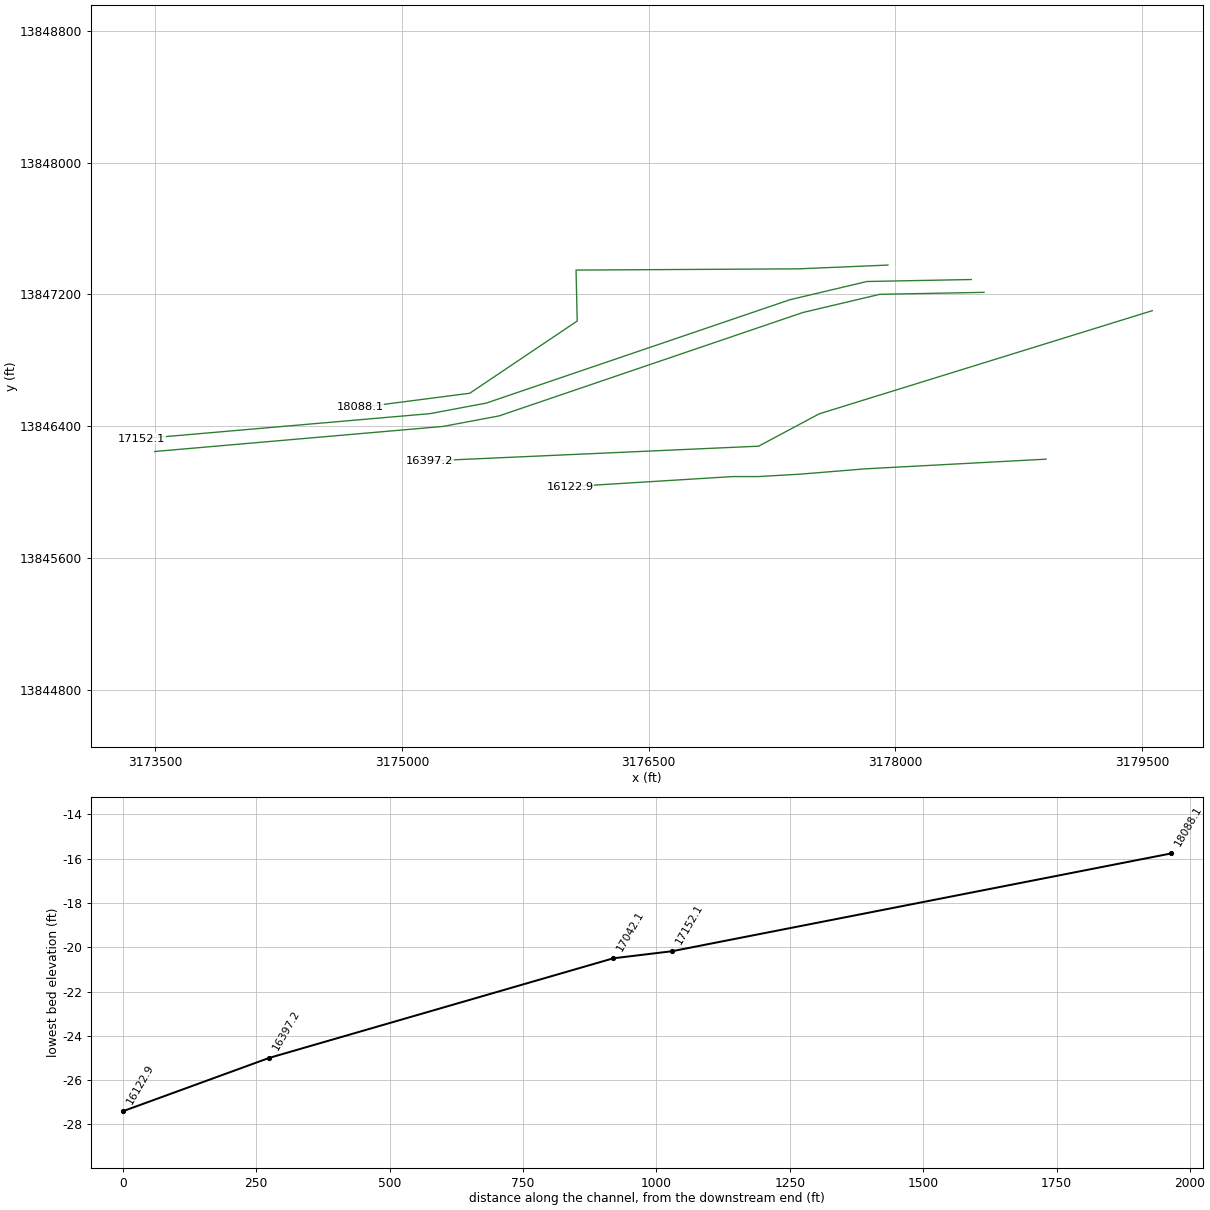
HEC-RAS study P100-00-00.prj: P100-00-00

--- P100-00-00.g01 (geometry) --- (continued)

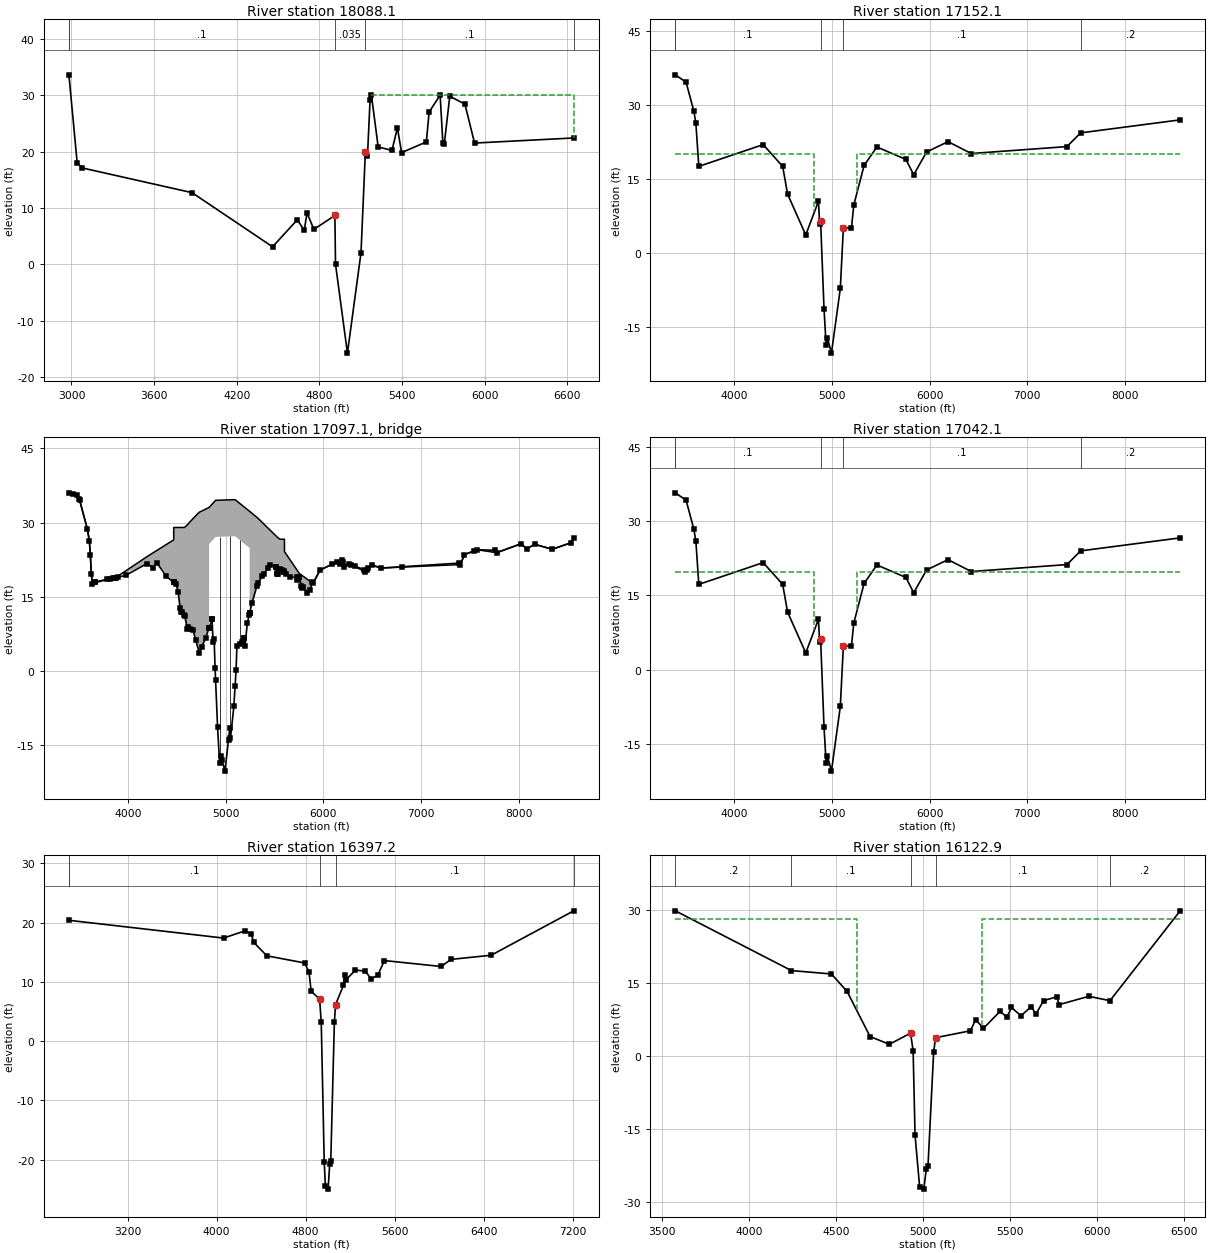
Type RM Length L Ch R = 1 ,18088.1 ,947.8,936,906.9
BEGIN DESCRIPTION:
Cross Section 18088.1
END DESCRIPTION:
XS GIS Cut Line= 6
      3177955.22     13847378.38      3177412.79     13847355.49
      3176059.04     13847347.96      3176066.22     13847039.19
      3175412.78     13846601.17      3174744.99     13846515.01
#Sta/Elev= 30
  2981.5    33.6  3041.5      18  3075.8    17.1  3875.8    12.7  4460.4     3.1
  4640.4     7.9  4690.4       6  4710.4     9.1  4760.4     6.2  4912.9    8.65
  4917.5     .02  5004.1  -15.76  5102.7    2.07  5134.4   19.95  5149.6   19.19
  5168.4    29.1  5178.4      30  5227.2    20.8  5327.2    20.2  5367.2    24.2
  5397.2    19.8  5577.2    21.7  5597.2      27  5677.2      30  5697.2    21.5
  5707.2    21.3  5747.2    29.8  5857.2    28.4  5927.2    21.5  6647.2    22.4
#Mann= 5 , 1 , 0
  2981.5      .2       0  2981.5      .1       0  4912.9    .035       0
  5134.4      .1       0  6647.2      .2       0
#XS Ineff= 2 , 0
       0                  5178.4       0      30
Permanent Ineff=
       F       F
Bank Sta=4912.9,5134.4
XS Rating Curve= 0 ,0
Exp/Cntr=0.5,0.3

Type RM Length L Ch R = 1 ,17152.1 ,110,110,110
BEGIN DESCRIPTION:
Upstream Section of Bridge/Culvert/Weir
END DESCRIPTION:
XS GIS Cut Line= 6
      3178461.17     13847290.73      3177827.65     13847278.73
      3177359.27     13847168.29      3175513.65     13846541.65
      3175172.61      13846477.8      3173420.12     13846325.83
#Sta/Elev= 30
  3395.1   36.05  3505.1   34.55  3585.1   28.65  3605.1   26.25  3635.1   17.55
  4294.3   21.95  4494.3   17.55  4544.3   11.95  4730.4    3.71    4861   10.51
  4872.4    5.83  4882.4    6.61  4917.8  -11.35  4939.2  -18.61  4952.2  -17.12
  4993.7  -20.18  5084.5   -7.12  5115.8    5.15  5198.4    5.07  5222.4    9.74
  5328.2   17.75  5459.1   21.47  5756.2   18.95  5836.2   15.85  5967.3   20.45
  6187.3   22.55  6425.7   20.15  7405.4   21.55  7545.6   24.32  8565.4   26.95
#Mann= 5 , 1 , 0
  3395.1      .2       0  3395.1      .1       0  4882.4    .035       0
  5115.8      .1       0  7545.6      .2       0
#XS Ineff= 2 , 0
       0    4820      20    5257       0      20
Permanent Ineff=
       F       F
Bank Sta=4882.4,5115.8
XS Rating Curve= 0 ,0
Exp/Cntr=0.5,0.3

Type RM Length L Ch R = 3 ,17097.1 ,,,
BEGIN DESCRIPTION:
MARKET ROAD
Structure ID: N00-4
END DESCRIPTION:
Bridge Culvert--1,0,-1,-1, 0
Deck Dist Width WeirC Skew NumUp NumDn MinLoCord MaxHiCord MaxSubmerge Is_Ogee
10,90,2.6,0, 60, 60, , , 0.95, 0, 1,1,,
  3395.1  3475.1  3505.1  3585.1  3605.1  3625.1  3635.1  3876.3  4194.3  4254.3
  4294.3 4468.49  4468.6  4494.3  4514.3  4544.3  4578.4  4608.3  4664.7  4730.4
 4831.01  4831.1  4897.5  5097.4 5246.29  5246.4  5328.2  5459.1  5520.3  5526.2
  5536.2  5556.2  5602.8 5602.91  5736.2  5756.2  5786.2  5836.2  5866.2  5886.2
  5896.2  5967.3  6137.3  6167.3  6187.3  6217.3  6267.3  6425.7  6495.4  6595.4
  7405.4  7445.4  7575.4  7775.4  8025.4  8085.4  8165.4  8345.4  8535.4  8565.4
      36   35.51   34.51   28.61   26.21   19.71   17.72    18.9    23.1   23.84
   24.34    26.5      29      29      29      29      29   29.55   30.76   32.08
   33.05   33.05   34.49   34.62   32.26   32.26   30.93    28.4   27.22   27.11
   26.92   26.63   26.63   24.13   20.26   19.69   19.26   18.54   18.11   18.01
   17.71   20.41   22.01   21.61   22.51   21.11   21.61   20.11   21.41   20.81
    21.5    23.5    24.5    23.9    25.7    24.7    25.6    24.6    25.9    26.9
      36    35.5    34.5    28.6    26.2    19.7    17.5   18.89    21.7    20.9
    21.9   17.91   17.91    17.5    15.9    11.9    11.4    8.56    8.34    3.66
    8.73   25.65   27.09   27.22   24.86    11.7    17.7   21.42   21.06    19.7
    19.5    20.6      20      20    18.4    18.9    16.7    15.8    16.3      18
    17.7    20.4      22    21.6    22.5    21.1    21.6    20.1    21.4    20.8
    21.5    23.5    24.5    23.9    25.7    24.7    25.6    24.6    25.9    26.9
  3395.1  3475.1  3505.1  3585.1  3605.1  3625.1  3635.1  3876.3  4194.3  4254.3
  4294.3 4468.49  4468.6  4494.3  4514.3  4544.3  4578.4  4608.3  4664.7  4730.4
 4831.01  4831.1  4897.5  5097.4 5246.29  5246.4  5328.2  5459.1  5520.3  5526.2
  5536.2  5556.2  5602.8 5602.91  5736.2  5756.2  5786.2  5836.2  5866.2  5886.2
  5896.2  5967.3  6137.3  6167.3  6187.3  6217.3  6267.3  6425.7  6495.4  6595.4
  7405.4  7445.4  7575.4  7775.4  8025.4  8085.4  8165.4  8345.4  8535.4  8565.4
      36   35.51   34.51   28.61   26.21   19.71   17.72    18.9    23.1   23.84
   24.34    26.5      29      29      29      29      29   29.55   30.76   32.08
   33.05   33.05   34.49   34.62   32.26   32.26   30.93    28.4   27.22   27.11
   26.92   26.63   26.63   24.13   20.26   19.69   19.26   18.54   18.11   18.01
   17.71   20.41   22.01   21.61   22.51   21.11   21.61   20.11   21.41   20.81
    21.5    23.5    24.5    23.9    25.7    24.7    25.6    24.6    25.9    26.9
    35.8    35.3    34.3    28.4      26    19.5    17.3   18.69    21.5    20.7
    21.7   17.71   17.71    17.3    15.7    11.7    11.2    8.36    8.14    3.46
    8.53   25.45   26.89   27.02   24.66    11.5    17.5   21.22   20.86    19.5
    19.3    20.4    19.8    19.8    18.2    18.7    16.5    15.6    16.1    17.8
    17.5    20.2    21.8    21.4    22.3    20.9    21.4    19.9    21.2    20.6
    21.3    23.3    24.3    23.7    25.5    24.5    25.4    24.4    25.7    26.7
Pier Skew, UpSta & Num, DnSta & Num=  ,4939.2, 2 ,4939.2, 2 , 0 , 0 , 0 ,,
       3       3
  -19.49   28.37
       3       3
  -19.69   28.17
Pier Skew, UpSta & Num, DnSta & Num=  ,5043.2, 2 ,5043.2, 2 , 0 , 0 , 0 ,,
       3       3
  -12.98   28.45
       3       3
  -13.18   28.25
Pier Skew, UpSta & Num, DnSta & Num=  ,5147.5, 2 ,5147.5, 2 , 0 , 0 , 0 ,,
       3       3
     4.4   27.65
       3       3
     4.2   27.45
Abutment Skew #Up #Dn= , 2 , 2
  4830.9    4861
   25.65   10.46
  4830.9    4861
   25.45   10.26
Abutment Skew #Up #Dn= , 2 , 2
  5191.9 5246.49
     6.6   24.86
  5191.9 5246.49
     6.4   24.66
BR Coef= 1 , 1 , 0 ,1.25, 0 ,,,0.8,0,2,0,
WSPro=,,,, 1 ,,,, 0 ,,,, 0 ,,,,-1 ,-1 ,-1 , 0 , 0 , 0 , 0 , 0
BR U #Sta/Elev= 136
  3395.1      36  3436.3   35.74  3475.1    35.5  3496.3   34.79  3505.1    34.5
  3585.1    28.6  3605.1    26.2  3615.1    23.4  3625.1    19.7  3635.1    17.5
  3665.1      18  3666.3   18.01  3786.3   18.51  3816.3   18.63  3846.3   18.76
  3866.3   18.84  3876.3   18.89  3896.3   18.97  3975.1    19.3  4194.3    21.7
  4254.3    20.9  4294.3    21.9  4394.3    19.1 4468.49   17.91  4468.6   17.91
 4468.71   17.91  4494.3    17.5  4514.3    15.9  4534.3    12.7  4544.3    11.9
  4548.4    11.9  4578.4    11.4    4582   11.06  4608.3    8.56  4610.9    8.85
    4639    8.58  4664.7    8.34  4694.3    6.23  4730.4    3.66  4755.7    4.84
  4795.9    6.71  4830.9    8.73 4831.01    8.73  4831.1    8.74  4860.9   10.45
    4861   10.46  4872.4    5.78  4882.4    6.56  4892.4     .51  4897.5   -1.88
  4917.8   -11.4  4939.2  -18.66  4952.2  -17.17    4963  -17.97  4993.7  -20.23
  5029.7  -13.89  5043.2  -11.51  5049.8   -13.6  5084.5   -7.17  5097.4      -3
  5107.5     .26  5115.8     5.1  5147.5    5.41  5165.8     5.9  5191.8     6.6
  5191.9     6.6  5198.4    5.02  5222.4    9.69  5241.6    11.3 5246.29   11.69
  5246.4    11.7  5246.5   11.71  5270.2   13.69  5321.7   17.25  5328.2    17.7
  5376.1   19.14  5392.9   19.65  5438.1   20.86  5459.1   21.42  5520.1   21.06
  5520.3   21.06  5526.1   19.72  5526.2    19.7  5536.2    19.5  5546.2    20.3
  5551.1   20.45  5556.2    20.6  5576.2    20.5  5596.2    20.2 5602.69   20.01
  5602.8      20 5602.91      20  5616.2    19.6  5656.2      19  5726.2    18.9
  5736.2    18.4  5746.2    18.9  5755.6    18.9  5756.2    18.9  5776.2    17.2
  5786.2    16.7  5796.2      17  5836.2    15.8  5866.2    16.3  5886.2      18
  5896.2    17.7  5967.3    20.4  6089.4   21.55  6137.3      22  6167.3    21.6
  6187.3    22.5  6207.3      22  6217.3    21.1  6267.3    21.6  6289.4   21.44
    6322   21.19  6415.7    20.5  6425.7    20.1  6445.4    20.5  6459.3   20.75
  6495.4    21.4  6595.4    20.8  6806.3   21.06  7395.4    21.8  7405.4    21.5
  7445.4    23.5  7545.6   24.27  7575.4    24.5  7755.4    24.4  7775.4    23.9
  8025.4    25.7  8085.4    24.7  8165.4    25.6  8345.4    24.6  8535.4    25.9
  8565.4    26.9
BR U #Mann= 5
  3395.1      .2  3395.1      .1  4882.4    .035  5115.8      .1  7545.6      .2
BR U Banks=4882.4,5115.8
BR D #Sta/Elev= 136
  3395.1    35.8  3436.3   35.54  3475.1    35.3  3496.3   34.59  3505.1    34.3
  3585.1    28.4  3605.1      26  3615.1    23.2  3625.1    19.5  3635.1    17.3
  3665.1    17.8  3666.3   17.81  3786.3   18.31  3816.3   18.43  3846.3   18.56
  3866.3   18.64  3876.3   18.69  3896.3   18.77  3975.1    19.1  4194.3    21.5
  4254.3    20.7  4294.3    21.7  4394.3    18.9 4468.49   17.71  4468.6   17.71
 4468.71   17.71  4494.3    17.3  4514.3    15.7  4534.3    12.5  4544.3    11.7
  4548.4    11.7  4578.4    11.2    4582   10.86  4608.3    8.36  4610.9    8.65
    4639    8.38  4664.7    8.14  4694.3    6.03  4730.4    3.46  4755.7    4.64
  4795.9    6.51  4830.9    8.53 4831.01    8.53  4831.1    8.54  4860.9   10.25
    4861   10.26  4872.4    5.58  4882.4    6.36  4892.4     .31  4897.5   -2.08
  4917.8   -11.6  4939.2  -18.86  4952.2  -17.37    4963  -18.17  4993.7  -20.43
  5029.7  -14.09  5043.2  -11.71  5049.8   -13.8  5084.5   -7.37  5097.4    -3.2
  5107.5     .06  5115.8     4.9  5147.5    5.21  5165.8     5.7  5191.8     6.4
  5191.9     6.4  5198.4    4.82  5222.4    9.49  5241.6    11.1 5246.29   11.49
  5246.4    11.5  5246.5   11.51  5270.2   13.49  5321.7   17.05  5328.2    17.5
  5376.1   18.94  5392.9   19.45  5438.1   20.66  5459.1   21.22  5520.1   20.86
  5520.3   20.86  5526.1   19.52  5526.2    19.5  5536.2    19.3  5546.2    20.1
  5551.1   20.25  5556.2    20.4  5576.2    20.3  5596.2      20 5602.69   19.81
  5602.8    19.8 5602.91    19.8  5616.2    19.4  5656.2    18.8  5726.2    18.7
  5736.2    18.2  5746.2    18.7  5755.6    18.7  5756.2    18.7  5776.2      17
  5786.2    16.5  5796.2    16.8  5836.2    15.6  5866.2    16.1  5886.2    17.8
  5896.2    17.5  5967.3    20.2  6089.4   21.35  6137.3    21.8  6167.3    21.4
  6187.3    22.3  6207.3    21.8  6217.3    20.9  6267.3    21.4  6289.4   21.24
    6322   20.99  6415.7    20.3  6425.7    19.9  6445.4    20.3  6459.3   20.55
  6495.4    21.2  6595.4    20.6  6806.3   20.86  7395.4    21.6  7405.4    21.3
  7445.4    23.3  7545.6   24.07  7575.4    24.3  7755.4    24.2  7775.4    23.7
  8025.4    25.5  8085.4    24.5  8165.4    25.4  8345.4    24.4  8535.4    25.7
  8565.4    26.7
BR D #Mann= 5
  3395.1      .2  3395.1      .1  4882.4    .035  5115.8      .1  7545.6      .2
BR D Banks=4882.4,5115.8
BC Design=,, 0 ,, 0 ,,,,,,
BC HTab HWMax=36.05
BC Use User HTab Curves=0
BC User HTab FreeFlow(D)= 0

Type RM Length L Ch R = 1 ,17042.1 ,644.9,644.9,644.9
BEGIN DESCRIPTION:
Downstream Section of Bridge/Culvert/Weir
END DESCRIPTION:
XS GIS Cut Line= 6
      3178539.01     13847213.01      3177905.49     13847201.01
      3177437.11     13847090.57      3175591.49     13846463.93
      3175250.45     13846400.08      3173497.96     13846248.11
#Sta/Elev= 30
  3395.1   35.73  3505.1   34.23  3585.1   28.33  3605.1   25.93  3635.1   17.23
  4294.3   21.63  4494.3   17.23  4544.3   11.63  4730.4    3.39    4861   10.19
  4872.4    5.51  4882.4    6.29  4917.8  -11.67  4939.2  -18.93  4952.2  -17.44
  4993.7   -20.5  5084.5   -7.44  5115.8    4.83  5198.4    4.75  5222.4    9.42
  5328.2   17.43  5459.1   21.15  5756.2   18.63  5836.2   15.53  5967.3   20.13
  6187.3   22.23  6425.7   19.83  7405.4   21.23  7545.6      24  8565.4   26.63
#Mann= 5 , 1 , 0
  3395.1      .2       0  3395.1      .1       0  4882.4    .035       0
  5115.8      .1       0  7545.6      .2       0
#XS Ineff= 2 , 0
       0    4820    19.8    5257       0    19.8
Permanent Ineff=
       F       F
Bank Sta=4882.4,5115.8
XS Rating Curve= 0 ,0
Exp/Cntr=0.5,0.3

Type RM Length L Ch R = 1 ,16397.2 ,335.7,274.3,140.4
BEGIN DESCRIPTION:
Cross Section 16397.2-Interpolated
END DESCRIPTION:
XS GIS Cut Line= 4
      3179561.75     13847101.75      3177537.89     13846476.73
      3177168.83      13846280.3      3175168.77     13846191.01
#Sta/Elev= 30
  2672.4    20.4  4062.4    17.4  4252.4    18.6  4312.4    18.1  4332.4    16.7
  4452.4    14.4  4790.6    13.2  4830.6    11.7  4850.6     8.4  4926.3     7.1
    4941    3.16  4967.9  -20.49  4978.5  -24.51  5002.4     -25  5017.3  -20.77
  5026.6  -20.22    5059    3.16  5069.9    6.18  5140.6     9.4  5150.6    11.1
  5160.6    10.3  5248.7      12  5338.7    11.8  5388.7    10.5  5448.7    11.1
  5508.7    13.6  6018.7    12.6  6108.7    13.8  6468.7    14.5  7210.7      22
#Mann= 5 , 1 , 0
  2672.4      .2       0  2672.4      .1       0  4926.3    .035       0
  5069.9      .1       0  7210.7      .2       0
Bank Sta=4926.3,5069.9
XS Rating Curve= 0 ,0
Exp/Cntr=0.5,0.3

Type RM Length L Ch R = 1 ,16122.9 ,31,31,31
BEGIN DESCRIPTION:
Upstream Section of Bridge/Culvert/Weir
END DESCRIPTION:
XS GIS Cut Line= 6
      3178916.33     13846201.61      3177819.05     13846143.07
      3177414.35     13846110.13      3177164.94     13846096.01
      3177009.64     13846096.01      3176021.51     13846034.98
#Sta/Elev= 30
  3575.3   29.89  4241.8   17.59  4471.8   16.89  4561.8   13.29  4693.9       4
  4804.4    2.41  4926.3    4.69  4941.1    1.11  4952.2  -16.29  4978.5  -26.92
  5002.4  -27.41  5017.3  -23.18  5026.6  -22.63    5059     .75  5069.9    3.77
  5270.4    5.19  5300.4    7.49  5345.4    5.69  5440.4    9.19  5480.7    7.99
  5505.7    9.99  5560.7    8.29  5620.7   10.19  5645.7    8.59  5690.7   11.39
  5765.7   12.19  5780.7   10.59  5950.7   12.29    6072   11.39  6475.3   29.89
#Mann= 5 , 1 , 0
  3575.3      .2       0  4241.8      .1       0  4926.3    .035       0
  5069.9      .1       0    6072      .2       0
#XS Ineff= 2 , 0
       0    4616    28.2    5335       0    28.2
Permanent Ineff=
       F       F
Bank Sta=4926.3,5069.9
XS Rating Curve= 0 ,0
Exp/Cntr=0.5,0.3