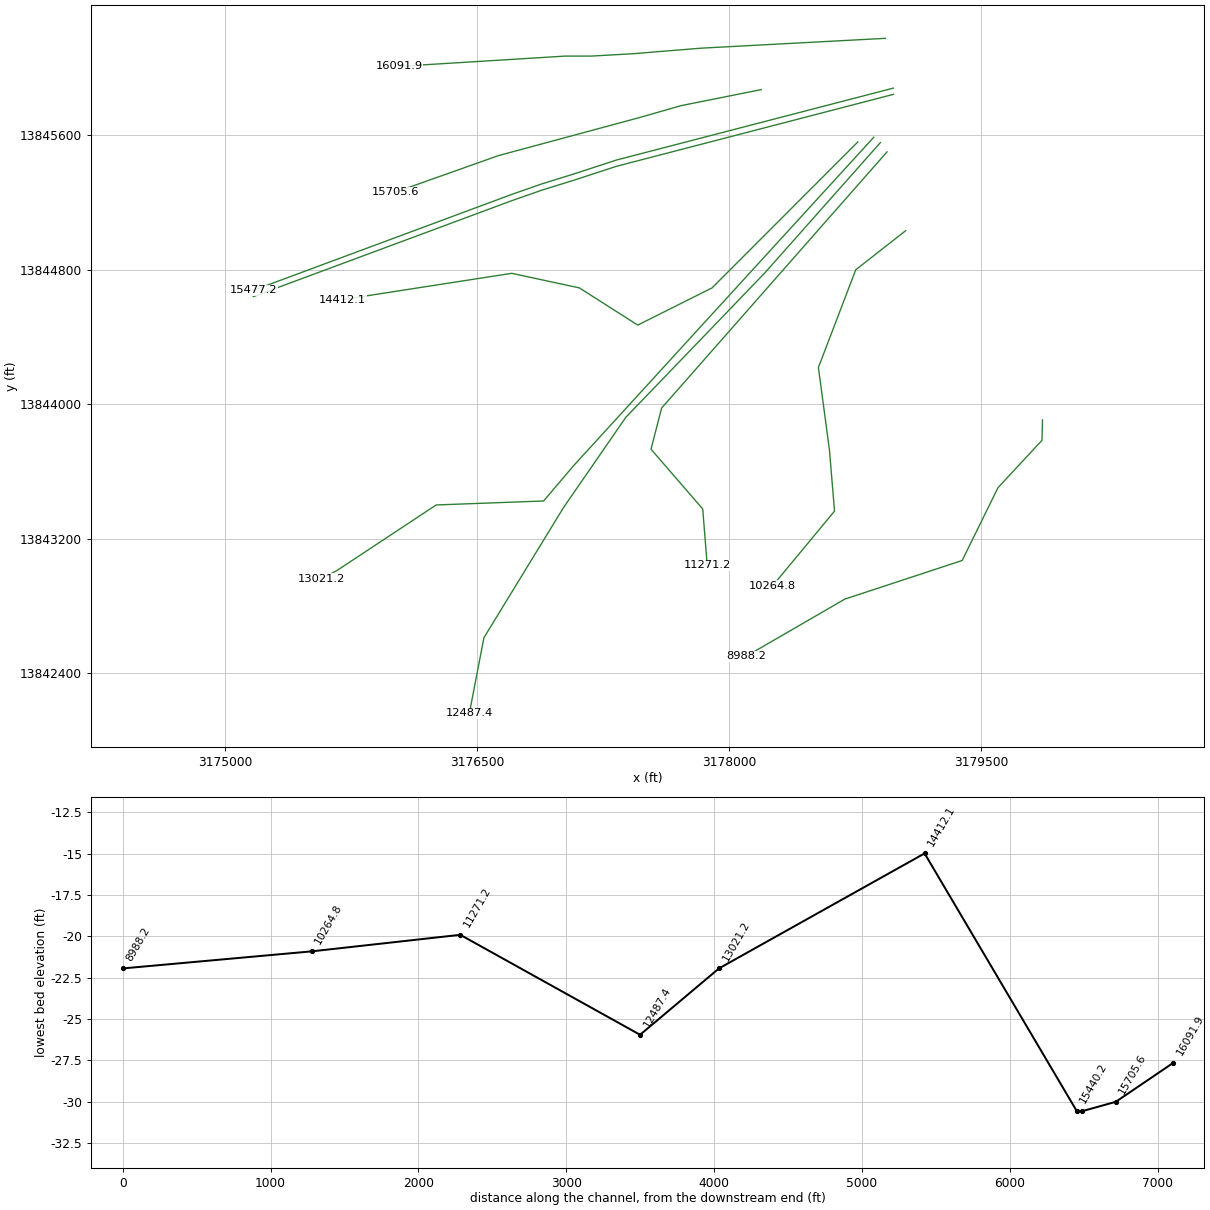
HEC-RAS study P100-00-00.prj: P100-00-00

--- P100-00-00.g01 (geometry) --- (continued)

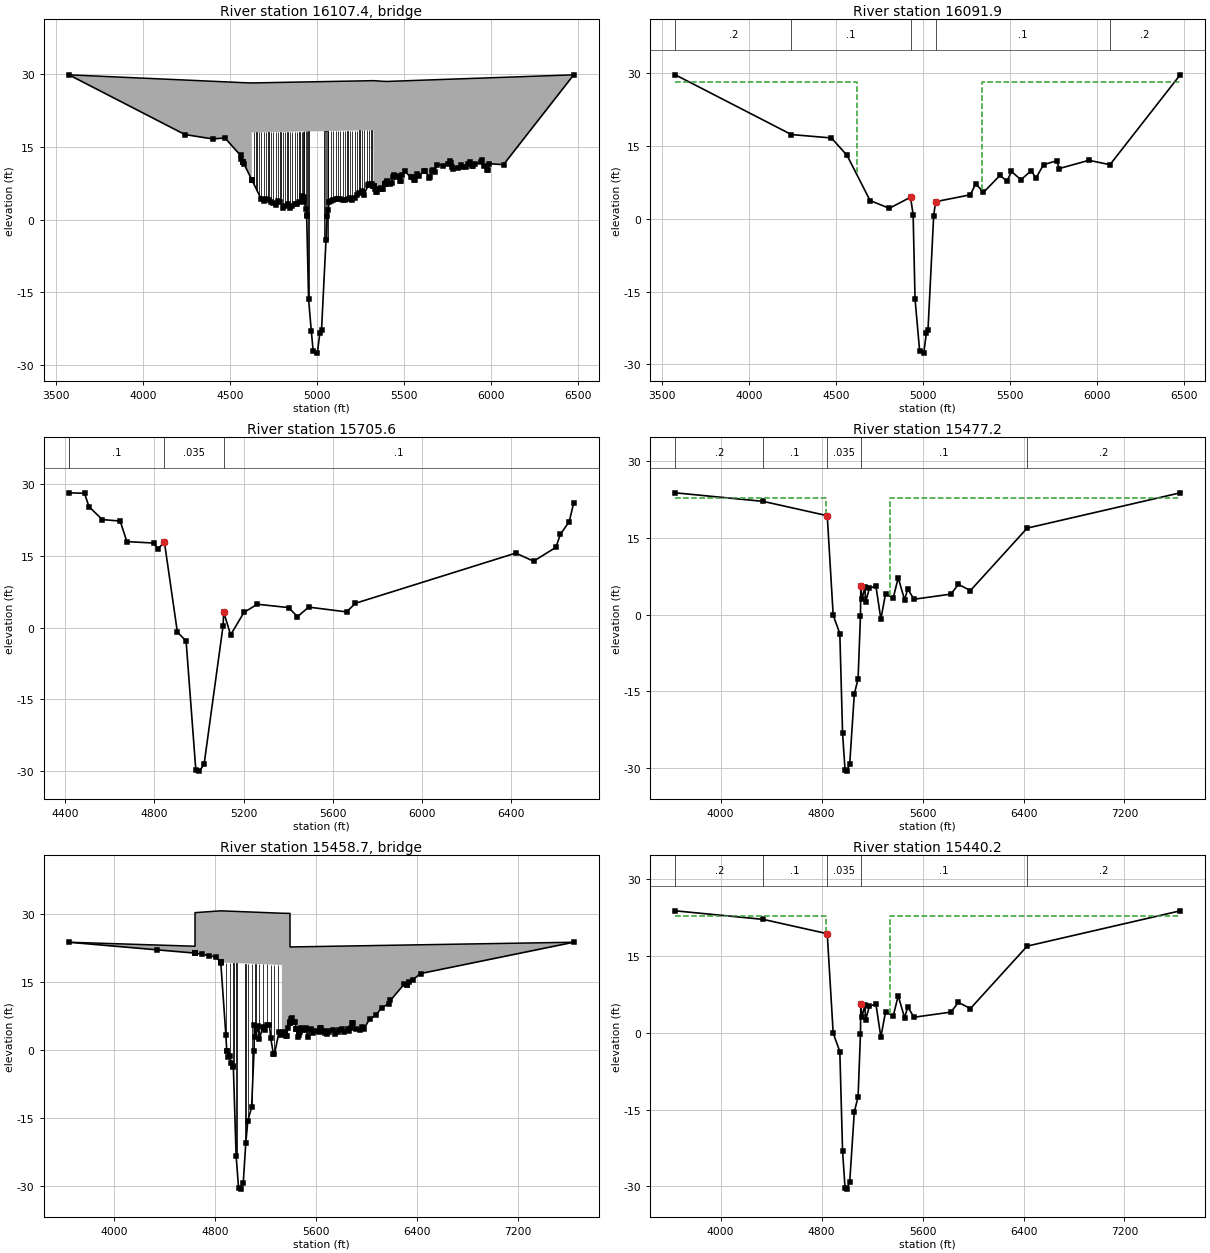
Type RM Length L Ch R = 3 ,16107.4 ,,,
BEGIN DESCRIPTION:
MISSOURI PACIFIC RAILROAD
Structure ID: P00-2
END DESCRIPTION:
Bridge Culvert--1,0,-1,-1, 0
Deck Dist Width WeirC Skew NumUp NumDn MinLoCord MaxHiCord MaxSubmerge Is_Ogee
10,11,2.6,0, 60, 60, , , 0.95, 0, 1,1,,
  3575.3  4241.8  4401.8  4471.8  4561.8  4566.8  4625.9 4626.01  4626.1 5325.09
  5325.2  5340.4  5345.4  5355.4  5370.4  5375.4  5380.4  5390.4  5405.4  5420.4
  5430.4  5435.4  5440.4  5460.7  5470.7  5475.7  5480.7  5490.7  5505.7  5560.7
  5575.7  5585.7  5615.7  5620.7  5645.7  5650.7  5660.7  5665.7  5675.7  5690.7
  5725.7  5755.7  5765.7  5780.7  5810.7  5825.7  5835.7  5855.7  5865.7  5880.7
  5890.7  5895.7  5940.7  5950.7  5960.7  5975.7  5980.7  5990.7    6072  6475.3
    29.8   28.73   28.47   28.36   28.21    28.2   28.13   28.13   28.13    28.6
    28.6   28.56   28.55   28.53   28.49   28.48   28.47   28.45   28.44   28.46
   28.48   28.48   28.49   28.51   28.53   28.53   28.54   28.55   28.57   28.64
   28.66   28.67   28.71   28.72   28.75   28.75   28.77   28.77   28.79   28.81
   28.85   28.89    28.9   28.92   28.96   28.98   28.99   29.01   29.03   29.05
   29.06   29.07   29.12   29.14   29.15   29.17   29.17   29.19   29.29    29.8
    29.8    17.5    16.6    16.8    13.2    12.5    8.19    8.18   17.93    18.4
    6.81     5.7     5.6     6.3     6.6     6.2     6.2     7.3       8     7.3
     7.5     8.8     9.1     8.7     8.9       8     7.9     9.1     9.9     8.2
     9.3     8.9    10.1    10.1     8.5     8.8    10.1    10.2     9.8    11.3
    11.1    11.5    12.1    10.5    10.6    11.2    10.9    10.8    11.5    11.8
    11.1      11    11.8    12.2      11    10.3    10.3    11.5    11.3    29.8
  3575.3  4241.8  4401.8  4471.8  4561.8  4566.8  4625.9 4626.01  4626.1 5325.09
  5325.2  5340.4  5345.4  5355.4  5370.4  5375.4  5380.4  5390.4  5405.4  5420.4
  5430.4  5435.4  5440.4  5460.7  5470.7  5475.7  5480.7  5490.7  5505.7  5560.7
  5575.7  5585.7  5615.7  5620.7  5645.7  5650.7  5660.7  5665.7  5675.7  5690.7
  5725.7  5755.7  5765.7  5780.7  5810.7  5825.7  5835.7  5855.7  5865.7  5880.7
  5890.7  5895.7  5940.7  5950.7  5960.7  5975.7  5980.7  5990.7    6072  6475.3
    29.8   28.73   28.47   28.36   28.21    28.2   28.13   28.13   28.13    28.6
    28.6   28.56   28.55   28.53   28.49   28.48   28.47   28.45   28.44   28.46
   28.48   28.48   28.49   28.51   28.53   28.53   28.54   28.55   28.57   28.64
   28.66   28.67   28.71   28.72   28.75   28.75   28.77   28.77   28.79   28.81
   28.85   28.89    28.9   28.92   28.96   28.98   28.99   29.01   29.03   29.05
   29.06   29.07   29.12   29.14   29.15   29.17   29.17   29.19   29.29    29.8
    29.7    17.4    16.5    16.7    13.1    12.4    8.09    8.08   17.83    18.3
    6.71     5.6     5.5     6.2     6.5     6.1     6.1     7.2     7.9     7.2
     7.4     8.7       9     8.6     8.8     7.9     7.8       9     9.8     8.1
     9.2     8.8      10      10     8.4     8.7      10    10.1     9.7    11.2
      11    11.4      12    10.4    10.5    11.1    10.8    10.7    11.4    11.7
      11    10.9    11.7    12.1    10.9    10.2    10.2    11.4    11.2    29.7
Pier Skew, UpSta & Num, DnSta & Num=  ,4639.1, 2 ,4639.1, 2 , 0 , 0 , 0 ,,
     1.3     1.3
    6.17   18.94
     1.3     1.3
    6.07   18.84
Pier Skew, UpSta & Num, DnSta & Num=  ,4653.3, 2 ,4653.3, 2 , 0 , 0 , 0 ,,
     1.3     1.3
    5.14   18.95
     1.3     1.3
    5.04   18.85
Pier Skew, UpSta & Num, DnSta & Num=  ,4667.3, 2 ,4667.3, 2 , 0 , 0 , 0 ,,
     1.3     1.3
    4.12   18.96
     1.3     1.3
    4.02   18.86
Pier Skew, UpSta & Num, DnSta & Num=  ,4680.2, 2 ,4680.2, 2 , 0 , 0 , 0 ,,
     1.3     1.3
    3.21   18.97
     1.3     1.3
    3.11   18.87
Pier Skew, UpSta & Num, DnSta & Num=  ,4693.9, 2 ,4693.9, 2 , 0 , 0 , 0 ,,
     1.3     1.3
    2.92   18.98
     1.3     1.3
    2.82   18.88
Pier Skew, UpSta & Num, DnSta & Num=  ,4707.1, 2 ,4707.1, 2 , 0 , 0 , 0 ,,
     1.3     1.3
    3.16   18.98
     1.3     1.3
    3.06   18.88
Pier Skew, UpSta & Num, DnSta & Num=  ,4722.3, 2 ,4722.3, 2 , 0 , 0 , 0 ,,
     1.3     1.3
    3.09   18.99
     1.3     1.3
    2.99   18.89
Pier Skew, UpSta & Num, DnSta & Num=  ,4735.7, 2 ,4735.7, 2 , 0 , 0 , 0 ,,
     1.3     1.3
    2.68      19
     1.3     1.3
    2.58    18.9
Pier Skew, UpSta & Num, DnSta & Num=  ,4749, 2 ,4749, 2 , 0 , 0 , 0 ,,
     1.3     1.3
    2.42   19.01
     1.3     1.3
    2.32   18.91
Pier Skew, UpSta & Num, DnSta & Num=  ,4763, 2 ,4763, 2 , 0 , 0 , 0 ,,
     1.3     1.3
    1.93   19.02
     1.3     1.3
    1.83   18.92
Pier Skew, UpSta & Num, DnSta & Num=  ,4776.3, 2 ,4776.3, 2 , 0 , 0 , 0 ,,
     1.3     1.3
    2.69   19.03
     1.3     1.3
    2.59   18.93
Pier Skew, UpSta & Num, DnSta & Num=  ,4790.5, 2 ,4790.5, 2 , 0 , 0 , 0 ,,
     1.3     1.3
    2.46   19.04
     1.3     1.3
    2.36   18.94
Pier Skew, UpSta & Num, DnSta & Num=  ,4804.4, 2 ,4804.4, 2 , 0 , 0 , 0 ,,
     1.3     1.3
    1.34   19.05
     1.3     1.3
    1.24   18.95
Pier Skew, UpSta & Num, DnSta & Num=  ,4817.7, 2 ,4817.7, 2 , 0 , 0 , 0 ,,
     1.3     1.3
    1.73   19.06
     1.3     1.3
    1.63   18.96
Pier Skew, UpSta & Num, DnSta & Num=  ,4831.5, 2 ,4831.5, 2 , 0 , 0 , 0 ,,
     1.3     1.3
    2.25   19.07
     1.3     1.3
    2.15   18.97
Pier Skew, UpSta & Num, DnSta & Num=  ,4844.5, 2 ,4844.5, 2 , 0 , 0 , 0 ,,
     1.3     1.3
    1.47   19.08
     1.3     1.3
    1.37   18.98
Pier Skew, UpSta & Num, DnSta & Num=  ,4859, 2 ,4859, 2 , 0 , 0 , 0 ,,
     1.3     1.3
    1.73   19.09
     1.3     1.3
    1.63   18.99
Pier Skew, UpSta & Num, DnSta & Num=  ,4873.1, 2 ,4873.1, 2 , 0 , 0 , 0 ,,
     1.3     1.3
    2.12    19.1
     1.3     1.3
    2.02      19
Pier Skew, UpSta & Num, DnSta & Num=  ,4886.3, 2 ,4886.3, 2 , 0 , 0 , 0 ,,
     1.3     1.3
    2.21   19.11
     1.3     1.3
    2.11   19.01
Pier Skew, UpSta & Num, DnSta & Num=  ,4899.5, 2 ,4899.5, 2 , 0 , 0 , 0 ,,
     1.3     1.3
     2.6   19.11
     1.3     1.3
     2.5   19.01
Pier Skew, UpSta & Num, DnSta & Num=  ,4914.2, 2 ,4914.2, 2 , 0 , 0 , 0 ,,
     1.3     1.3
    3.87   19.12
     1.3     1.3
    3.77   19.02
Pier Skew, UpSta & Num, DnSta & Num=  ,4922.7, 2 ,4922.7, 2 , 0 , 0 , 0 ,,
     1.3     1.3
    3.17   19.13
     1.3     1.3
    3.07   19.03
Pier Skew, UpSta & Num, DnSta & Num=  ,4927, 2 ,4927, 2 , 0 , 0 , 0 ,,
     1.3     1.3
    2.52   19.13
     1.3     1.3
    2.42   19.03
Pier Skew, UpSta & Num, DnSta & Num=  ,4938.3, 2 ,4938.3, 2 , 0 , 0 , 0 ,,
     1.3     1.3
     .78   19.14
     1.3     1.3
     .68   19.04
Pier Skew, UpSta & Num, DnSta & Num=  ,4941.1, 2 ,4941.1, 2 , 0 , 0 , 0 ,,
     1.3     1.3
      -1   19.14
     1.3     1.3
    -1.1   19.04
Pier Skew, UpSta & Num, DnSta & Num=  ,4952.2, 2 ,4952.2, 2 , 0 , 0 , 0 ,,
       6       6
  -18.64   19.15
       6       6
  -18.74   19.05
Pier Skew, UpSta & Num, DnSta & Num=  ,5052, 2 ,5052, 2 , 0 , 0 , 0 ,,
      18      18
  -11.74   19.22
      18      18
  -11.84   19.12
Pier Skew, UpSta & Num, DnSta & Num=  ,5065.7, 2 ,5065.7, 2 , 0 , 0 , 0 ,,
     1.3     1.3
     .82   19.23
     1.3     1.3
     .72   19.13
Pier Skew, UpSta & Num, DnSta & Num=  ,5079.1, 2 ,5079.1, 2 , 0 , 0 , 0 ,,
     1.3     1.3
    2.83   19.23
     1.3     1.3
    2.73   19.13
Pier Skew, UpSta & Num, DnSta & Num=  ,5093.2, 2 ,5093.2, 2 , 0 , 0 , 0 ,,
     1.3     1.3
    2.97   19.24
     1.3     1.3
    2.87   19.14
Pier Skew, UpSta & Num, DnSta & Num=  ,5107.7, 2 ,5107.7, 2 , 0 , 0 , 0 ,,
     1.3     1.3
    3.28   19.25
     1.3     1.3
    3.18   19.15
Pier Skew, UpSta & Num, DnSta & Num=  ,5120.9, 2 ,5120.9, 2 , 0 , 0 , 0 ,,
     1.3     1.3
    3.22   19.26
     1.3     1.3
    3.12   19.16
Pier Skew, UpSta & Num, DnSta & Num=  ,5134.9, 2 ,5134.9, 2 , 0 , 0 , 0 ,,
     1.3     1.3
    3.14   19.27
     1.3     1.3
    3.04   19.17
Pier Skew, UpSta & Num, DnSta & Num=  ,5148.6, 2 ,5148.6, 2 , 0 , 0 , 0 ,,
     1.3     1.3
    3.11   19.28
     1.3     1.3
    3.01   19.18
Pier Skew, UpSta & Num, DnSta & Num=  ,5162.4, 2 ,5162.4, 2 , 0 , 0 , 0 ,,
     1.3     1.3
    3.08   19.29
     1.3     1.3
    2.98   19.19
Pier Skew, UpSta & Num, DnSta & Num=  ,5175.9, 2 ,5175.9, 2 , 0 , 0 , 0 ,,
     1.3     1.3
    3.31    19.3
     1.3     1.3
    3.21    19.2
Pier Skew, UpSta & Num, DnSta & Num=  ,5189.9, 2 ,5189.9, 2 , 0 , 0 , 0 ,,
     1.3     1.3
    3.37   19.31
     1.3     1.3
    3.27   19.21
Pier Skew, UpSta & Num, DnSta & Num=  ,5203.5, 2 ,5203.5, 2 , 0 , 0 , 0 ,,
     1.3     1.3
    3.13   19.32
     1.3     1.3
    3.03   19.22
Pier Skew, UpSta & Num, DnSta & Num=  ,5217.3, 2 ,5217.3, 2 , 0 , 0 , 0 ,,
     1.3     1.3
    3.52   19.33
     1.3     1.3
    3.42   19.23
Pier Skew, UpSta & Num, DnSta & Num=  ,5230.4, 2 ,5230.4, 2 , 0 , 0 , 0 ,,
     1.3     1.3
    4.01   19.34
     1.3     1.3
    3.91   19.24
Pier Skew, UpSta & Num, DnSta & Num=  ,5244.6, 2 ,5244.6, 2 , 0 , 0 , 0 ,,
     1.3     1.3
    4.51   19.35
     1.3     1.3
    4.41   19.25
Pier Skew, UpSta & Num, DnSta & Num=  ,5258.3, 2 ,5258.3, 2 , 0 , 0 , 0 ,,
     1.3     1.3
    4.85   19.36
     1.3     1.3
    4.75   19.26
Pier Skew, UpSta & Num, DnSta & Num=  ,5272.4, 2 ,5272.4, 2 , 0 , 0 , 0 ,,
     1.3     1.3
    4.21   19.36
     1.3     1.3
    4.11   19.26
Pier Skew, UpSta & Num, DnSta & Num=  ,5286.2, 2 ,5286.2, 2 , 0 , 0 , 0 ,,
     1.3     1.3
    5.37   19.37
     1.3     1.3
    5.27   19.27
Pier Skew, UpSta & Num, DnSta & Num=  ,5299.6, 2 ,5299.6, 2 , 0 , 0 , 0 ,,
     1.3     1.3
    6.34   19.38
     1.3     1.3
    6.24   19.28
Pier Skew, UpSta & Num, DnSta & Num=  ,5313.4, 2 ,5313.4, 2 , 0 , 0 , 0 ,,
     1.3     1.3
    6.35   19.39
     1.3     1.3
    6.25   19.29
BR Coef= 1 , 1 , 0 ,1.25, 0 ,,,0.8,0,2,0,
WSPro=,,,, 1 ,,,, 0 ,,,, 0 ,,,,-1 ,-1 ,-1 , 0 , 0 , 0 , 0 , 0
BR U #Sta/Elev= 134
  3575.3    29.8  4241.8    17.5  4401.8    16.6  4471.8    16.8  4561.8    13.2
  4566.8    12.5 4574.49   11.94  4574.6   11.93 4574.71   11.92  4575.3   11.88
  4581.8    11.4  4625.9    8.19 4626.01    8.18  4626.1    8.17  4626.2    8.16
  4680.2    4.23  4693.9    3.91  4707.1    4.17  4722.3    4.11  4735.7    3.69
    4749    3.45    4763     2.9  4776.3    3.73  4790.5    3.52  4804.4    2.32
  4817.7    2.75  4831.5    3.29  4844.5    2.46    4859    2.74  4873.1    3.14
  4886.3    3.21  4899.5    3.62  4914.2    4.93  4922.7    4.11  4926.3     4.6
    4927     3.6  4938.3    2.14    4941     .66  4941.1    1.02  4952.2  -16.38
  4967.9  -22.99  4978.5  -27.01  5002.4   -27.5  5017.3  -23.27  5026.6  -22.72
    5052   -4.16    5059     .66  5065.7    1.95  5069.9    3.68  5079.1    3.84
  5093.2    3.98  5107.7    4.29  5120.9    4.22  5134.9    4.14  5148.6    4.11
  5162.4    4.08  5175.9    4.32  5189.9    4.38  5203.5    4.12  5217.3    4.54
  5230.4    5.03  5244.6    5.53  5258.3    5.89  5270.4     5.1  5295.4     7.2
  5300.4     7.4  5305.4     7.2  5315.4     7.4    5325    6.82 5325.09    6.82
  5325.2    6.81  5325.3    6.81  5335.4     6.2  5340.4     5.7  5345.4     5.6
  5355.4     6.3  5370.4     6.6  5375.4     6.2  5380.4     6.2  5390.4     7.3
 5392.89     7.4    5393     7.4 5393.11    7.41  5394.5    7.46  5400.4     7.7
  5405.4       8  5420.4     7.3  5430.4     7.5  5435.4     8.8  5440.4     9.1
  5445.7     8.9  5460.7     8.7  5470.7     8.9  5475.7       8  5480.7     7.9
  5490.7     9.1  5505.7     9.9  5540.7     8.7  5545.7     8.8  5555.7     8.2
  5560.7     8.2  5575.7     9.3  5585.7     8.9  5615.7    10.1  5620.7    10.1
  5645.7     8.5  5650.7     8.8  5660.7    10.1  5665.7    10.2  5675.7     9.8
  5690.7    11.3  5725.7    11.1  5755.7    11.5  5765.7    12.1  5770.7    11.7
  5775.7    10.9  5780.7    10.5  5810.7    10.6  5825.7    11.2  5835.7    10.9
  5855.7    10.8  5865.7    11.5  5880.7    11.8  5890.7    11.1  5895.7      11
  5910.7    11.4  5940.7    11.8  5950.7    12.2  5960.7      11  5975.7    10.3
  5980.7    10.3  5990.7    11.5    6072    11.3  6475.3    29.8
BR U #Mann= 5
  3575.3      .2  4241.8      .1  4926.3    .035  5069.9      .1    6072      .2
BR U Banks=4926.3,5069.9
BR D #Sta/Elev= 134
  3575.3    29.7  4241.8    17.4  4401.8    16.5  4471.8    16.7  4561.8    13.1
  4566.8    12.4 4574.49   11.84  4574.6   11.83 4574.71   11.82  4575.3   11.78
  4581.8    11.3  4625.9    8.09 4626.01    8.08  4626.1    8.07  4626.2    8.06
  4680.2    4.13  4693.9    3.81  4707.1    4.07  4722.3    4.01  4735.7    3.59
    4749    3.35    4763     2.8  4776.3    3.63  4790.5    3.42  4804.4    2.22
  4817.7    2.65  4831.5    3.19  4844.5    2.36    4859    2.64  4873.1    3.04
  4886.3    3.11  4899.5    3.52  4914.2    4.83  4922.7    4.01  4926.3     4.5
    4927     3.5  4938.3    2.04    4941     .56  4941.1     .92  4952.2  -16.48
  4967.9  -23.09  4978.5  -27.11  5002.4   -27.6  5017.3  -23.37  5026.6  -22.82
    5052   -4.26    5059     .56  5065.7    1.85  5069.9    3.58  5079.1    3.74
  5093.2    3.88  5107.7    4.19  5120.9    4.12  5134.9    4.04  5148.6    4.01
  5162.4    3.98  5175.9    4.22  5189.9    4.28  5203.5    4.02  5217.3    4.44
  5230.4    4.93  5244.6    5.43  5258.3    5.79  5270.4       5  5295.4     7.1
  5300.4     7.3  5305.4     7.1  5315.4     7.3    5325    6.72 5325.09    6.72
  5325.2    6.71  5325.3    6.71  5335.4     6.1  5340.4     5.6  5345.4     5.5
  5355.4     6.2  5370.4     6.5  5375.4     6.1  5380.4     6.1  5390.4     7.2
 5392.89     7.3    5393     7.3 5393.11    7.31  5394.5    7.36  5400.4     7.6
  5405.4     7.9  5420.4     7.2  5430.4     7.4  5435.4     8.7  5440.4       9
  5445.7     8.8  5460.7     8.6  5470.7     8.8  5475.7     7.9  5480.7     7.8
  5490.7       9  5505.7     9.8  5540.7     8.6  5545.7     8.7  5555.7     8.1
  5560.7     8.1  5575.7     9.2  5585.7     8.8  5615.7      10  5620.7      10
  5645.7     8.4  5650.7     8.7  5660.7      10  5665.7    10.1  5675.7     9.7
  5690.7    11.2  5725.7      11  5755.7    11.4  5765.7      12  5770.7    11.6
  5775.7    10.8  5780.7    10.4  5810.7    10.5  5825.7    11.1  5835.7    10.8
  5855.7    10.7  5865.7    11.4  5880.7    11.7  5890.7      11  5895.7    10.9
  5910.7    11.3  5940.7    11.7  5950.7    12.1  5960.7    10.9  5975.7    10.2
  5980.7    10.2  5990.7    11.4    6072    11.2  6475.3    29.7
BR D #Mann= 5
  3575.3      .2  4241.8      .1  4926.3    .035  5069.9      .1    6072      .2
BR D Banks=4926.3,5069.9
BC Design=,, 0 ,, 0 ,,,,,,
BC HTab HWMax=29.89
BC Use User HTab Curves=0
BC User HTab FreeFlow(D)= 0

Type RM Length L Ch R = 1 ,16091.9 ,386.3,386.3,386.3
BEGIN DESCRIPTION:
Downstream Section of Bridge/Culvert/Weir
END DESCRIPTION:
XS GIS Cut Line= 6
      3178931.07     13846174.33      3177833.79     13846115.79
      3177429.09     13846082.85      3177179.68     13846068.73
      3177024.38     13846068.73      3176036.25      13846007.7
#Sta/Elev= 30
  3575.3   29.64  4241.8   17.34  4471.8   16.64  4561.8   13.04  4693.9    3.75
  4804.4    2.16  4926.3    4.44  4941.1     .86  4952.2  -16.54  4978.5  -27.17
  5002.4  -27.66  5017.3  -23.43  5026.6  -22.88    5059      .5  5069.9    3.52
  5270.4    4.94  5300.4    7.24  5345.4    5.44  5440.4    8.94  5480.7    7.74
  5505.7    9.74  5560.7    8.04  5620.7    9.94  5645.7    8.34  5690.7   11.14
  5765.7   11.94  5780.7   10.34  5950.7   12.04    6072   11.14  6475.3   29.64
#Mann= 5 , 1 , 0
  3575.3      .2       0  4241.8      .1       0  4926.3    .035       0
  5069.9      .1       0    6072      .2       0
#XS Ineff= 2 , 0
       0    4616    28.2    5335       0    28.2
Permanent Ineff=
       F       F
Bank Sta=4926.3,5069.9
XS Rating Curve= 0 ,0
Exp/Cntr=0.5,0.3

Type RM Length L Ch R = 1 ,15705.6 ,230.5,228.4,185
BEGIN DESCRIPTION:
Cross Section 15705.6-Interpolated
END DESCRIPTION:
XS GIS Cut Line= 5
      3178192.67     13845869.57      3177716.46     13845774.33
      3177466.46      13845702.9      3176627.15      13845476.7
      3176014.48     13845259.48
#Sta/Elev= 30
  4416.3    28.2  4486.3    28.1  4506.3    25.3  4566.3    22.6  4646.3    22.3
  4676.3      18  4796.3    17.7  4816.3    16.5  4844.7   17.93  4902.9    -.91
  4942.1    -2.8  4985.7  -29.75  5001.7     -30  5022.9  -28.54    5108     .39
  5110.9    3.24  5141.9    -1.5  5201.9     3.2  5261.9     4.9  5401.9     4.2
  5441.9     2.3  5491.9     4.3  5661.9     3.3  5701.9     5.1  6421.2    15.6
  6501.2    13.9  6601.2    16.8  6621.2    19.5  6661.2    22.2  6681.2    26.1
#Mann= 4 , 1 , 0
  4416.3      .2       0  4416.3      .1       0  4844.7    .035       0
  5110.9      .1       0
Bank Sta=4844.7,5110.9
XS Rating Curve= 0 ,0
Exp/Cntr=0.5,0.3

Type RM Length L Ch R = 1 ,15477.2 ,37,37,37
BEGIN DESCRIPTION:
Upstream Section of Bridge/Culvert/Weir
END DESCRIPTION:
XS GIS Cut Line= 6
      3178979.21     13845878.49      3177331.18     13845450.87
      3177071.68     13845366.25       3176885.9     13845308.74
       3176708.5     13845246.67      3175168.92     13844675.78
#Sta/Elev= 30
  3641.3   23.83  4336.8   22.16  4844.7   19.36  4891.8    -.08  4944.4   -3.69
  4966.2  -23.17  4985.7  -30.32  5001.7  -30.57  5022.9  -29.11  5059.2  -15.48
  5089.1  -12.52    5108    -.18  5110.9    5.67    5119       3  5143.2    5.39
  5148.9    2.41  5178.7    5.26  5230.7    5.55  5269.5    -.85  5307.1    4.13
  5367.1    3.23  5407.1    7.23  5457.4    2.93  5482.4    5.03  5532.4    3.03
  5824.2    4.03  5884.2    5.93  5979.2    4.73  6428.8   16.93  7641.3   23.83
#Mann= 5 , 1 , 0
  3641.3      .2       0  4336.8      .1       0  4844.7    .035       0
  5110.9      .1       0  6428.8      .2       0
#XS Ineff= 2 , 0
       0    4833    22.8    5340       0    22.8
Permanent Ineff=
       F       F
Bank Sta=4844.7,5110.9
XS Rating Curve= 0 ,0
Exp/Cntr=0.5,0.3

Type RM Length L Ch R = 3 ,15458.7 ,,,
BEGIN DESCRIPTION:
PORT TERMINAL RAILROAD ASSOCIATION RAILROAD
Structure ID: P00-1
END DESCRIPTION:
Bridge Culvert--1,0,-1,-1, 0
Deck Dist Width WeirC Skew NumUp NumDn MinLoCord MaxHiCord MaxSubmerge Is_Ogee
10,17,2.6,0, 60, 60, , , 0.95, 0, 1,1,,
  3641.3 4640.49  4640.6  4808.8  4844.7 5329.19  5329.3  5337.1  5352.1  5362.1
  5367.1  5377.1  5393.2 5393.31  5407.1  5427.1  5432.1  5442.1  5457.4  5482.4
  5487.4  5517.4  5522.4  5532.4  5562.4  5572.4  5597.4  5622.4  5632.4  5637.4
  5647.4  5657.4  5667.4  5672.4  5687.4  5697.4  5732.4  5747.4  5774.2  5779.2
  5809.2  5824.2  5849.2  5859.2  5874.2  5884.2  5914.2  5949.2  5964.2  5979.2
  6024.2  6074.2  6119.2  6174.2  6189.2  6299.2  6319.2  6334.2  6428.8  7641.3
    23.8   22.92   30.32   30.65   30.72   30.19   30.19   30.19   30.18   30.17
   30.17   30.17   30.16   22.76   22.77   22.78   22.78   22.78   22.79    22.8
    22.8   22.82   22.82   22.82   22.84   22.84   22.85   22.87   22.87   22.87
   22.88   22.88   22.89   22.89    22.9    22.9   22.92   22.92   22.94   22.94
   22.95   22.96   22.97   22.98   22.98   22.99      23   23.02   23.02   23.03
   23.05   23.08    23.1   23.12   23.13   23.18   23.19    23.2   23.24    23.8
    23.8    21.4    21.4   20.53   19.33   18.79    3.74     4.1     3.8     3.1
     3.2       5    5.97    5.97     7.2     6.2     6.3     4.7     2.9       5
     4.4     4.8     4.5       3     4.6     3.9     4.2       4     4.9     4.9
     4.2     4.3     3.8       4     3.5     4.2     4.5     3.6       4     4.4
     4.7       4     4.6     4.3     4.8     5.9     4.6     4.5     5.1     4.7
     6.9     7.7     9.4    10.2      11    14.6    14.3      15    16.9    23.8
  3641.3 4640.49  4640.6  4808.8  4844.7 5329.19  5329.3  5337.1  5352.1  5362.1
  5367.1  5377.1  5393.2 5393.31  5407.1  5427.1  5432.1  5442.1  5457.4  5482.4
  5487.4  5517.4  5522.4  5532.4  5562.4  5572.4  5597.4  5622.4  5632.4  5637.4
  5647.4  5657.4  5667.4  5672.4  5687.4  5697.4  5732.4  5747.4  5774.2  5779.2
  5809.2  5824.2  5849.2  5859.2  5874.2  5884.2  5914.2  5949.2  5964.2  5979.2
  6024.2  6074.2  6119.2  6174.2  6189.2  6299.2  6319.2  6334.2  6428.8  7641.3
    23.8   22.92   30.32   30.65   30.72   30.19   30.19   30.19   30.18   30.17
   30.17   30.17   30.16   22.76   22.77   22.78   22.78   22.78   22.79    22.8
    22.8   22.82   22.82   22.82   22.84   22.84   22.85   22.87   22.87   22.87
   22.88   22.88   22.89   22.89    22.9    22.9   22.92   22.92   22.94   22.94
   22.95   22.96   22.97   22.98   22.98   22.99      23   23.02   23.02   23.03
   23.05   23.08    23.1   23.12   23.13   23.18   23.19    23.2   23.24    23.8
   23.71   21.31   21.31   20.44   19.24    18.7    3.65    4.01    3.71    3.01
    3.11    4.91    5.88    5.88    7.11    6.11    6.21    4.61    2.81    4.91
    4.31    4.71    4.41    2.91    4.51    3.81    4.11    3.91    4.81    4.81
    4.11    4.21    3.71    3.91    3.41    4.11    4.41    3.51    3.91    4.31
    4.61    3.91    4.51    4.21    4.71    5.81    4.51    4.41    5.01    4.61
    6.81    7.61    9.31   10.11   10.91   14.51   14.21   14.91   16.81   23.71
Pier Skew, UpSta & Num, DnSta & Num=  ,4885.3, 2 ,4885.3, 2 , 0 , 0 , 0 ,,
     1.7     1.7
    1.83   20.27
     1.7     1.7
    1.74   20.18
Pier Skew, UpSta & Num, DnSta & Num=  ,4915.3, 2 ,4915.3, 2 , 0 , 0 , 0 ,,
     1.7     1.7
   -2.37   20.24
     1.7     1.7
   -2.46   20.15
Pier Skew, UpSta & Num, DnSta & Num=  ,4944.4, 2 ,4944.4, 2 , 0 , 0 , 0 ,,
       3       3
   -6.06   20.21
       3       3
   -6.15   20.12
Pier Skew, UpSta & Num, DnSta & Num=  ,4966.2, 2 ,4966.2, 2 , 0 , 0 , 0 ,,
       7       7
  -25.48   20.19
       7       7
  -25.57    20.1
Pier Skew, UpSta & Num, DnSta & Num=  ,5042.8, 2 ,5042.8, 2 , 0 , 0 , 0 ,,
       7       7
  -23.01    20.1
       7       7
   -23.1   20.01
Pier Skew, UpSta & Num, DnSta & Num=  ,5059.2, 2 ,5059.2, 2 , 0 , 0 , 0 ,,
     1.7     1.7
  -16.77   20.08
     1.7     1.7
  -16.86   19.99
Pier Skew, UpSta & Num, DnSta & Num=  ,5089.1, 2 ,5089.1, 2 , 0 , 0 , 0 ,,
     1.7     1.7
  -13.63   20.05
     1.7     1.7
  -13.72   19.96
Pier Skew, UpSta & Num, DnSta & Num=  ,5119, 2 ,5119, 2 , 0 , 0 , 0 ,,
     1.7     1.7
    2.05   20.02
     1.7     1.7
    1.96   19.93
Pier Skew, UpSta & Num, DnSta & Num=  ,5148.9, 2 ,5148.9, 2 , 0 , 0 , 0 ,,
     1.7     1.7
    1.46   19.99
     1.7     1.7
    1.37    19.9
Pier Skew, UpSta & Num, DnSta & Num=  ,5178.7, 2 ,5178.7, 2 , 0 , 0 , 0 ,,
     1.7     1.7
    4.15   19.95
     1.7     1.7
    4.06   19.86
Pier Skew, UpSta & Num, DnSta & Num=  ,5209.6, 2 ,5209.6, 2 , 0 , 0 , 0 ,,
     1.7     1.7
    4.49   19.92
     1.7     1.7
     4.4   19.83
Pier Skew, UpSta & Num, DnSta & Num=  ,5239.9, 2 ,5239.9, 2 , 0 , 0 , 0 ,,
     1.7     1.7
    1.66   19.89
     1.7     1.7
    1.57    19.8
Pier Skew, UpSta & Num, DnSta & Num=  ,5269.5, 2 ,5269.5, 2 , 0 , 0 , 0 ,,
     1.7     1.7
   -1.87   19.86
     1.7     1.7
   -1.96   19.77
Pier Skew, UpSta & Num, DnSta & Num=  ,5299.1, 2 ,5299.1, 2 , 0 , 0 , 0 ,,
     1.7     1.7
    1.93   19.82
     1.7     1.7
    1.84   19.73
Abutment Skew #Up #Dn= , 2 , 2
  4843.4  4891.9
   19.37    -.12
  4843.4  4891.9
   19.28    -.21
Abutment Skew #Up #Dn= , 2 , 2
  5327.8 5329.39
    3.67   18.79
  5327.8 5329.39
    3.58    18.7
BR Coef= 1 , 1 , 0 ,1.25, 0 ,,,0.8,0,2,0,
WSPro=,,,, 1 ,,,, 0 ,,,, 0 ,,,,-1 ,-1 ,-1 , 0 , 0 , 0 , 0 , 0
BR U #Sta/Elev= 112
  3641.3    23.8  4336.8   22.13  4638.5   21.41 4640.49    21.4  4640.6    21.4
 4640.71    21.4  4641.3    21.4  4693.9   21.15    4752   20.82  4808.8   20.53
  4843.4   19.37 4843.51   19.37  4843.6   19.37  4844.7   19.33  4885.3    3.27
  4891.8    -.11  4891.9    -.12  4902.9   -1.51  4915.3   -1.27  4928.3   -2.83
  4942.1    -3.4  4944.4   -3.72  4966.2   -23.2  4985.7  -30.35  5001.7   -30.6
  5022.9  -29.14  5042.8  -20.49  5059.2  -15.51  5089.1  -12.55    5108    -.21
  5110.9    5.64    5119    2.97  5143.2    5.36  5148.9    2.38  5178.7    5.23
  5198.3    4.47  5209.6    5.57  5230.7    5.52  5239.9     2.8  5261.2    -.74
  5269.5    -.88  5307.1     4.1  5322.1     3.4  5327.8    3.67 5329.19    3.73
  5329.3    3.74  5329.4    3.74  5337.1     4.1  5352.1     3.8  5362.1     3.1
  5367.1     3.2  5377.1       5 5393.09    5.96  5393.2    5.97 5393.31    5.97
  5397.1     6.2  5402.1     6.9  5407.1     7.2  5427.1     6.2  5432.1     6.3
  5442.1     4.7  5442.4     4.7  5457.4     2.9  5462.4     3.3  5467.4     3.9
  5472.4     4.1  5482.4       5  5487.4     4.4  5517.4     4.8  5522.4     4.5
  5532.4       3  5562.4     4.6  5572.4     3.9  5597.4     4.2  5622.4       4
  5632.4     4.9  5637.4     4.9  5647.4     4.2  5657.4     4.3  5667.4     3.8
  5672.4       4  5687.4     3.5  5697.4     4.2  5702.4     4.1  5732.4     4.5
  5747.4     3.6  5774.2       4  5779.2     4.4  5809.2     4.7  5824.2       4
  5849.2     4.6  5859.2     4.3  5874.2     4.8  5884.2     5.9  5889.2     5.9
  5914.2     4.6  5949.2     4.5  5964.2     5.1  5974.2       5  5979.2     4.7
  6024.2     6.9  6074.2     7.7  6119.2     9.4  6174.2    10.2  6189.2      11
  6299.2    14.6  6319.2    14.3  6324.2    14.4  6334.2      15  6364.2    15.5
  6428.8    16.9  7641.3    23.8
BR U #Mann= 5
  3641.3      .2  4336.8      .1  4844.7    .035  5110.9      .1  6428.8      .2
BR U Banks=4844.7,5110.9
BR D #Sta/Elev= 112
  3641.3   23.71  4336.8   22.04  4638.5   21.32 4640.49   21.31  4640.6   21.31
 4640.71   21.31  4641.3   21.31  4693.9   21.06    4752   20.73  4808.8   20.44
  4843.4   19.28 4843.51   19.28  4843.6   19.28  4844.7   19.24  4885.3    3.18
  4891.8     -.2  4891.9    -.21  4902.9    -1.6  4915.3   -1.36  4928.3   -2.92
  4942.1   -3.49  4944.4   -3.81  4966.2  -23.29  4985.7  -30.44  5001.7  -30.69
  5022.9  -29.23  5042.8  -20.58  5059.2   -15.6  5089.1  -12.64    5108     -.3
  5110.9    5.55    5119    2.88  5143.2    5.27  5148.9    2.29  5178.7    5.14
  5198.3    4.38  5209.6    5.48  5230.7    5.43  5239.9    2.71  5261.2    -.83
  5269.5    -.97  5307.1    4.01  5322.1    3.31  5327.8    3.58 5329.19    3.64
  5329.3    3.65  5329.4    3.65  5337.1    4.01  5352.1    3.71  5362.1    3.01
  5367.1    3.11  5377.1    4.91 5393.09    5.87  5393.2    5.88 5393.31    5.88
  5397.1    6.11  5402.1    6.81  5407.1    7.11  5427.1    6.11  5432.1    6.21
  5442.1    4.61  5442.4    4.61  5457.4    2.81  5462.4    3.21  5467.4    3.81
  5472.4    4.01  5482.4    4.91  5487.4    4.31  5517.4    4.71  5522.4    4.41
  5532.4    2.91  5562.4    4.51  5572.4    3.81  5597.4    4.11  5622.4    3.91
  5632.4    4.81  5637.4    4.81  5647.4    4.11  5657.4    4.21  5667.4    3.71
  5672.4    3.91  5687.4    3.41  5697.4    4.11  5702.4    4.01  5732.4    4.41
  5747.4    3.51  5774.2    3.91  5779.2    4.31  5809.2    4.61  5824.2    3.91
  5849.2    4.51  5859.2    4.21  5874.2    4.71  5884.2    5.81  5889.2    5.81
  5914.2    4.51  5949.2    4.41  5964.2    5.01  5974.2    4.91  5979.2    4.61
  6024.2    6.81  6074.2    7.61  6119.2    9.31  6174.2   10.11  6189.2   10.91
  6299.2   14.51  6319.2   14.21  6324.2   14.31  6334.2   14.91  6364.2   15.41
  6428.8   16.81  7641.3   23.71
BR D #Mann= 5
  3641.3      .2  4336.8      .1  4844.7    .035  5110.9      .1  6428.8      .2
BR D Banks=4844.7,5110.9
BC Design=,, 0 ,, 0 ,,,,,,
BC HTab HWMax=23.83
BC Use User HTab Curves=0
BC User HTab FreeFlow(D)= 0

Type RM Length L Ch R = 1 ,15440.2 ,1028.1,1028.1,1028.1
BEGIN DESCRIPTION:
Downstream Section of Bridge/Culvert/Weir
END DESCRIPTION:
XS GIS Cut Line= 6
        3178980.      13845841.5      3177331.96     13845413.87
      3177072.46     13845329.25      3176886.68     13845271.74
      3176709.28     13845209.67      3175169.71     13844638.79
#Sta/Elev= 30
  3641.3   23.86  4336.8   22.19  4844.7   19.39  4891.8    -.05  4944.4   -3.66
  4966.2  -23.14  4985.7  -30.29  5001.7  -30.54  5022.9  -29.08  5059.2  -15.45
  5089.1  -12.49    5108    -.15  5110.9     5.7    5119    3.03  5143.2    5.42
  5148.9    2.44  5178.7    5.29  5230.7    5.58  5269.5    -.82  5307.1    4.16
  5367.1    3.26  5407.1    7.26  5457.4    2.96  5482.4    5.06  5532.4    3.06
  5824.2    4.06  5884.2    5.96  5979.2    4.76  6428.8   16.96  7641.3   23.86
#Mann= 5 , 1 , 0
  3641.3      .2       0  4336.8      .1       0  4844.7    .035       0
  5110.9      .1       0  6428.8      .2       0
#XS Ineff= 2 , 0
       0    4833    22.8    5340       0    22.8
Permanent Ineff=
       F       F
Bank Sta=4844.7,5110.9
XS Rating Curve= 0 ,0
Exp/Cntr=0.5,0.3

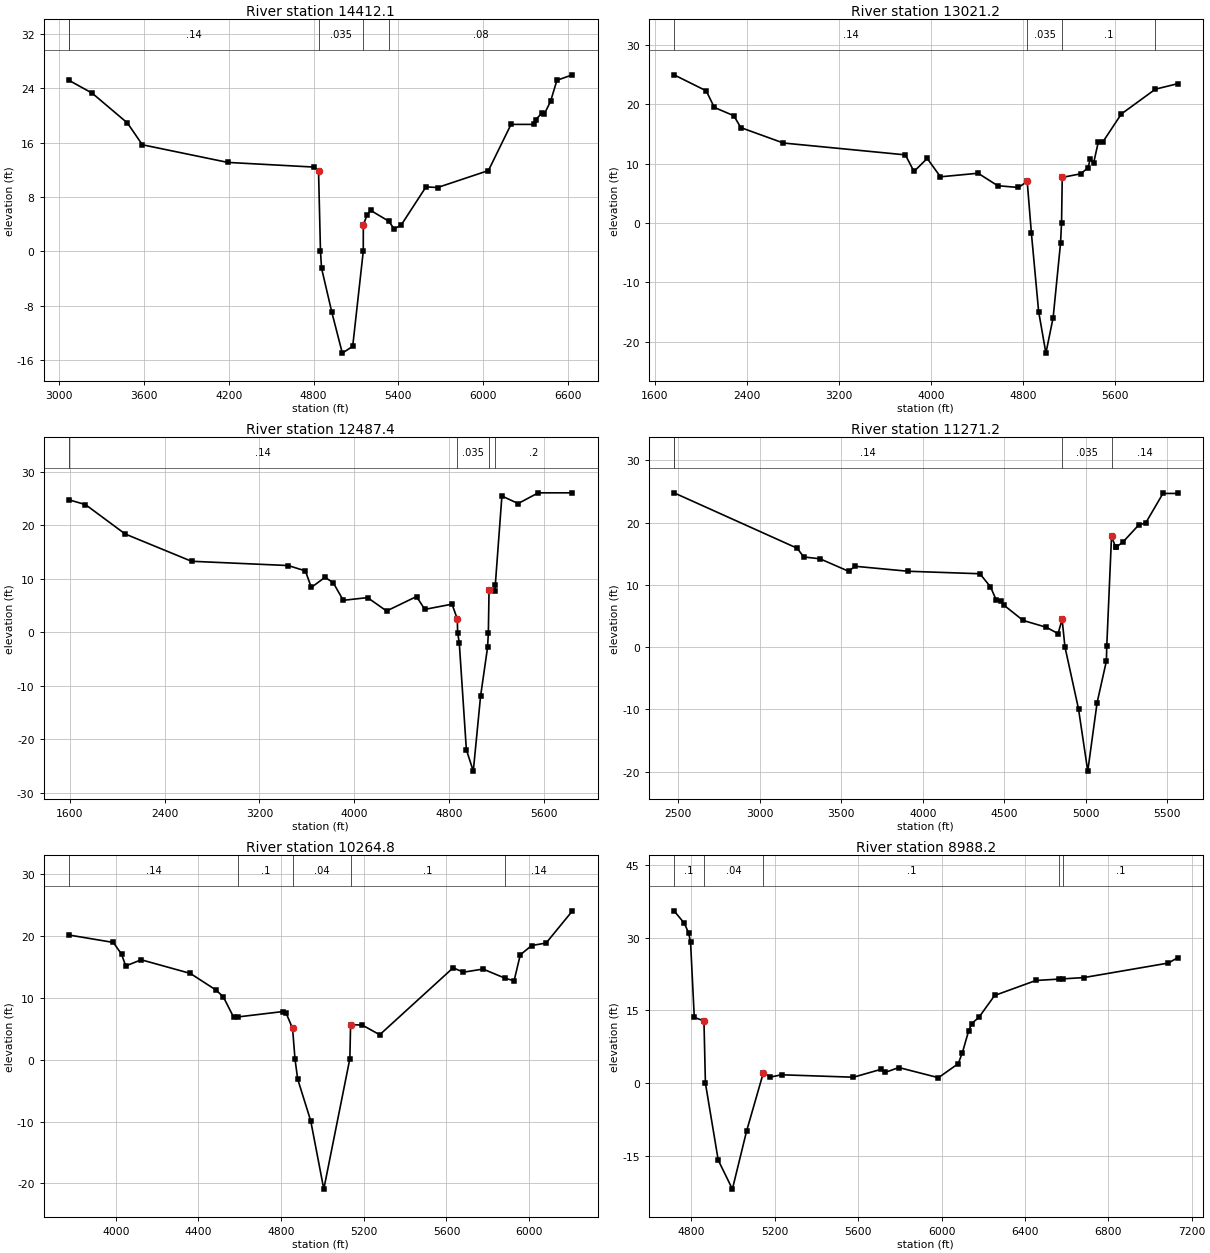
Type RM Length L Ch R = 1 ,14412.1 ,978.9,1390.9,1498.6
BEGIN DESCRIPTION:
Cross Section 14412.1
END DESCRIPTION:
XS GIS Cut Line= 6
       3178767.6     13845558.62      3177899.48     13844690.51
      3177457.52     13844469.53      3177110.28     13844690.51
      3176707.79     13844777.32      3175699.76     13844621.04
#Sta/Elev= 30
  3066.9    25.2  3231.9    23.3  3481.9    18.9  3586.9    15.7  4191.9    13.1
  4804.8   12.41  4834.5   11.83  4848.1     .08  4855.7   -2.47  4928.8   -8.99
  5002.8  -14.99  5076.3  -13.99  5151.1     .01  5151.6    3.87  5177.4    5.34
  5204.2    6.02  5330.9    4.45  5370.3     3.3  5420.3     3.9  5595.3     9.5
  5677.1     9.4  6037.1    11.9  6197.1    18.7  6357.1    18.7  6372.1    19.4
  6417.1    20.4  6432.1    20.2  6477.1    22.1  6522.1    25.2  6632.1      26
#Mann= 5 , 1 , 0
  3066.9      .2       0  3066.9     .14       0  4834.5    .035       0
  5151.6      .1       0  5330.9     .08       0
Bank Sta=4834.5,5151.6
XS Rating Curve= 0 ,0
Exp/Cntr=0.3,0.1

Type RM Length L Ch R = 1 ,13021.2 ,72.4,533.8,763.3
BEGIN DESCRIPTION:
Cross Section 13021.2
END DESCRIPTION:
XS GIS Cut Line= 6
       3178862.3     13845586.25      3177078.71     13843636.93
      3176897.19     13843423.84      3176257.94     13843400.17
      3175666.04     13843009.51      3175572.68     13842961.37
#Sta/Elev= 30
  1766.4      25  2046.4    22.3  2116.4    19.5  2286.4    18.1  2346.4    16.1
  2716.4    13.5  3776.4    11.5  3851.4     8.7  3966.4    10.9  4081.4     7.8
  4408.6     8.4  4578.6     6.3  4758.5       6  4835.2    7.01  4871.8   -1.76
  4934.6  -14.94  4997.6  -21.94  5060.6  -15.94  5124.7   -3.41  5133.7     .04
  5139.6     7.7  5298.5     8.3  5363.2     9.3  5383.2    10.8  5413.2    10.2
  5453.2    13.7  5493.2    13.7  5653.2    18.4  5949.1   22.58  6142.4    23.5
#Mann= 4 , 1 , 0
  1766.4     .14       0  4835.2    .035       0  5139.6      .1       0
  5949.1      .2       0
Bank Sta=4835.2,5139.6
XS Rating Curve= 0 ,0
Exp/Cntr=0.3,0.1

Type RM Length L Ch R = 1 ,12487.4 ,527.1,1216.2,1713.8
BEGIN DESCRIPTION:
Cross Section 12487.4
END DESCRIPTION:
XS GIS Cut Line= 6
      3178901.76     13845554.68      3178215.16     13844781.26
       3177386.5     13843921.04      3177015.57     13843384.38
      3176542.05     13842610.97      3176455.24     13842161.12
#Sta/Elev= 30
  1592.7    24.8  1732.7    23.9  2067.7    18.4  2626.9    13.3  3441.9    12.5
  3586.9    11.5  3636.9     8.4  3751.9    10.3  3821.3     9.3  3906.3       6
  4111.3     6.5  4271.3       4  4523.7     6.7  4593.7     4.3  4823.3    5.28
  4867.8    2.49  4870.4    -.06  4884.2   -1.94  4944.1  -21.95  5002.5  -25.95
  5063.8  -11.95  5123.1   -2.76  5129.5    -.04  5135.4       8  5184.6    7.83
  5187.9    8.82  5243.7    25.5  5380.6    24.1  5550.6    26.1  5838.7    26.1
#Mann= 5 , 1 , 0
  1592.7      .2       0  1592.7     .14       0  4867.8    .035       0
  5135.4      .1       0  5187.9      .2       0
Bank Sta=4867.8,5135.4
XS Rating Curve= 0 ,0
Exp/Cntr=0.3,0.1

Type RM Length L Ch R = 1 ,11271.2 ,1043.1,1006.4,968.1
BEGIN DESCRIPTION:
Cross Section 11271.2
END DESCRIPTION:
XS GIS Cut Line= 5
      3178941.22     13845499.43      3177599.58     13843976.28
      3177536.44     13843731.63      3177844.23     13843376.49
      3177870.95     13843042.51
#Sta/Elev= 30
  2475.4    24.8  3230.4    15.9  3270.4    14.5  3370.4    14.2  3545.4    12.2
  3585.4      13  3910.4    12.2  4350.4    11.8  4415.4     9.7  4450.4     7.6
  4480.4     7.4  4495.4     6.8  4615.2     4.3  4757.8     3.2  4829.7    2.18
  4854.6    4.46  4871.8     .06    4955   -9.91  5011.7  -19.91    5069   -8.91
    5126   -2.22  5128.2     .13  5157.4   17.79  5183.1   16.04  5187.8    16.1
  5227.8    16.9  5322.8    19.6  5367.8      20  5472.8    24.7  5562.8    24.7
#Mann= 4 , 1 , 0
  2475.4      .2       0  2475.4     .14       0  4854.6    .035       0
  5157.4     .14       0
Bank Sta=4854.6,5157.4
XS Rating Curve= 0 ,0
Exp/Cntr=0.3,0.1

Type RM Length L Ch R = 1 ,10264.8 ,1437.9,1276.6,1024.7
BEGIN DESCRIPTION:
Cross Section 10264.8
END DESCRIPTION:
XS GIS Cut Line= 6
      3179052.13     13845030.87      3178754.97     13844798.15
      3178532.73      13844217.3      3178598.39     13843727.37
       3178628.7      13843363.7      3178259.98     13842919.23
#Sta/Elev= 30
  3773.4    20.1  3988.4    18.9  4028.4      17  4048.4    15.1  4123.4    16.1
  4360.9    13.9  4485.9    11.2  4520.9    10.1  4570.9     6.8  4591.9    6.88
  4807.3    7.74  4825.1    7.44  4855.6    5.02  4867.4     .05  4880.3   -3.15
  4943.5   -9.91  5006.6  -20.91  5132.7     .15  5136.2    5.65  5193.5    5.55
  5277.1       4    5632    14.8    5682    14.1    5777    14.6  5882.5   13.14
    5927    12.7    5957    16.9    6012    18.4    6082    18.8  6209.5      24
#Mann= 5 , 1 , 0
  3773.4     .14       0  4591.9      .1       0  4855.6     .04       0
  5136.2      .1       0  5882.5     .14       0
Bank Sta=4855.6,5136.2
XS Rating Curve= 0 ,0
Exp/Cntr=0.3,0.1

Type RM Length L Ch R = 1 ,8988.2  ,1198.8,1173,1123.6
BEGIN DESCRIPTION:
Cross Section 8988.2
END DESCRIPTION:
XS GIS Cut Line= 6
      3179866.39     13843905.48      3179863.53     13843784.44
       3179601.7     13843503.21      3179388.35     13843070.05
      3178690.11     13842840.54      3178101.49     13842499.96
#Sta/Elev= 30
  4716.7    35.6  4766.7      33  4786.7      31  4795.9    29.2  4813.9   13.56
  4860.3   12.84  4867.3    -.04  4928.7  -15.94  4996.7  -21.94  5064.8   -9.94
  5144.8    2.06  5179.3    1.23  5232.3     1.7  5577.3     1.2  5707.3     2.8
  5730.1     2.2  5795.1     3.2  5985.1     1.1  6080.1       4  6100.1     6.3
  6130.1    10.8  6145.1    12.3  6179.6    13.6  6254.6    18.1  6452.6    21.2
  6565.6   21.49  6584.8   21.54  6682.6    21.8  7087.6    24.8  7132.6    25.9
#Mann= 5 , 1 , 0
  4716.7      .1       0  4860.3     .04       0  5144.8      .1       0
  6565.6     .14       0  6584.8      .1       0
Bank Sta=4860.3,5144.8
XS Rating Curve= 0 ,0
Exp/Cntr=0.3,0.1