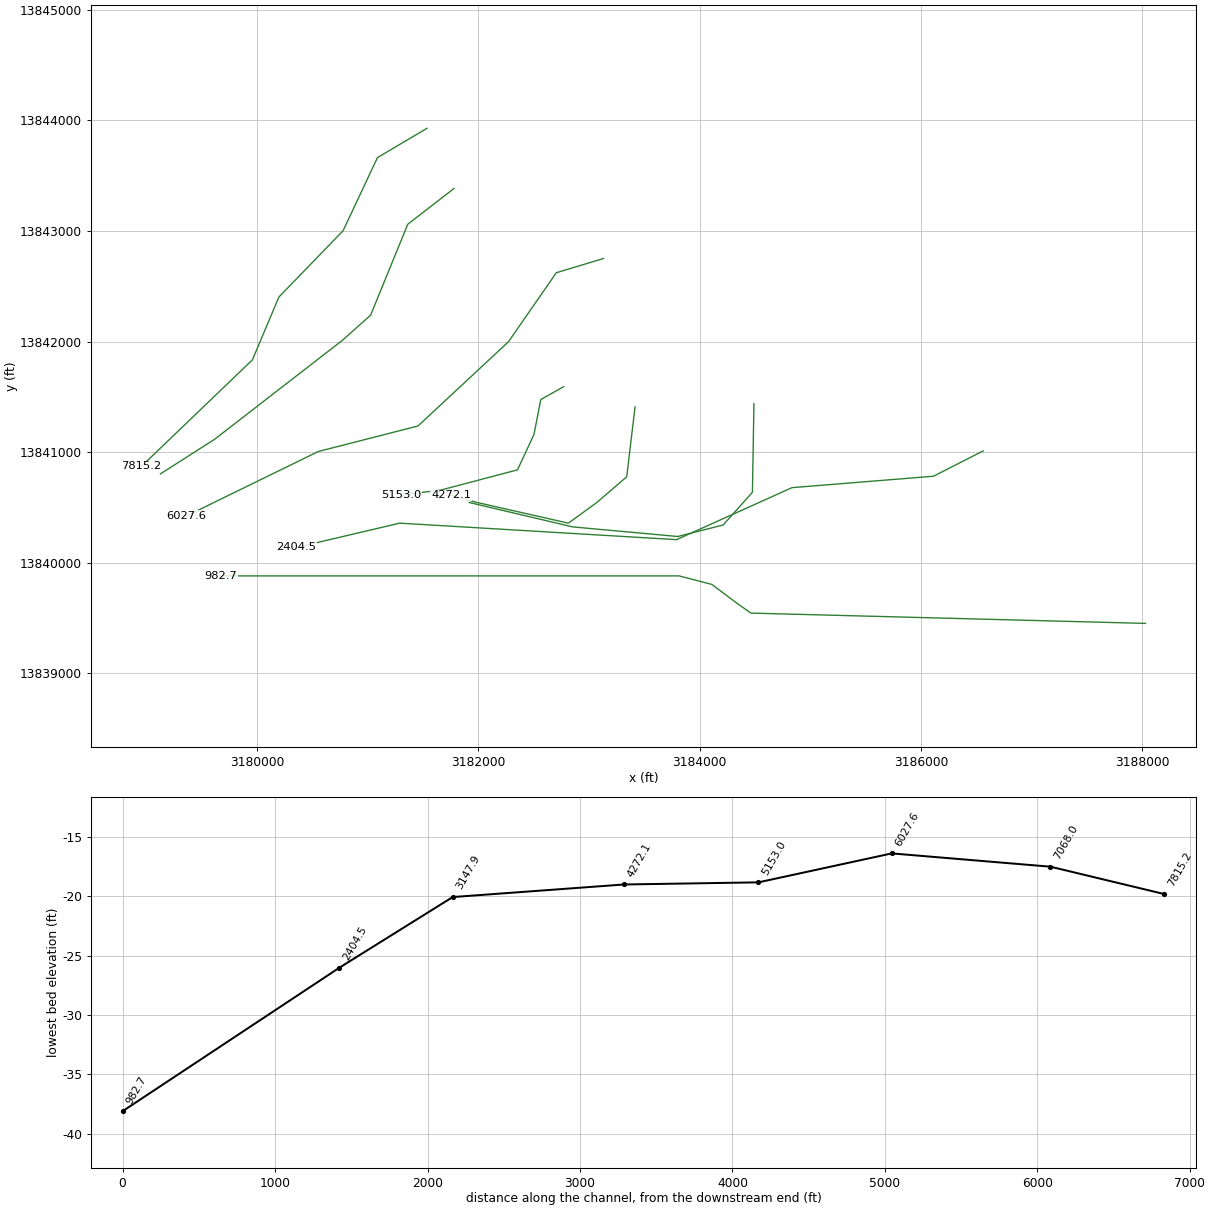
HEC-RAS study P100-00-00.prj: P100-00-00

--- P100-00-00.g01 (geometry) --- (continued)

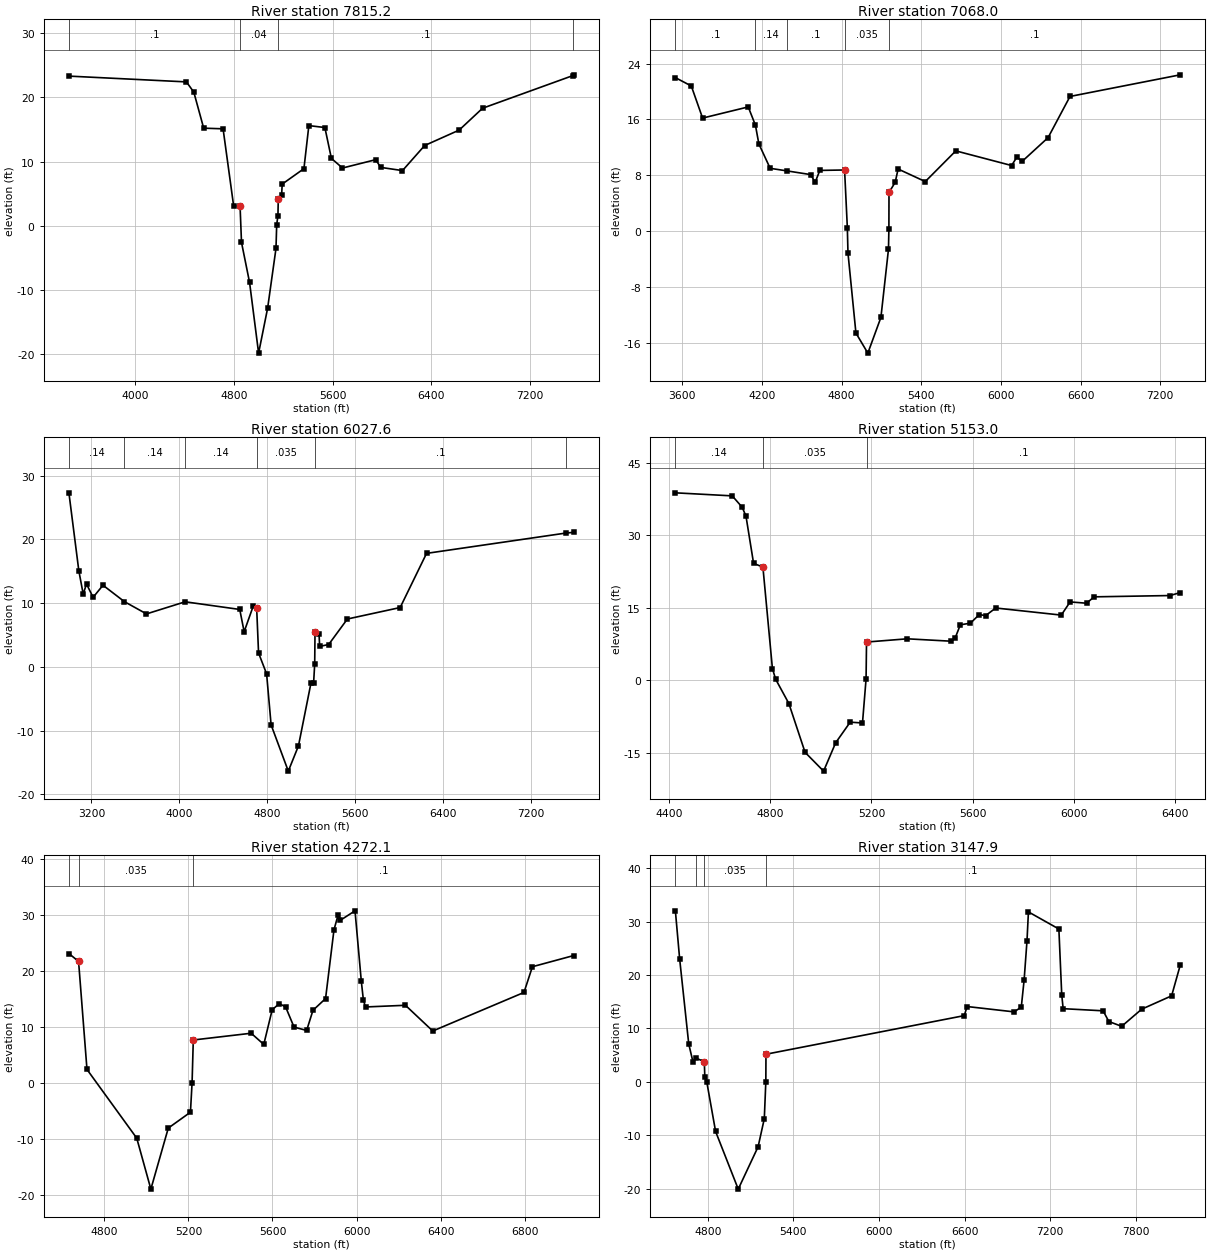
Type RM Length L Ch R = 1 ,7815.2  ,673,747.2,759.1
BEGIN DESCRIPTION:
Cross Section 7815.2
END DESCRIPTION:
XS GIS Cut Line= 6
      3181535.33     13843928.89      3181087.98     13843663.79
      3180777.21     13843002.43      3180197.41     13842403.29
      3179957.64      13841834.7      3178955.02     13840871.99
#Sta/Elev= 30
  3459.8    23.3  4413.9    22.4  4473.9    20.8  4553.9    15.2  4711.4    15.1
  4797.7    3.02  4849.4    3.02  4860.9   -2.57  4926.4    -8.8  4999.8   -19.8
    5073   -12.8  5140.9   -3.51  5146.6     .19  5156.7    1.57  5159.4    4.12
  5186.3    4.74  5191.4     6.5  5367.7     8.9  5407.7    15.6  5537.7    15.3
  5590.7    10.5  5680.7       9  5950.7    10.3  5990.7     9.1  6167.8     8.6
  6347.8    12.5  6627.8    14.9  6817.8    18.3  7552.2   23.39  7557.8    23.5
#Mann= 4 , 1 , 0
  3459.8      .1       0  4849.4     .04       0  5159.4      .1       0
  7552.2      .2       0
Bank Sta=4849.4,5159.4
XS Rating Curve= 0 ,0
Exp/Cntr=0.3,0.1

Type RM Length L Ch R = 1 ,7068.0  ,1188.6,1040.4,942.8
BEGIN DESCRIPTION:
Cross Section 7068.0
END DESCRIPTION:
XS GIS Cut Line= 6
      3181780.08     13843384.76        3181362.     13843060.95
      3181026.32     13842238.88      3180772.85     13842012.81
      3179615.11     13841115.39      3179126.23     13840803.34
#Sta/Elev= 30
  3548.4      22  3668.4    20.8  3753.4    16.2  4097.2    17.8  4151.3   15.18
  4177.2    12.5  4262.2       9  4385.6    8.64  4567.2     8.1  4601.3       7
  4636.3     8.7  4822.8    8.76  4843.5     .51  4848.3   -3.15  4908.2  -14.61
  4997.9  -17.49  5096.4  -12.37  5153.4   -2.59  5156.5     .31  5157.3    5.54
    5204       7  5225.8     8.9  5430.4     7.1  5660.4    11.5  6080.4     9.4
  6120.4    10.6  6160.4      10  6355.4    13.4  6520.4    19.3  7350.2    22.4
#Mann= 5 , 1 , 0
  3548.4      .1       0  4151.3     .14       0  4385.6      .1       0
  4822.8    .035       0  5157.3      .1       0
Bank Sta=4822.8,5157.3
XS Rating Curve= 0 ,0
Exp/Cntr=0.3,0.1

Type RM Length L Ch R = 1 ,6027.6  ,675.2,874.6,1143.5
BEGIN DESCRIPTION:
Cross Section 6027.6
END DESCRIPTION:
XS GIS Cut Line= 6
      3183131.16     13842751.44       3182704.7     13842622.51
      3182273.12     13841999.11      3181454.53     13841236.57
      3180553.63     13841005.78      3179359.16     13840421.94
#Sta/Elev= 30
  2995.2    27.3  3085.2    15.1  3125.2    11.4  3155.2      13  3215.2    10.9
  3305.2    12.8  3499.5   10.23  3700.7     8.3  4052.3    10.2  4548.9       9
  4588.9     5.5  4672.5    9.58  4702.9    9.15  4719.9    2.17  4793.1    -1.1
    4834   -9.11  4990.4  -16.37  5082.8  -12.41  5195.9   -2.61  5220.5   -2.54
  5230.5     .42  5233.4    5.39  5270.1    5.07  5275.6     3.2  5357.7     3.5
  5527.7     7.5  6007.7     9.3  6247.7    17.8  7516.3   20.99    7586    21.1
#Mann= 6 , 1 , 0
  2995.2     .14       0  3499.5     .14       0  4052.3     .14       0
  4702.9    .035       0  5233.4      .1       0  7516.3      .2       0
Bank Sta=4702.9,5233.4
XS Rating Curve= 0 ,0
Exp/Cntr=0.3,0.1

Type RM Length L Ch R = 1 ,5153.0  ,863.4,880.9,885.6
BEGIN DESCRIPTION:
Cross Section 5153.0
END DESCRIPTION:
XS GIS Cut Line= 6
      3182773.06     13841592.96       3182564.4     13841475.59
      3182503.02     13841159.92      3182353.96     13840839.86
      3181656.85     13840655.72      3181300.65     13840613.84
#Sta/Elev= 30
  4424.5   38.82  4649.5   38.19  4688.9   35.83  4703.9   33.97  4733.9   24.21
  4770.8   23.45  4808.4    2.43  4821.2     .22  4873.5   -4.81  4937.5  -14.91
  5010.8  -18.81  5058.6  -12.94  5116.1   -8.67  5164.7   -8.84  5178.9     .26
  5180.7    7.92  5341.8    8.59  5516.8    8.09  5531.8    8.82  5551.8   11.49
  5591.8   11.83  5626.8   13.61  5651.8   13.39  5691.8   14.97  5951.1    13.5
  5986.1   16.23  6051.1   15.96  6081.1   17.28  6381.5   17.55  6421.5   18.16
#Mann= 3 , 1 , 0
  4424.5     .14       0  4770.8    .035       0  5180.7      .1       0
#XS Ineff= 2 , 0
       0                  5691.8       0   14.97
Permanent Ineff=
       F       F
Bank Sta=4770.8,5180.7
XS Rating Curve= 0 ,0
Exp/Cntr=0.3,0.1

Type RM Length L Ch R = 1 ,4272.1  ,1104.8,1124.2,1280
BEGIN DESCRIPTION:
Cross Section 4272.1
END DESCRIPTION:
XS GIS Cut Line= 6
      3183416.68     13841409.78      3183341.34     13840776.96
      3183072.99     13840546.11      3182814.31     13840357.59
      3181981.29     13840546.11      3181753.33     13840609.68
#Sta/Elev= 30
  4631.4   23.16  4677.4   21.75  4717.4    2.42  4954.2   -9.87  5021.4  -18.99
  5104.3   -8.07  5209.7   -5.23  5217.5     .04  5223.3    7.69  5498.7     8.9
  5558.7     6.9  5598.7    13.1  5632.7    14.2  5662.7    13.6  5702.7      10
  5762.7     9.4  5792.7      13  5852.7    15.1  5892.7    27.4  5912.7    30.1
  5922.7    29.1  5992.8    30.8  6022.8    18.2  6032.8    14.8  6042.8    13.6
  6232.8    13.9  6362.8     9.3  6796.9    16.2  6836.9    20.8  7033.5    22.8
#Mann= 3 , 1 , 0
  4631.4     .14       0  4677.4    .035       0  5223.3      .1       0
#XS Ineff= 2 , 0
       0                  5632.7       0    14.2
Permanent Ineff=
       F       F
Bank Sta=4677.4,5223.3
XS Rating Curve= 0 ,0
Exp/Cntr=0.3,0.1

Type RM Length L Ch R = 1 ,3147.9  ,1143.9,743.4,173.2
BEGIN DESCRIPTION:
Cross Section 3147.9
END DESCRIPTION:
XS GIS Cut Line= 6
      3184491.39     13841438.08      3184477.47     13840636.65
      3184213.23     13840341.11      3183802.39     13840236.95
      3182853.42     13840323.75      3181918.99      13840543.9
#Sta/Elev= 30
  4572.8      32  4602.8      23  4666.5     7.1  4696.5     3.7  4716.2    4.45
  4775.7    3.81  4779.2     .85  4793.2    -.05  4854.7   -9.27  5013.3  -20.05
  5152.6  -12.12    5196   -6.87  5206.7     .07  5207.7    5.18  6597.1    12.4
  6617.1    14.1  6946.8    13.1  6996.8      14  7016.8    19.1  7036.8    26.4
  7046.8    31.8  7260.2    28.6  7280.2    16.3  7290.2    13.7  7570.2    13.3
  7610.2    11.3  7700.2    10.4  7840.2    13.6  8050.2    16.1  8110.2    21.8
#Mann= 4 , 1 , 0
  4572.8     .14       0  4716.2      .1       0  4775.7    .035       0
  5207.7      .1       0
#XS Ineff= 2 , 0
       0                  6617.1       0    14.1
Permanent Ineff=
       F       F
Bank Sta=4775.7,5207.7
XS Rating Curve= 0 ,0
Exp/Cntr=0.3,0.1

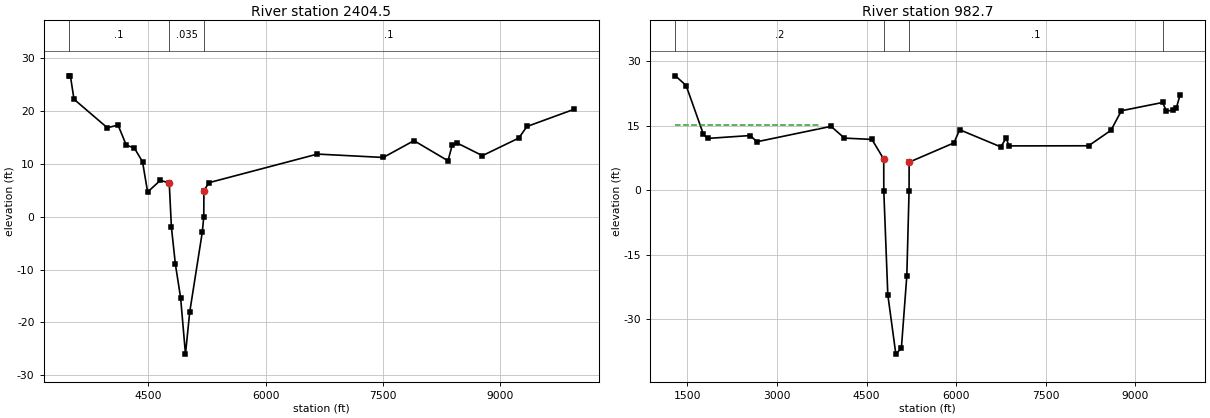
Type RM Length L Ch R = 1 ,2404.5  ,1526.4,1421.8,1114.4
BEGIN DESCRIPTION:
Cross Section 2404.5
END DESCRIPTION:
XS GIS Cut Line= 6
      3186563.07     13841010.81      3186114.57     13840782.16
      3184835.48     13840678.71      3183791.52     13840208.46
      3181289.79     13840357.67       3180354.6     13840137.74
#Sta/Elev= 30
  3487.5   26.66  3507.5   26.54  3552.5   22.23  3977.5   16.84  4115.9   17.33
  4220.9   13.53  4323.4   13.01  4428.4    10.4  4493.4    4.67  4656.2    6.88
  4769.8    6.37  4797.4   -1.98  4848.3   -8.99  4915.3  -15.37  4977.2  -26.01
  5030.9  -18.11  5191.7   -2.96  5211.1    -.05  5212.8     4.9  5275.7    6.43
  6663.3   11.85  7504.9   11.21  7897.5   14.39  8332.5   10.58  8387.5   13.65
  8452.5   13.92  8771.8   11.55  9236.8   14.88  9341.3   17.07  9938.8    20.3
#Mann= 3 , 1 , 0
  3487.5      .1       0  4769.8    .035       0  5212.8      .1       0
#XS Ineff= 2 , 0
       0                  7897.5       0   14.39
Permanent Ineff=
       F       F
Bank Sta=4769.8,5212.8
XS Rating Curve= 0 ,0
Exp/Cntr=0.3,0.1

Type RM Length L Ch R = 1 ,982.7   ,0,0,0
BEGIN DESCRIPTION:
Cross Section 982.7
Located At: 14TH XS DS MARKET ROAD
END DESCRIPTION:
XS GIS Cut Line= 6
      3188030.25     13839450.97      3184464.77     13839544.07
      3184352.06     13839622.68      3184110.31     13839803.61
       3183814.6     13839880.55      3179670.12     13839880.55
#Sta/Elev= 30
    1297   26.54    1477   24.29    1767   12.94    1837      12    2552   12.67
    2662   11.22  3904.4    14.8  4129.4   12.07  4589.4   11.77  4787.2    7.21
  4788.4    -.19  4855.6  -24.31  4990.1  -38.11    5083  -36.71    5174  -19.94
  5211.6    -.26  5212.9    6.48  5963.6   10.96  6058.6   14.02  6748.6   10.03
  6838.6   12.11  6883.6   10.26  8218.6   10.29  8593.6   13.88  8768.6   18.43
  9458.9   20.35  9523.6   18.29  9628.6   18.63  9688.6   19.06  9753.1    22.2
#Mann= 4 , 1 , 0
    1297      .2       0  4787.2    .035       0  5212.9      .1       0
  9458.9      .2       0
#XS Ineff= 2 , 0
       0  3694.4   15.01  6058.6       0   14.02
Permanent Ineff=
       F       F
Bank Sta=4787.2,5212.9
XS Rating Curve= 0 ,0
Exp/Cntr=0.3,0.1
LCMann Table=0

Chan Stop Cuts=-1
Use User Specified Reach Order=0
Composite Channel Slope=5